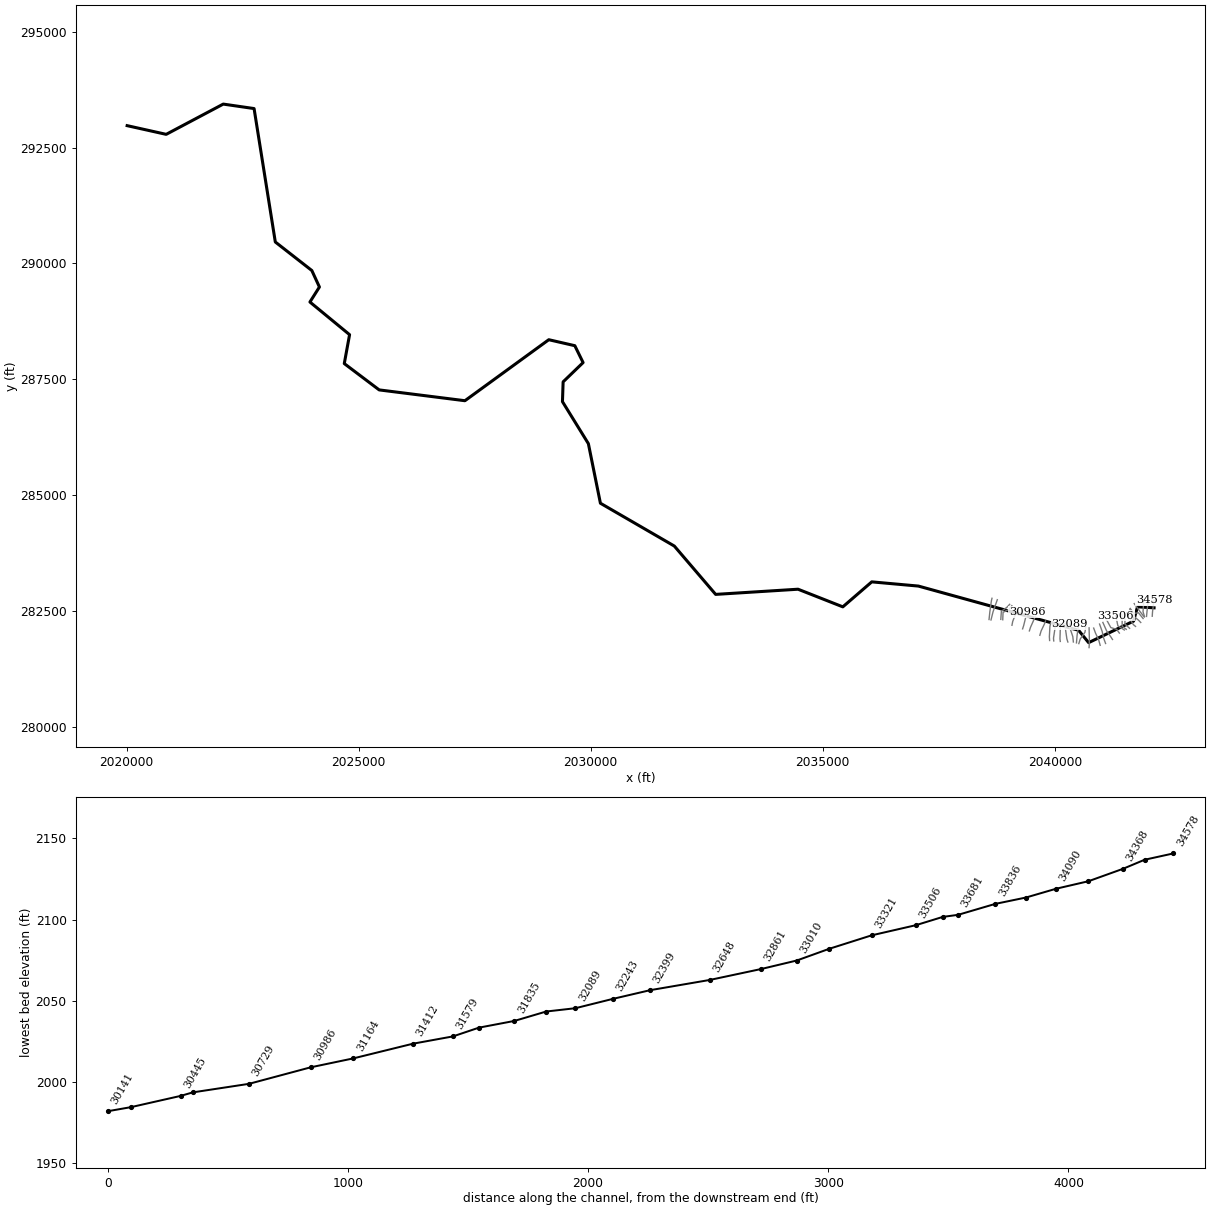
--- LICKCK1.prj (project) ---

Proj Title=LICKCK1
Current Plan=p01
Default Exp/Contr=0,0
English Units
Geom File=g01
Flow File=f01
Plan File=p01
BEGIN DESCRIPTION:
Stream Name: Lick Creek 1
Flood Zone: Approximate
Summers County, West Virginia
HEC-RAS Version: 5.0.7
Hydrology Method:
Regression.
Model Notes:
DS tie in with LICKCK3_AE.
END DESCRIPTION:
DSS Export Rating Curves= 0
DSS Export Rating Curve Sorted= 0
DSS Export Volume Flow Curves= 0
DXF Filename=..\..\LICKCK1(1).
DXF OffsetX= 0
DXF OffsetY= 0
DXF ScaleX= 0
DXF ScaleY= 0

--- LICKCK1.p01 (plan) ---

Plan Title=Floodplain
Program Version=5.07
Short Identifier=Floodplain
Geom File=g01
Flow File=f01
Subcritical Flow
K Sum by GR= 0
Std Step Tol= 0.01
Critical Tol= 0.01
Num of Std Step Trials= 20
Max Error Tol= 0.3
Flow Tol Ratio= 0.001
Split Flow NTrial= 30
Split Flow Tol= 0.02
Split Flow Ratio= 0.02
Log Output Level= 0
Friction Slope Method= 1
Unsteady Friction Slope Method= 2
Unsteady Bridges Friction Slope Method= 1
Parabolic Critical Depth
Global Vel Dist= 0 , 0 , 0
Global Log Level= 0
CheckData=True
Encroach Param=-1 ,0,0, 0
Mapping Interval=1HOUR
Computation Time Step Use Courant=        0
Computation Time Step Use Time Series=    0
Computation Time Step Count To Double=0
Computation Time Step Max Doubling=0
Computation Time Step Max Halving=0
Computation Time Step Residence Courant=0
Run HTab= 0
Run UNet= 0
Run Sediment= 0
Run PostProcess= 0
Run WQNet= 0
Run RASMapper= 0
UNET Theta= 0
UNET Theta Warmup= 0
UNET ZTol= 0
UNET ZSATol= 0
UNET MxIter= 0
UNET Max Iter WO Improvement= 0
UNET MaxInSteps= 0
UNET DtIC= 0
UNET DtMin= 0
UNET MaxCRTS= 0
UNET WFStab= 0
UNET SFStab= 0
UNET WFX= 1
UNET SFX= 1
UNET 1D Methodology=Finite Difference
UNET DSS MLevel= 1
UNET Pardiso=0
UNET DZMax Abort= 0
UNET Use Existing IB Tables= 0
UNET Froude Reduction=False
UNET Froude Limit= 0
UNET Froude Power= 0
UNET D1 Cores= 0
UNET D2 Coriolis=0
UNET D2 Cores= 0
UNET D2 Theta= 1
UNET D2 Theta Warmup= 1
UNET D2 Z Tol= 0.01
UNET D2 Volume Tol= 0.01
UNET D2 Max Iterations= 20
UNET D2 Equation= 0
UNET D2 RampUpFraction=0.1
UNET D2 TimeSlices= 1
UNET D2 Eddy Viscosity=0.3
UNET D2 BCVolumeCheck=0
UNET D1D2 MaxIter= 0
UNET D1D2 ZTol=0.01
UNET D1D2 QTol=0.1
UNET D1D2 MinQTol=1
Write IC File= 0
Write IC File at Fixed DateTime=0
Write IC File at Sim End=0
Echo Input=False
Echo Parameters=False
Echo Output=False
Write Detailed= 0
HDF Write Warmup=0
HDF Write Time Slices=0
HDF Flush=0
HDF Face Node Velocities=0
HDF Compression= 1
HDF Chunk Size= 1
HDF Spatial Parts= 1
HDF Use Max Rows=0
HDF Fixed Rows= 1
Calibration Method= 0
Calibration Iterations= 20
Calibration Max Change=0.05
Calibration Tolerance=0.2
Calibration Maximum=1.5
Calibration Minimum=0.5
Calibration Optimization Method= 1
WQ AD Non Conservative
WQ ULTIMATE=-1
WQ Max Comp Step=1HOUR
WQ Output Interval=15MIN
WQ Output Selected Increments= 0
WQ Output face flow=0
WQ Output face velocity=0
WQ Output face area=0
WQ Output face dispersion=0
WQ Output cell volume=0
WQ Output cell surface area=0
WQ Output cell continuity=0
WQ Output cumulative cell continuity=0
WQ Output face conc=0
WQ Output face dconc_dx=0
WQ Output face courant=0
WQ Output face peclet=0
WQ Output face adv mass=0
WQ Output face disp mass=0
WQ Output cell mass=0
WQ Output cell source sink temp=0
WQ Output nsm pathways=0
WQ Output nsm derived pathways=0
WQ Output MaxMinRange=-1
WQ Daily Max Min Mean=-1
WQ Daily Range=0
WQ Daily Time=0
WQ Create Restart=0
WQ Fixed Restart=0
WQ System Summary=0
WQ Write To DSS=0
WQ Use Fixed Temperature=0
Sorting and Armoring Iterations= 10
XS Update Threshold= 0.02
Bed Roughness Predictor= 0
Hydraulics Update Threshold= 0.02
Energy Slope Method= 1
Volume Change Method= 1
Sediment Retention Method= 0
XS Weighting Method= 0
Number of US Weighted Cross Sections= 1
Number of DS Weighted Cross Sections= 1
Upstream XS Weight=0
Main XS Weight=1
Downstream XS Weight=0
Number of DS XS's Weighted with US Boundary= 1
Upstream Boundary Weight= 1
Weight of XSs Associated with US Boundary= 0
Number of US XS's Weighted with DS Boundary= 1
Downstream Boundary Weight= 0.5
Weight of XSs Associated with DS Boundary= 0.5
Percentile Method= 0
Sediment Output Level= 3
Mass or Volume Output= 0
Output Increment Type= 1
Profile and TS Output Increment= 1
XS Output Flag= 0
XS Output Increment= 10
Write Gradation File= 0
Read Gradation Hotstart= 0
Write HDF5 File= 1
Write Binary Output= 1
Write DSS Sediment File= 0
SV Curve= 0
Specific Gage Flag= 0

--- LICKCK1.f01 (steady flow) ---

Flow Title=Flows
Program Version=5.07
Number of Profiles= 6
Profile Names=01pct,10pct,04pct,02pct,0_2pct,01plus
River Rch & RM=LICKCK1,Main            ,34578
     609     323     429     516     850     901
River Rch & RM=LICKCK1,Main            ,32648
     778     416     550     660    1080    1150
River Rch & RM=LICKCK1,Main            ,30986
     944     508     670     802    1306    1396
River Rch & RM=LICKCK1,Main            ,29179
    1077     583     767     917    1487    1593
River Rch & RM=LICKCK1,Main            ,23451
    1373     751     982    1171    1887    2031
River Rch & RM=LICKCK1,Main            ,16315
    2292    1278    1656    1964    3119    3390
River Rch & RM=LICKCK1,Main            ,10376
    2580    1445    1869    2213    3503    3816
River Rch & RM=LICKCK1,Main            ,10075
    2870    1614    2083    2464    3890    4245
River Rch & RM=LICKCK1,Main            ,4049
    3206    1811    2332    2756    4336    4742
River Rch & RM=LICKCK1,Main            ,3
    4843    2780    3552    4178    6500    7164
Boundary for River Rch & Prof#=LICKCK1,Main            , 1
Up Type= 0
Dn Type= 1
Dn Known WS=1531
Boundary for River Rch & Prof#=LICKCK1,Main            , 2
Up Type= 0
Dn Type= 1
Dn Known WS=1528.8
Boundary for River Rch & Prof#=LICKCK1,Main            , 3
Up Type= 0
Dn Type= 1
Dn Known WS=1529.7
Boundary for River Rch & Prof#=LICKCK1,Main            , 4
Up Type= 0
Dn Type= 1
Dn Known WS=1530.4
Boundary for River Rch & Prof#=LICKCK1,Main            , 5
Up Type= 0
Dn Type= 1
Dn Known WS=1532.2
Boundary for River Rch & Prof#=LICKCK1,Main            , 6
Up Type= 0
Dn Type= 1
Dn Known WS=1532.6
DSS Import GetInterval= 0
DSS Import GetPeak= 0
DSS Import FillOption= 0

--- LICKCK1.g01 (geometry) ---

Geom Title=Geometry
Program Version=5.07

River Reach=LICKCK1         ,Main
Reach XY= 30
2042139.47481116282574.9195500392041781.95798614282596.088008296
2041696.70998116282287.6900261972040729.16804778281823.721466445
2040512.64099001282090.2410394462037061.35101156283043.639956008
2036055.92598592283134.5289909562035432.29503308282595.548029521
2034466.92796983282975.9430237562032691.76400551 282864.36803666
2031801.04796872283906.7749586952030208.28997388284830.086956969
 2029948.7850056286115.0750145142029390.28502846287020.834991012
2029404.70201164287447.7010078732029835.21202986287863.144980133
2029656.69402086288227.4030081172029095.71040585288356.355819555
 2027288.6250395287040.8129751152025440.83202442287273.907984153
2024688.62698612287841.5979819622024802.77700698288465.107033753
2023948.17597781289169.2750005542024153.03702243 289492.88502858
2023989.47202406289848.5230226142023202.43201532290463.621028419
2022744.79098015 293340.887985692022080.40997001293437.386994138
2020850.68299434292784.9089971052020009.27339541292972.560552762

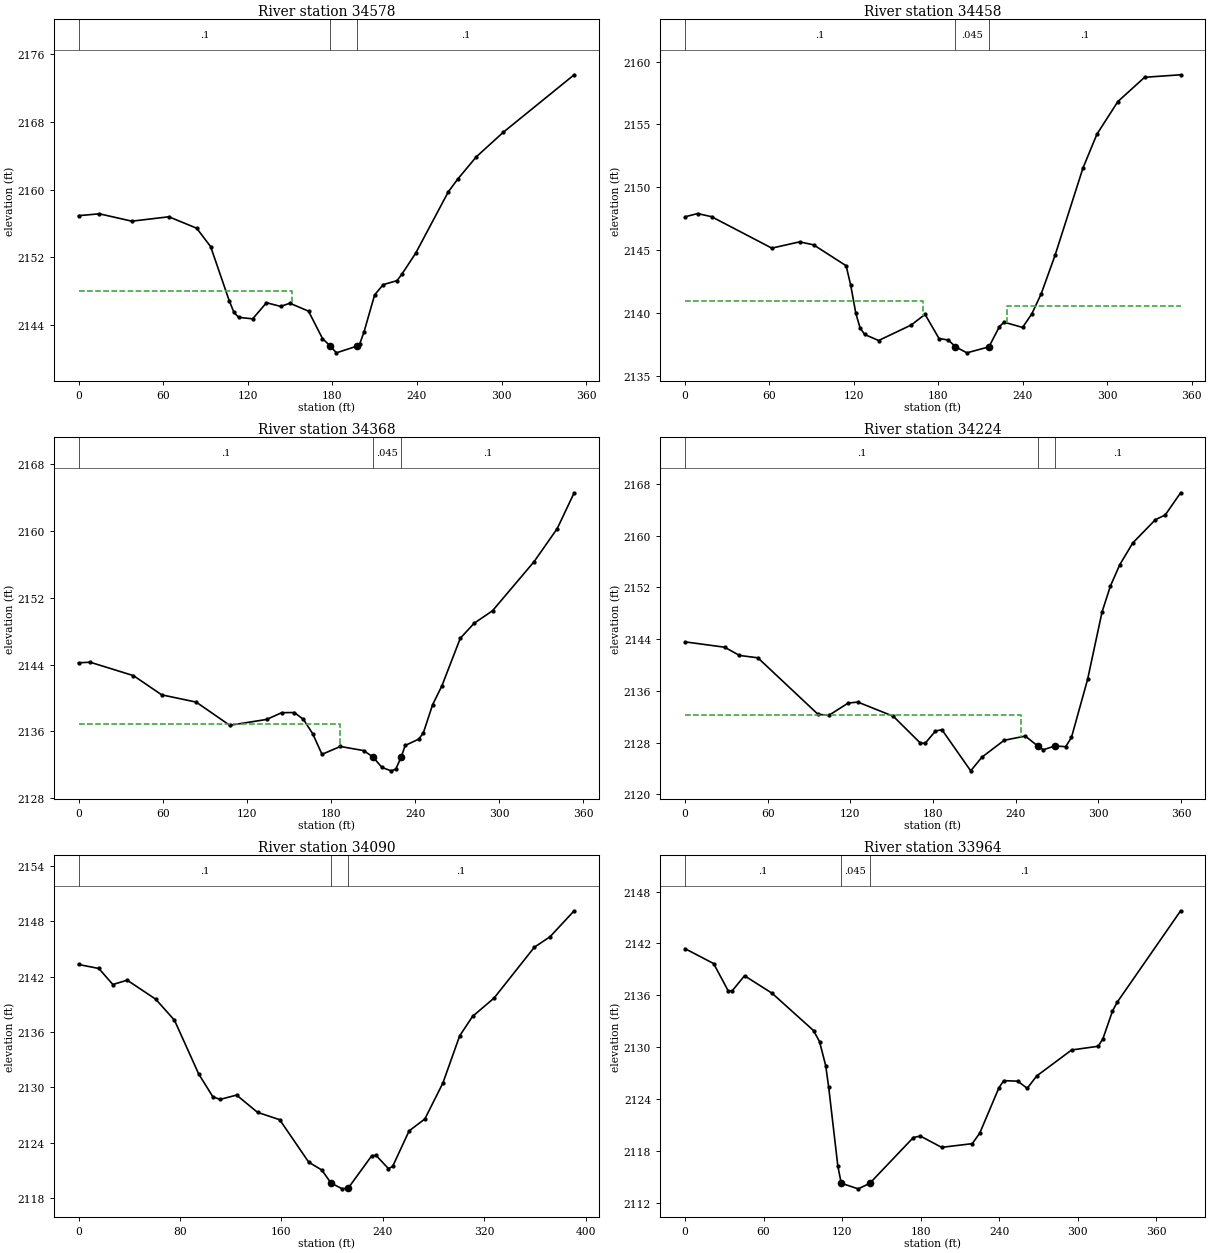
Type RM Length L Ch R = 1 ,34578   ,120.1,120.2,120.4
XS GIS Cut Line= 4
2042099.91716998 282393.079580592042106.18980533282487.739350406
2042128.49551215282669.902622775 2042139.2157901282742.264498898
#Sta/Elev= 30
       0 2156.92    14.8 2157.14    37.8 2156.27    64.1 2156.79    83.8 2155.44
    93.7 2153.27   106.9 2146.88   110.2 2145.52   113.5 2144.93   123.5 2144.75
   133.3 2146.65   143.3 2146.22   149.9 2146.59   163.1 2145.66     173 2142.43
   178.62141.529   182.9 2140.74   197.42141.529   199.4 2141.77   202.5 2143.23
     210 2147.57     216 2148.78   225.9 2149.26   229.2 2149.99   239.1 2152.49
   262.2 2159.72   268.9 2161.23   282.1 2163.86   301.1 2166.74   351.5 2173.54
#Mann= 3 ,-1 , 0
       0      .1       0   178.6    .045       0   197.4      .1       0
#XS Ineff= 2 , 0
          151.12 2148.07
Permanent Ineff=
       F       F
Bank Sta=178.6,197.4
XS Rating Curve= 0 ,0
Exp/Cntr(USF)=0,0
Exp/Cntr=0.3,0.1

Type RM Length L Ch R = 1 ,34458   ,89.1,89.9,90.6
XS GIS Cut Line= 4
2041977.03579017282389.0167931662041987.22603562282497.033394915
2042007.67293354282679.1966672832042015.23644996 282739.07450563
#Sta/Elev= 30
       0 2147.65       9 2147.91    18.9 2147.66    61.7 2145.16    81.5 2145.66
    91.4 2145.42   114.5 2143.76   117.8 2142.19   121.4 2139.97   124.4 2138.82
   127.7 2138.29   137.6 2137.81   160.7 2139.04   170.6 2139.89   180.5 2137.97
   187.1 2137.85   192.22137.315   200.3 2136.83     2162137.306   223.4 2138.91
   226.7 2139.27   239.9 2138.85   246.5 2139.94   253.1 2141.52     263  2144.6
   282.8 2151.53   292.7 2154.22   307.6 2156.82   326.6 2158.75   352.2 2158.95
#Mann= 3 ,-1 , 0
       0      .1       0   192.2    .045       0     216      .1       0
#XS Ineff= 2 , 0
          169.12 2140.93  228.49         2140.55
Permanent Ineff=
       F       F
Bank Sta=192.2,216
XS Rating Curve= 0 ,0
Exp/Cntr(USF)=0,0
Exp/Cntr=0.3,0.1

Type RM Length L Ch R = 1 ,34368   ,133.1,143.8,151.3
XS GIS Cut Line= 3
2041933.10244569282386.7323089692041901.58117831282489.050740674
2041916.86882868282734.952186033
#Sta/Elev= 30
       0 2144.21     8.3 2144.28    39.2 2142.67    59.3 2140.37    83.9  2139.5
   107.8 2136.72   134.1 2137.42   144.9 2138.23   153.9 2138.25   160.4 2137.42
     167  2135.7   173.6 2133.24   186.7 2134.18   203.2 2133.69   209.92132.935
   216.3 2131.67   222.9 2131.26   226.2 2131.46   230.2 2132.97   232.9  2134.3
   242.6 2135.06   245.9 2135.83   252.5  2139.2   259.1 2141.45   272.2 2147.15
   282.1 2148.95   295.2 2150.45   324.8 2156.33   341.3 2160.29   353.4 2164.59
#Mann= 3 ,-1 , 0
       0      .1       0   209.9    .045       0   230.2      .1       0
#XS Ineff= 2 , 0
          186.51 2136.82
Permanent Ineff=
       F       F
Bank Sta=209.9,230.2
XS Rating Curve= 0 ,0
Exp/Cntr(USF)=0,0
Exp/Cntr=0.3,0.1

Type RM Length L Ch R = 1 ,34224   ,122.5,134.6,146.3
XS GIS Cut Line= 4
2041927.25505885282377.4975628372041834.96376904282496.401929693
2041749.70613089282613.756561034 2041711.6344628282665.205320522
#Sta/Elev= 30
       0 2143.58    28.8 2142.75    39.5 2141.48    52.9 2141.11    96.5 2132.37
   104.4 2132.21   118.4 2134.11   125.4 2134.26   151.1 2132.07   170.8 2127.91
   174.3 2127.89   181.7 2129.77   186.4 2129.99   207.3 2123.62   215.4 2125.73
   231.6 2128.35   246.9    2129   255.9 2127.47     260 2126.88   268.32127.466
   276.2 2127.36   280.4 2128.79   292.1 2137.77   302.6 2148.22   308.7 2152.24
   315.5 2155.54   324.9 2158.89   341.3 2162.49   348.4 2163.21   359.6 2166.65
#Mann= 3 , 0 , 0
       0      .1       0   255.9    .045       0   268.3      .1       0
#XS Ineff= 2 , 0
          244.08  2132.3
Permanent Ineff=
       F       F
Bank Sta=255.9,268.3
XS Rating Curve= 0 ,0
Exp/Cntr(USF)=0,0
Exp/Cntr=0.3,0.1

Type RM Length L Ch R = 1 ,34090   ,135.3,125.5,109.8
XS GIS Cut Line= 5
2041903.27765694282344.1832981052041815.64367831282451.724351808
 2041804.3589561282468.2174073612041705.40062276282455.196574032
2041625.34781635282560.748708129
#Sta/Elev= 30
       0 2143.31      16 2142.88    27.1 2141.14    38.4 2141.61    60.9 2139.55
    75.7 2137.27    94.8 2131.45     106 2128.97   111.7 2128.69   124.7 2129.16
   141.2 2127.29   158.7 2126.49   181.6 2121.89   191.9 2121.04   199.22119.626
   208.1    2119   212.92119.107   231.3 2122.58   234.6 2122.64   244.5 2121.19
   247.8 2121.43   260.8 2125.28   273.2 2126.57   287.4 2130.45   300.7 2135.58
   310.8 2137.68   327.8 2139.67   359.6 2145.18     372 2146.32     391 2149.13
#Mann= 3 ,-1 , 0
       0      .1       0   199.2    .045       0   212.9      .1       0
Bank Sta=199.2,212.9
XS Rating Curve= 0 ,0
Exp/Cntr(USF)=0,0
Exp/Cntr=0.3,0.1

Type RM Length L Ch R = 1 ,33964   ,132.3,127.9,122.2
XS GIS Cut Line= 4
2041852.60912072282258.2202362262041805.06276325 282307.43488694
2041678.66375793282409.6693765342041616.59631812282543.656230716
#Sta/Elev= 30
       0 2141.39    21.9 2139.66      33 2136.51    36.1 2136.51    45.5 2138.25
    66.6 2136.22    98.2 2131.91   102.8 2130.63   107.5 2127.86   109.8 2125.35
   116.8 2116.21   119.4 2114.24   132.3 2113.59   141.12114.216   174.5 2119.53
   179.8  2119.7   196.1 2118.39   219.5 2118.82   225.2 2120.03   239.8 2125.26
   243.5 2126.11   254.3 2126.05   261.5 2125.22   268.7 2126.65   295.4 2129.66
   315.7 2130.09   319.3 2130.95   326.6 2134.15   330.2 2135.18   378.7 2145.77
#Mann= 3 ,-1 , 0
       0      .1       0   119.4    .045       0   141.1      .1       0
Bank Sta=119.4,141.1
XS Rating Curve= 0 ,0
Exp/Cntr(USF)=0,0
Exp/Cntr=0.3,0.1

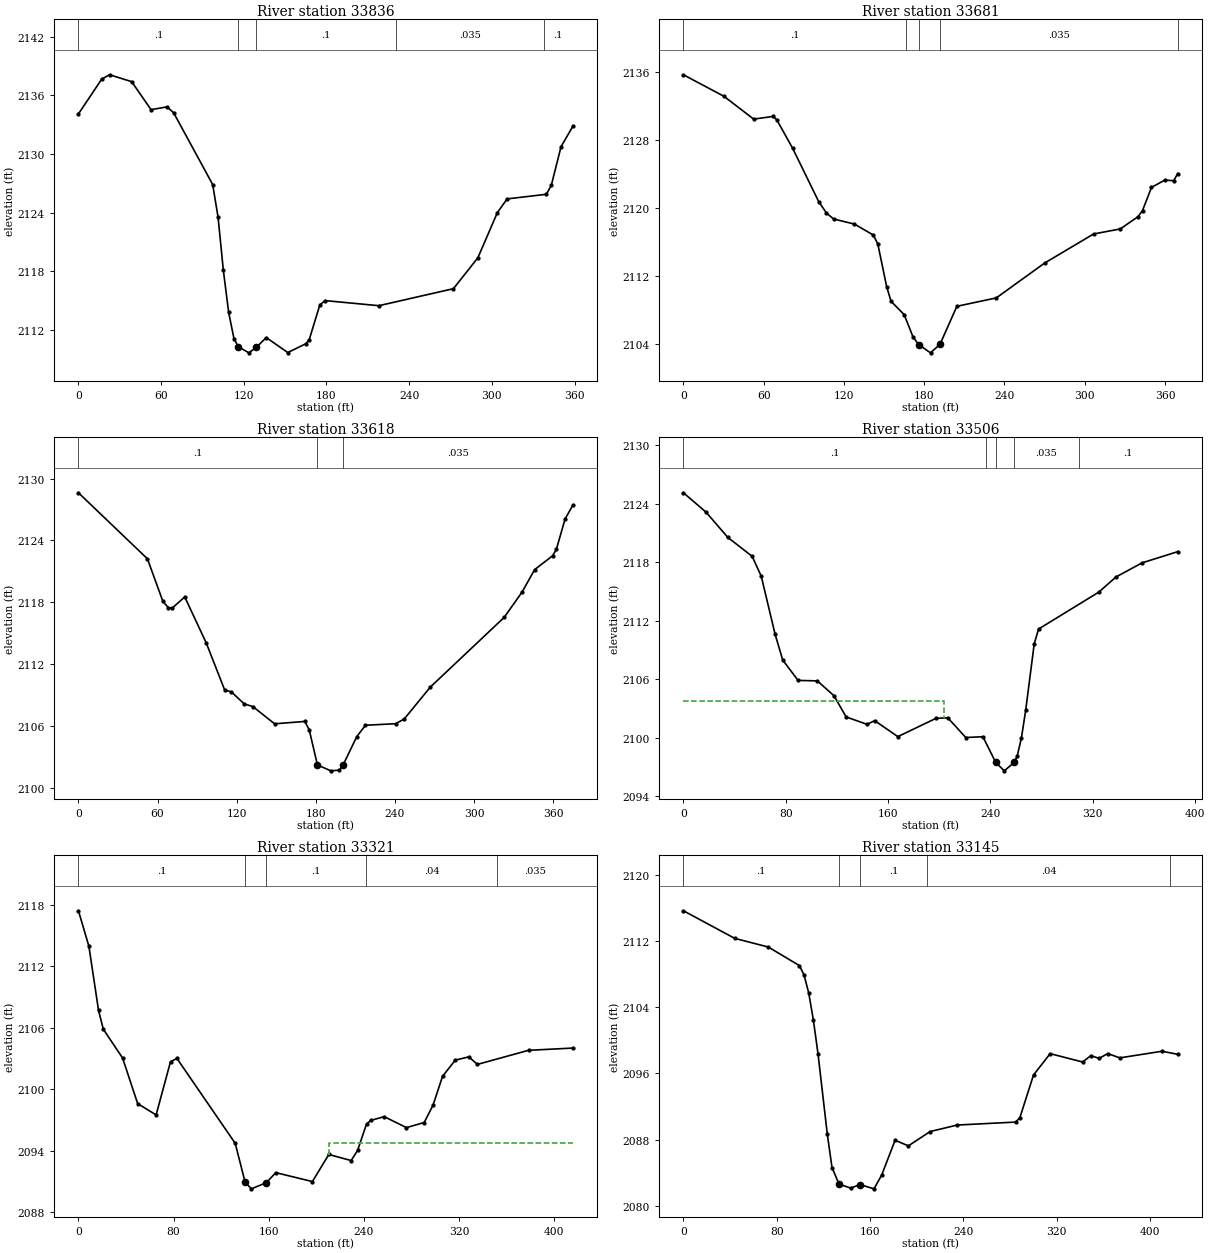
Type RM Length L Ch R = 1 ,33836   ,162.3,154.9,130.1
XS GIS Cut Line= 4
2041739.87980618282173.8657752442041693.53422915282212.635632952
2041582.00569504282387.3636697142041547.22641752282471.413590386
#Sta/Elev= 30
       0  2134.1    16.9 2137.66    22.6  2138.1    38.6  2137.4    52.7 2134.53
    64.3 2134.82    69.1 2134.21    97.4 2126.88   101.3 2123.56   105.1 2118.17
     109  2113.8   112.9 2111.09   116.12110.284   123.7 2109.67   129.12110.242
   136.3 2111.23   151.9  2109.7     165  2110.6   167.4 2110.99   175.2 2114.59
   179.1 2115.01     218 2114.49   272.1 2116.23   289.8 2119.38     304 2124.01
   311.1 2125.41   339.5 2125.88   343.1 2126.78   350.2 2130.75   358.7 2132.82
#Mann= 5 ,-1 , 0
       0      .1       0   116.1    .045       0   129.1      .1       0
  230.42    .035       0  337.71      .1       0
Bank Sta=116.1,129.1
XS Rating Curve= 0 ,0
Exp/Cntr(USF)=0,0
Exp/Cntr=0.3,0.1

Type RM Length L Ch R = 1 ,33681   ,64.1,63.7,64.4
XS GIS Cut Line= 4
2041611.85146256 282132.918532962041511.36287096282224.731850468
2041513.22167986282358.5660913922041496.33174771282456.688554334
#Sta/Elev= 30
       0 2135.73    30.3 2133.19    52.5  2130.5    67.1 2130.82    69.8 2130.41
    81.7 2127.04   101.1 2120.77   106.9 2119.43   112.2 2118.72   127.8 2118.12
     142 2116.82   145.3 2115.77   151.9 2110.75   155.2 2109.01     165 2107.44
   171.6 2104.82   175.82103.904   184.7 2102.93   191.82103.937   204.4 2108.42
   233.9 2109.41     270 2113.52   306.6 2116.95   326.6 2117.55   339.9    2119
   343.2 2119.72   349.9 2122.45   359.9 2123.31   366.5 2123.23   369.5 2124.08
#Mann= 5 ,-1 , 0
       0      .1       0  166.12    .035       0   175.8    .045       0
   191.8    .035       0  369.53      .1       0
Bank Sta=175.8,191.8
XS Rating Curve= 0 ,0
Exp/Cntr(USF)=0,0
Exp/Cntr=0.3,0.1

Type RM Length L Ch R = 1 ,33618   ,109.8,111.5,113.7
XS GIS Cut Line= 4
2041541.19490955282110.713868872 2041451.8809861282176.402819023
 2041451.8809861282352.9896646872041442.62670495282439.837533956
#Sta/Elev= 30
       0 2128.62    52.3 2122.22      64  2118.1    68.1 2117.48      71 2117.43
    80.6 2118.52    96.9 2114.06   110.9 2109.49   115.9 2109.32   125.7 2108.15
   132.3 2107.89   148.7 2106.22   171.7 2106.45     175 2105.63   181.22102.233
   191.4 2101.66   197.9 2101.73   200.72102.239     211 2104.97   217.6 2106.08
   240.6 2106.23   247.1  2106.7   266.8 2109.78   322.8 2116.54   336.3 2118.98
   345.9 2121.17   359.6 2122.52   362.4 2123.15     369 2126.09   374.8  2127.4
#Mann= 3 ,-1 , 0
       0      .1       0   181.2    .045       0   200.7    .035       0
Bank Sta=181.2,200.7
XS Rating Curve= 0 ,0
Exp/Cntr(USF)=0,0
Exp/Cntr=0.3,0.1

Type RM Length L Ch R = 1 ,33506   ,173.2,185,199.5
XS GIS Cut Line= 4
2041498.52281418282096.3619206352041358.94054102282187.555672434
2041331.05840749282326.9663400632041312.44199768282402.147995084
#Sta/Elev= 30
       0 2125.11    17.6 2123.13    34.7 2120.53    53.7 2118.59    60.8 2116.56
    71.6 2110.62    77.6 2107.95    89.6 2105.86   104.7 2105.81   117.7 2104.28
   127.2 2102.11   143.5 2101.35   149.5 2101.73   167.6 2100.09   197.3 2101.96
   206.6 2102.03   220.7    2100   234.1 2100.08   244.1 2097.44   250.8 2096.58
   258.6 2097.45   260.9  2098.1   264.2 2099.95   267.6 2102.86   274.2 2109.61
   277.6 2111.13   324.6 2114.91   338.1 2116.47   358.5 2117.92   386.4 2119.07
#Mann= 5 ,-1 , 0
       0      .1       0  236.73    .035       0   244.1    .045       0
   258.6    .035       0   308.9      .1       0
#XS Ineff= 2 , 0
           203.3 2103.72
Permanent Ineff=
       F       F
Bank Sta=244.1,258.6
XS Rating Curve= 0 ,0
Exp/Cntr(USF)=0,0
Exp/Cntr=0.3,0.1

Type RM Length L Ch R = 1 ,33321   ,183.8,176.2,141.5
XS GIS Cut Line= 5
 2041391.2530484282029.9174086232041332.91721639282111.344507463
2041238.11796241282139.2266409892041206.87012969282149.407564379
2041119.09099721282310.839595433
#Sta/Elev= 30
       0 2117.42     8.8 2113.95    16.9  2107.7    20.9 2105.87    37.1 2103.06
    49.8 2098.61    65.3 2097.51    77.4  2102.7    82.8 2103.02   131.8 2094.74
   140.12090.963   145.4  2090.3     1582090.903   165.9 2091.88   196.7 2091.01
   210.5 2093.65   229.3 2093.06   234.7 2094.05   242.2 2096.62   245.9 2096.98
   257.1 2097.34   275.8 2096.27   290.7 2096.77   298.2 2098.48   306.1 2101.27
   316.8 2102.85   328.1 2103.17   335.5 2102.44   378.4 2103.81   415.6 2104.03
#Mann= 5 ,-1 , 0
       0      .1       0   140.1    .045       0     158      .1       0
  241.85     .04       0  351.85    .035       0
#XS Ineff= 2 , 0
                          210.64         2094.73
Permanent Ineff=
       F       F
Bank Sta=140.1,158
XS Rating Curve= 0 ,0
Exp/Cntr(USF)=0,0
Exp/Cntr=0.3,0.1

Type RM Length L Ch R = 1 ,33145   ,140.8,135.2,122.3
XS GIS Cut Line= 4
2041243.62855516281891.7938305582041206.51821108281949.628133014
2041115.43657489282079.7447561342041036.09773331282259.359078041
#Sta/Elev= 30
       0 2115.68      44 2112.34    72.8 2111.29    99.4 2109.05   103.4 2107.92
   107.4 2105.76   111.4 2102.48   115.4 2098.38   123.4 2088.61   127.4 2084.61
   133.42082.605   143.4 2082.12   151.4 2082.55   163.4 2082.03     170  2083.7
   181.5 2087.91   192.9 2087.23   211.5 2088.96   234.7 2089.75   284.9 2090.11
   288.5 2090.64   300.2 2095.81   314.5 2098.39   342.3 2097.38   349.3 2098.14
   356.6 2097.82   363.8  2098.4   374.2 2097.88   410.4 2098.68   423.9 2098.31
#Mann= 5 ,-1 , 0
       0      .1       0   133.4    .045       0   151.4      .1       0
  208.72     .04       0  417.54    .035       0
Bank Sta=133.4,151.4
XS Rating Curve= 0 ,0
Exp/Cntr(USF)=0,0
Exp/Cntr=0.3,0.1

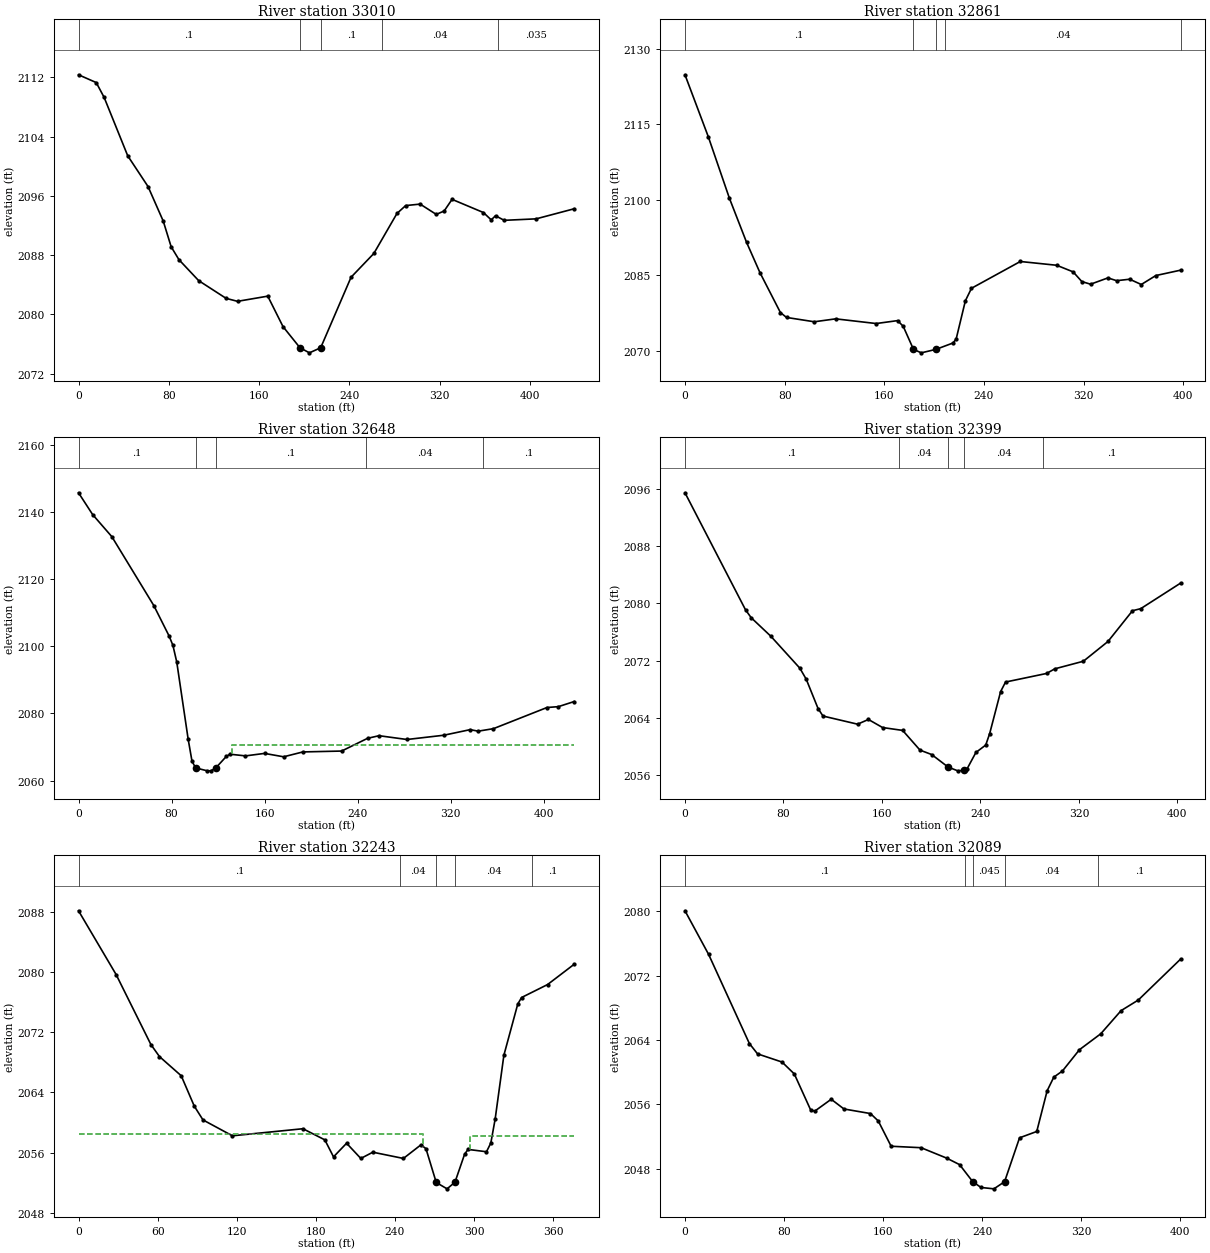
Type RM Length L Ch R = 1 ,33010   ,138.7,148.5,151
XS GIS Cut Line= 4
2041094.49993733281805.7627121312041050.37826333281927.322426193
2041020.63732091282066.7330938222040964.63559037282224.367594594
#Sta/Elev= 30
       0 2112.34    15.7 2111.29    22.7 2109.29    43.6 2101.41    61.6 2097.26
    75.1 2092.59    82.1 2089.13      89 2087.39   106.5 2084.56   130.8 2082.17
   140.9 2081.77   167.7 2082.47   181.2 2078.36   196.22075.512   204.6 2074.82
   214.62075.507   241.5 2085.02   261.7 2088.23   282.2 2093.63   289.9 2094.69
   302.7 2094.89     317  2093.5     324 2093.96     331 2095.53   358.8 2093.75
   365.7 2092.76   369.5 2093.32   377.2  2092.7   405.5  2092.9   439.2 2094.26
#Mann= 5 ,-1 , 0
       0      .1       0   196.2    .045       0   214.6      .1       0
  269.32     .04       0  371.87    .035       0
Bank Sta=196.2,214.6
XS Rating Curve= 0 ,0
Exp/Cntr(USF)=0,0
Exp/Cntr=0.3,0.1

Type RM Length L Ch R = 1 ,32861   ,218.5,212.9,207.1
XS GIS Cut Line= 4
2040978.15871267281766.4336216832040946.28496484 281880.85220365
2040877.50903547282029.5569157882040837.90088847282137.819184246
#Sta/Elev= 30
       0  2124.8    18.7 2112.51    35.7 2100.26    49.4 2091.55    60.2  2085.5
    76.6 2077.59    81.5 2076.61   103.8 2075.75     121 2076.33   153.5  2075.4
   170.7 2075.98   175.2 2074.85   183.42070.285   189.7 2069.58   201.52070.271
   215.2 2071.54   217.7 2072.33   225.1 2079.92     230  2082.4   269.2 2087.72
   298.4 2086.97   311.6 2085.66   318.6 2083.73   325.6 2083.21   339.5 2084.46
   346.5 2083.91     357  2084.2   366.3 2083.15     378 2084.93   397.9    2086
#Mann= 5 ,-1 , 0
       0      .1       0   183.4    .045       0   201.5      .1       0
  208.78     .04       0  397.89      .1       0
Bank Sta=183.4,201.5
XS Rating Curve= 0 ,0
Exp/Cntr(USF)=0,0
Exp/Cntr=0.3,0.1

Type RM Length L Ch R = 1 ,32648   ,257.4,249.1,240.9
XS GIS Cut Line= 4
2040738.66655311281716.4749040632040741.81598565281765.606051743
2040745.53360345281893.8638659622040738.78124803282142.575624117
#Sta/Elev= 30
       0 2145.66    12.2 2139.15    28.7 2132.58    64.8 2112.06    77.9 2103.03
    81.2 2100.23    84.5 2095.27    94.3 2072.32    97.6 2065.77   100.7 2063.76
   110.8 2062.88     114 2062.89   118.32063.837   127.2  2067.2   130.4 2067.83
   143.6 2067.33     160 2068.07   176.4 2067.06     193 2068.51   226.3 2068.77
   248.6 2072.56   258.5 2073.34   282.5 2072.21   314.2 2073.48   336.8 2075.14
   343.8 2074.69   356.9 2075.44   402.9 2081.73   412.7 2081.99   426.3 2083.51
#Mann= 5 ,-1 , 0
       0      .1       0   100.7    .045       0   118.3      .1       0
  247.54     .04       0  347.54      .1       0
#XS Ineff= 2 , 0
                          131.93         2070.51
Permanent Ineff=
       F       F
Bank Sta=100.7,118.3
XS Rating Curve= 0 ,0
Exp/Cntr(USF)=0,0
Exp/Cntr=0.3,0.1

Type RM Length L Ch R = 1 ,32399   ,151.8,156.3,162.2
XS GIS Cut Line= 4
2040518.17189014 281802.96494785 2040548.2825672281902.245185122
2040649.84506723282047.2104628982040669.08171856282167.487727478
#Sta/Elev= 30
       0 2095.48    49.2 2079.09    53.8 2077.99    69.8 2075.39    93.3 2070.93
    98.5 2069.38   108.1 2065.28   112.1 2064.23   140.2 2063.09     149 2063.75
   160.5 2062.62   176.8 2062.22   190.9 2059.46   200.4 2058.84   213.72057.091
   221.6 2056.56   226.52056.631   229.1 2056.83   236.3 2059.13   244.3 2060.17
   247.5 2061.78   256.4 2067.66   260.4 2068.99   293.7 2070.19   300.4 2070.84
   323.6  2071.9   343.6 2074.67   363.5 2078.97   370.2 2079.26   402.6 2082.84
#Mann= 5 ,-1 , 0
       0      .1       0  173.75     .04       0   213.7    .045       0
   226.5     .04       0  290.75      .1       0
Bank Sta=213.7,226.5
XS Rating Curve= 0 ,0
Exp/Cntr(USF)=0,0
Exp/Cntr=0.3,0.1

Type RM Length L Ch R = 1 ,32243   ,148.1,154.6,160.9
XS GIS Cut Line= 4
2040466.85561824281818.3719800762040479.72393051281971.933839834
2040507.60606403282168.9675834172040510.67282081282191.530151123
#Sta/Elev= 30
       0 2088.13    28.5 2079.66    54.9 2070.35    61.4 2068.75    77.9  2066.2
    87.8 2062.16    94.4 2060.33   116.7 2058.22   170.2 2059.16   186.8 2057.68
   193.4 2055.42   203.3 2057.23   214.1 2055.21   223.2 2056.04   246.4 2055.21
   259.7 2057.02   263.5 2056.51   271.32052.014   279.5 2051.17   285.5 2052.05
   292.8 2055.77   295.4 2056.41   309.4  2056.1   312.7 2057.26     316 2060.47
   322.6 2068.93   333.1 2075.72     336  2076.6   355.7 2078.32   375.9 2081.02
#Mann= 5 ,-1 , 0
       0      .1       0   244.1     .04       0   271.3    .045       0
   285.5     .04       0   344.1      .1       0
#XS Ineff= 2 , 0
          261.47 2058.41  296.85         2058.14
Permanent Ineff=
       F       F
Bank Sta=271.3,285.5
XS Rating Curve= 0 ,0
Exp/Cntr(USF)=0,0
Exp/Cntr=0.3,0.1

Type RM Length L Ch R = 1 ,32089   ,130.5,121.8,120.5
XS GIS Cut Line= 4
2040400.20952876281837.6734063932040388.64229432281953.345750817
2040319.86636496282159.6735389082040318.37688027282226.203854948
#Sta/Elev= 30
       0 2080.08    19.1 2074.65      52 2063.56    58.6 2062.27    78.4 2061.25
    88.3 2059.77   101.5 2055.29   104.8 2055.14   118.1 2056.62   128.4 2055.41
   149.8 2054.84   156.1 2053.92   166.5 2050.77   190.7 2050.59   211.4 2049.29
   221.8 2048.48   232.4 2046.36   239.1 2045.64   249.5 2045.47   258.12046.354
   270.2 2051.82   284.1 2052.61   292.5 2057.68   297.9 2059.38   304.8 2060.13
   318.6 2062.79   335.8 2064.77   352.2 2067.65   366.1 2068.97   400.3 2074.07
#Mann= 5 ,-1 , 0
       0      .1       0  226.25     .04       0   232.4    .045       0
   258.1     .04       0  333.74      .1       0
Bank Sta=232.4,258.1
XS Rating Curve= 0 ,0
Exp/Cntr(USF)=0,0
Exp/Cntr=0.3,0.1

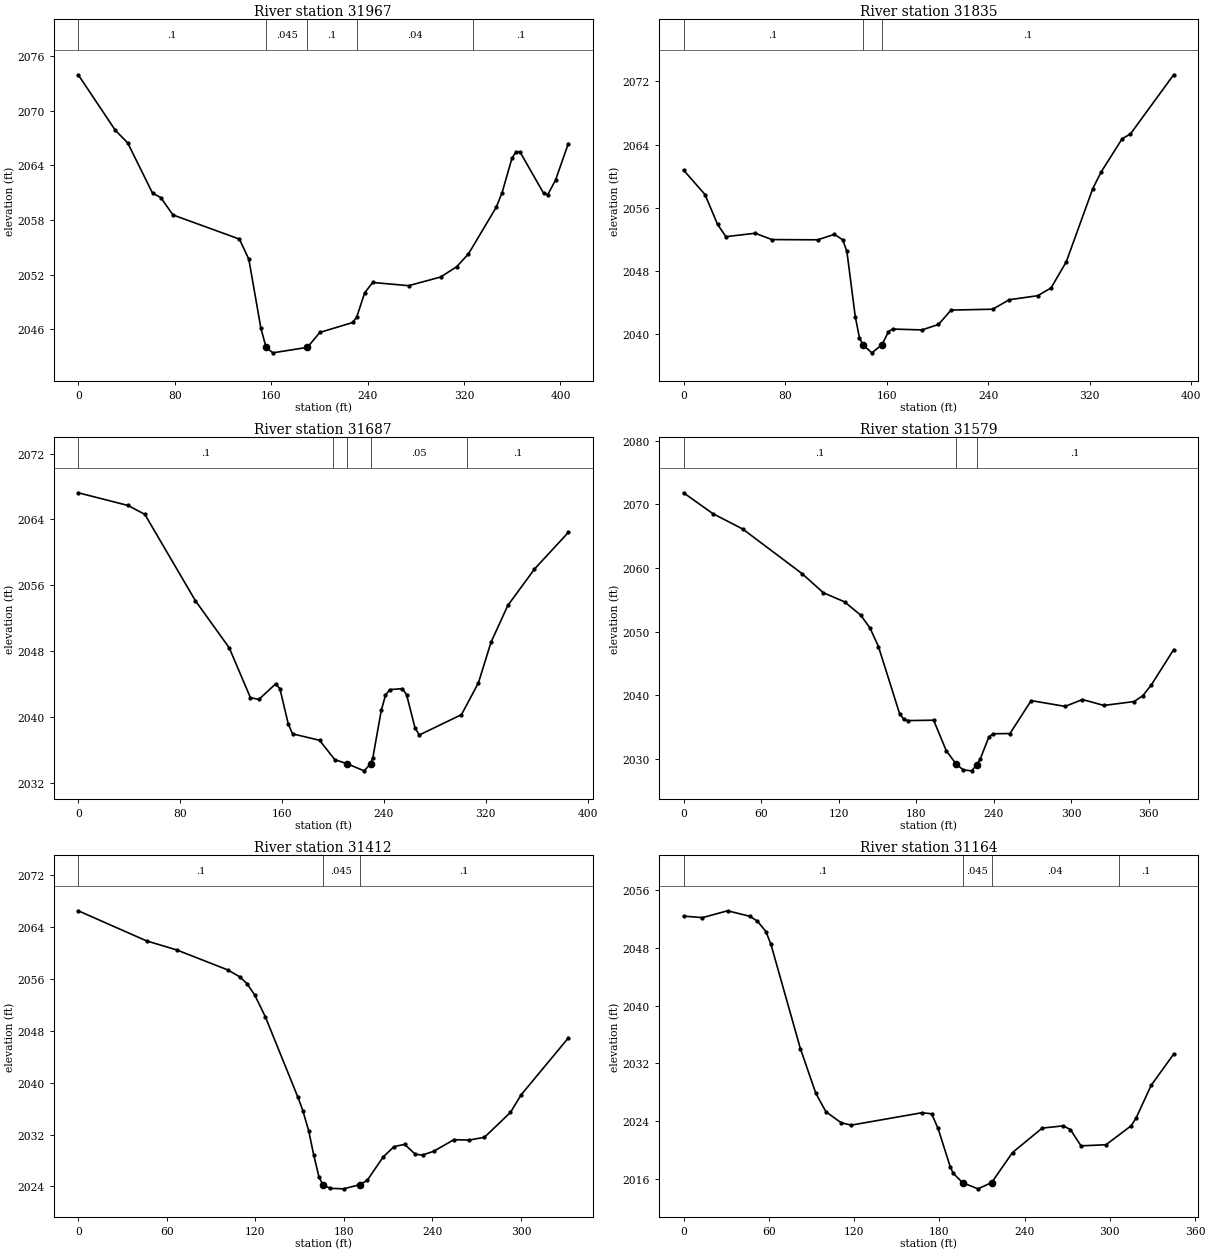
Type RM Length L Ch R = 1 ,31967   ,135,132.1,129.4
XS GIS Cut Line= 4
2040281.79441713281837.218585438 2040260.3844801281905.016719372
2040226.92591987282139.2266409892040222.22786424282237.885809314
#Sta/Elev= 30
       0 2073.94    30.7 2067.86      41 2066.47    61.6 2060.96    68.5 2060.46
    78.6 2058.56   133.7 2055.91   141.5  2053.7   151.5 2046.13   155.82044.042
   161.4 2043.43   190.12044.033   200.4 2045.67   227.7 2046.76     231 2047.36
   237.6 2050.02   244.3 2051.15   274.1  2050.8   300.6 2051.75   313.8 2052.87
   323.7 2054.29   346.7  2059.4   351.6 2061.02   359.8 2064.81   363.1 2065.47
   366.4 2065.48     386 2060.94   389.4 2060.77   395.9 2062.39   406.5 2066.39
#Mann= 5 ,-1 , 0
       0      .1       0   155.8    .045       0   190.1      .1       0
   231.1     .04       0  327.69      .1       0
Bank Sta=155.8,190.1
XS Rating Curve= 0 ,0
Exp/Cntr(USF)=0,0
Exp/Cntr=0.3,0.1

Type RM Length L Ch R = 1 ,31835   ,148,148,146.6
XS GIS Cut Line= 4
2040118.33943235281849.7415049462040111.67976796281905.016719372
2040119.11500357282137.3678320872040128.06162919282234.967384284
#Sta/Elev= 30
       0 2060.77    16.9 2057.68    26.8  2053.9    33.4 2052.35    56.5 2052.78
    69.6 2051.98   105.7 2051.95   118.9 2052.64   125.4 2051.95   128.7 2050.49
   135.3 2042.24   138.6 2039.57   141.3 2038.67   148.4 2037.65   156.32038.668
   161.5 2040.32   164.8 2040.66   187.8 2040.55   200.9 2041.24   210.8 2043.06
   243.6 2043.17   256.7 2044.37   279.1 2044.88   289.6 2045.86   301.6 2049.17
   322.5 2058.44   329.1 2060.54   345.6 2064.73   352.2 2065.35   386.2 2072.83
#Mann= 3 ,-1 , 0
       0      .1       0   141.3    .045       0   156.3      .1       0
Bank Sta=141.3,156.3
XS Rating Curve= 0 ,0
Exp/Cntr(USF)=0,0
Exp/Cntr=0.3,0.1

Type RM Length L Ch R = 1 ,31687   ,106.7,108,109.2
XS GIS Cut Line= 4
2039977.39352204281860.3157882562039972.26910034281919.887190586
2040005.72766057282142.9442587922040019.03321274 282241.56188074
#Sta/Elev= 30
       0 2067.24    39.1  2065.7    52.3 2064.62      92 2054.15   118.6 2048.42
   135.2 2042.39   141.8 2042.16   155.1 2044.06   158.4 2043.46     165 2039.16
   168.3 2037.99   189.5 2037.21   201.5 2034.86   210.92034.374   224.6  2033.5
   229.62034.368   231.4 2035.11     238 2040.84   241.3 2042.66   244.6 2043.36
   254.6 2043.47   257.9 2042.73   264.5  2038.7   267.9 2037.85     301 2040.32
   314.3 2044.18   324.2 2049.11   337.4 2053.57   358.3 2057.98   384.9 2062.43
#Mann= 5 ,-1 , 0
       0      .1       0  199.79     .05       0   210.9    .045       0
   229.6     .05       0  305.34      .1       0
Bank Sta=210.9,229.6
XS Rating Curve= 0 ,0
Exp/Cntr(USF)=0,0
Exp/Cntr=0.3,0.1

Type RM Length L Ch R = 1 ,31579   ,170.4,166.4,160
XS GIS Cut Line= 4
2039888.62548737281870.0960506852039883.04627305281951.486941915
2039894.19912646282163.3911567112039909.00064179282247.759794086
#Sta/Elev= 30
       0 2071.83    22.7 2068.55    45.9 2066.12    91.7 2059.13   108.2 2056.12
   124.6 2054.69   137.1  2052.6   144.3 2050.59   150.9 2047.65   167.3 2037.07
   170.6  2036.2   173.9 2036.02   193.6 2036.08   203.4 2031.27   211.22029.145
   216.6 2028.26   223.1 2028.12     2272029.085   229.7 2029.98   236.3 2033.42
   239.6 2033.95   252.7 2033.98   269.1 2039.16   295.4 2038.25   308.8 2039.33
   325.4  2038.4   348.7 2039.01   355.5 2039.92   362.1 2041.62   379.4 2047.17
#Mann= 3 ,-1 , 0
       0      .1       0   211.2    .045       0     227      .1       0
Bank Sta=211.2,227
XS Rating Curve= 0 ,0
Exp/Cntr(USF)=0,0
Exp/Cntr=0.3,0.1

Type RM Length L Ch R = 1 ,31412   ,247,247.8,247.8
XS GIS Cut Line= 4
2039678.19724459281982.7224978552039704.60061849282074.168329429
2039777.09416566 282226.590659372039801.21249256282290.287779125
#Sta/Elev= 30
       0 2066.48    46.3 2061.84    66.8 2060.44   101.3 2057.37   109.4 2056.31
   114.3 2055.26   119.5 2053.55   126.8 2050.14   148.8 2037.78   152.2 2035.69
   156.2 2032.54   159.5 2028.92   163.1 2025.49   165.82024.232   170.9 2023.71
   179.8 2023.63   190.6 2024.26   195.8 2024.93   206.7 2028.56     214 2030.14
   221.2 2030.48   228.5 2028.95   233.3 2028.84   240.9 2029.42   254.6 2031.21
   264.8 2031.14   275.3 2031.58   292.9 2035.41   300.1 2038.11   332.1 2046.88
#Mann= 3 ,-1 , 0
       0      .1       0   165.8    .045       0   190.6      .1       0
Bank Sta=165.8,190.6
XS Rating Curve= 0 ,0
Exp/Cntr(USF)=0,0
Exp/Cntr=0.3,0.1

Type RM Length L Ch R = 1 ,31164   ,175.6,178.8,181.1
XS GIS Cut Line= 4
2039452.30167734282076.8390908662039475.96712358282152.238303301
2039559.61352415282341.8368112762039581.59777975282396.150854529
#Sta/Elev= 30
       0 2052.41    13.3  2052.2      31 2053.15    46.7 2052.38      52 2051.71
      58 2050.26    61.5 2048.49    82.2 2034.06    93.1 2027.84   100.2 2025.29
   110.9 2023.77     118 2023.44   167.8 2025.16   174.6 2025.01   179.1 2022.99
   187.7 2017.65   189.8 2016.76   196.52015.449   207.2 2014.61   216.82015.475
   231.5 2019.64   252.4 2023.03   267.3 2023.34   272.3 2022.81   279.7 2020.57
   297.3 2020.72     315 2023.35   318.5 2024.43   329.1 2028.97   344.9 2033.28
#Mann= 4 ,-1 , 0
       0      .1       0   196.5    .045       0   216.8     .04       0
  306.26      .1       0
Bank Sta=196.5,216.8
XS Rating Curve= 0 ,0
Exp/Cntr(USF)=0,0
Exp/Cntr=0.3,0.1

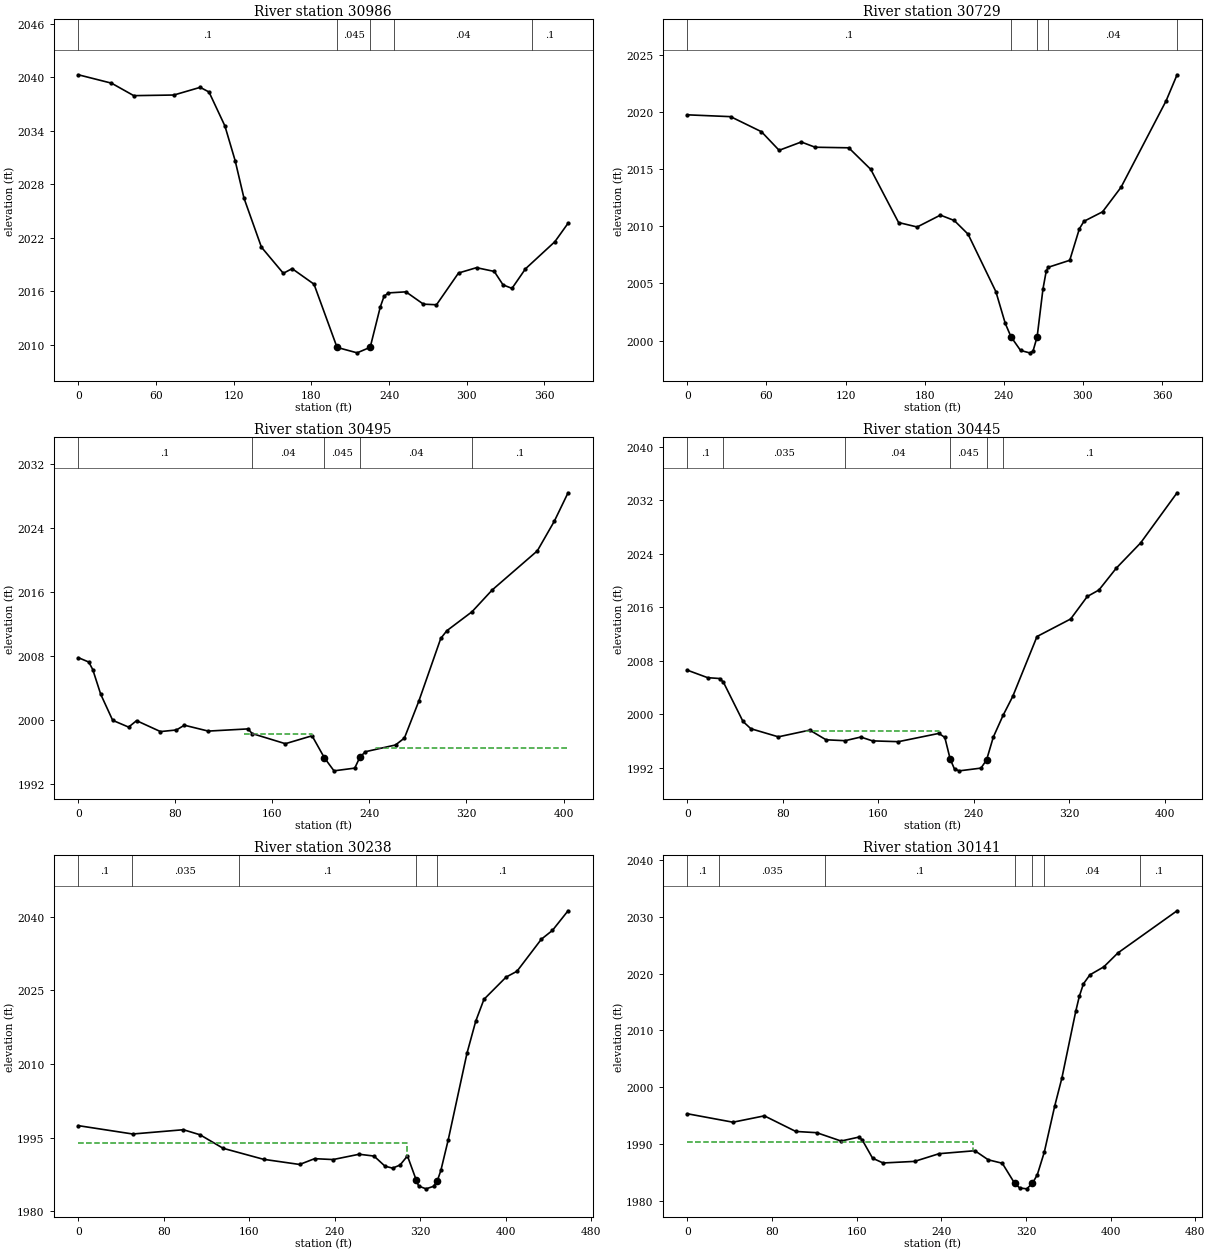
Type RM Length L Ch R = 1 ,30986   ,258.4,256.4,253.7
XS GIS Cut Line= 4
 2039306.6027491282120.9717214912039329.12122034282191.273290237
2039381.16786959282401.3186961312039408.07791427282485.124263834
#Sta/Elev= 30
       0 2040.25    25.6 2039.31    42.8 2037.91    73.8 2037.98    94.1 2038.84
   100.9 2038.32   113.2 2034.51   121.1 2030.62   127.9 2026.43   141.4 2020.92
   158.3 2017.99   165.1 2018.51     182 2016.77   199.8 2009.68   215.3 2009.07
   225.42009.693   233.2 2014.22   236.1 2015.41   239.4 2015.79     253 2015.91
   266.5 2014.53   276.6 2014.46   293.6 2018.02   307.5 2018.62   321.2  2018.2
     328 2016.69   334.9  2016.3   345.3 2018.49     368 2021.53   378.2  2023.6
#Mann= 5 ,-1 , 0
       0      .1       0   199.8    .045       0   225.4      .1       0
  243.82     .04       0  350.22      .1       0
Bank Sta=199.8,225.4
XS Rating Curve= 0 ,0
Exp/Cntr(USF)=0,0
Exp/Cntr=0.3,0.1

Type RM Length L Ch R = 1 ,30729   ,253.8,234,213.5
XS GIS Cut Line= 4
2039077.16654552282198.4187386142039093.05248982 282280.49611752
 2039172.9812726282488.6827145122039195.98770013282549.225944861
#Sta/Elev= 30
       0 2019.78    32.8 2019.62    56.2  2018.3    69.6 2016.67    86.4  2017.4
    96.9 2016.94   122.4 2016.89   139.1    2015   160.2 2010.34   174.3 2009.95
   191.9 2010.99   202.4 2010.52   212.9 2009.32     234 2004.28   241.1  2001.5
   245.52000.316   252.7 1999.13   259.5 1998.92   262.1 1999.05   265.32000.334
   269.7 2004.52   272.2  2006.1   273.7 2006.42     290 2007.03   297.3 2009.79
   300.8 2010.45   314.9 2011.28   328.9 2013.43   363.1 2021.01   371.4 2023.29
#Mann= 5 ,-1 , 0
       0      .1       0   245.5    .045       0   265.3      .1       0
   273.7     .04       0   371.4      .1       0
Bank Sta=245.5,265.3
XS Rating Curve= 0 ,0
Exp/Cntr(USF)=0,0
Exp/Cntr=0.5,0.3

Type RM Length L Ch R = 1 ,30495   ,44.7,50.4,55.7
XS GIS Cut Line= 4
2038878.59456284282317.1931316172038885.15697494282477.297386184
2039011.53531645282540.5919848932039074.13884251282621.314055055
#Sta/Elev= 30
       02007.798   8.6052007.251  11.8882006.309  18.4552003.224  28.3061999.971
   41.441999.124  48.0081999.928  67.7151998.563  80.8431998.766  87.4111999.359
 107.1121998.625 139.948  1998.9 143.2321998.321 170.671 1997.05 192.6871998.038
 202.8831995.281 210.758 1993.66 227.8721993.999 232.1881995.385 236.7191996.051
 261.4941996.891  268.821997.757  280.752002.385 298.7732010.195 303.7752011.162
 324.534 2013.53 341.1422016.248 378.3992021.139  392.432024.849 403.7342028.395
#Mann= 5 ,-1 , 0
       0      .1       0 143.232     .04       0 202.883    .045       0
 232.188     .04       0 324.534      .1       0
#XS Ineff= 3 ,-1
  136.57   192.5 1998.32  194.16  197.31 1996.56     245 403.734 1996.55
Permanent Ineff=
       F       F       F
Bank Sta=202.883,232.188
XS Rating Curve= 0 ,0
Exp/Cntr(USF)=0,0
Exp/Cntr=0.5,0.3

Type RM Length L Ch R = 1 ,30445   ,195.5,206.6,218.8
XS GIS Cut Line= 5
2038836.77929973 282325.229936422038848.89615369282501.610352595
2038879.42780825282521.5682194982038969.75354685282587.596475689
2039027.43934251282649.929623282
#Sta/Elev= 30
       02006.579  17.0052005.456  26.9552005.331  30.1592004.796  46.6021998.899
  53.1791997.811   76.211996.594 102.5071997.601 116.193 1996.15 132.1041996.016
 145.2591996.563 155.1241995.988 176.7961995.869 210.7031997.109 215.6671996.503
 220.1191993.284 223.7951991.748 227.859  1991.5 245.9441991.909 250.6391993.135
 256.3071996.567 264.4351999.802 272.5632002.652 292.8822011.621 321.0722014.248
 334.9992017.617  344.762018.589 359.2512021.855   379.72025.647   410.22033.153
#Mann= 6 ,-1 , 0
       0      .1       0  30.159    .035       0 132.104     .04       0
 220.119    .045       0 250.639     .04       0 264.435      .1       0
#XS Ineff= 3 ,-1
   98.95  210.64 1997.46  211.73  215.22 1994.01     255   410.2    1994
Permanent Ineff=
       F       F       F
Bank Sta=220.119,250.639
XS Rating Curve= 0 ,0
Exp/Cntr(USF)=0,0
Exp/Cntr=0.5,0.3

Type RM Length L Ch R = 1 ,30238   ,94,96.9,99.6
XS GIS Cut Line= 3
2038625.06529792282312.5504730432038670.48517432282492.310828916
2038761.30061919282749.621256035
#Sta/Elev= 30
       0 1997.45    50.9 1995.75    98.3 1996.62   113.9 1995.59   135.5 1992.84
   173.3  1990.6   207.1 1989.55   221.1 1990.73   238.4 1990.55   262.8 1991.63
   276.7 1991.26     287  1989.2   294.1  1988.8   301.1 1989.44     308 1991.29
   316.3 1986.33   318.5 1985.15   325.4 1984.59   332.4  1985.1     336 1986.26
   339.3 1988.36   346.2  1994.6   363.7 2012.18   371.9 2018.71   379.6 2023.16
   400.3 2027.68   410.5 2028.87   433.3 2035.39   443.7 2037.19   458.3 2041.18
#Mann= 5 ,-1 , 0
       0      .1       0      50    .035       0     150      .1       0
   316.3    .045       0     336      .1       0
#XS Ineff= 2 , 0
          307.35 1993.88
Permanent Ineff=
       F       F
Bank Sta=316.3,336
XS Rating Curve= 0 ,0
Exp/Cntr(USF)=0,0
Exp/Cntr=0.3,0.1

Type RM Length L Ch R = 1 ,30141   ,189.8,191.9,195.7
XS GIS Cut Line= 4
2038583.04711522282322.3120151182038600.46813087282488.682714512
 2038633.9266911282726.6102539322038646.56409079282780.529825964
#Sta/Elev= 30
       0  1995.3    43.1 1993.81    72.8 1994.93   102.5 1992.18   122.3 1991.96
   145.3 1990.49   161.8 1991.17   165.1 1990.75   175.1 1987.46     185 1986.62
   214.8  1986.9     238 1988.26   271.8 1988.78   284.4 1987.18   297.7 1986.57
   309.41983.027   314.2 1982.21   320.8 1982.06   326.21983.036   330.8 1984.55
   337.4 1988.53   347.3  1996.7     354 2001.57   367.2 2013.42   370.5    2016
   374.4 2018.21   380.5 2019.79   393.7 2021.21     407 2023.66   462.9 2031.09
#Mann= 7 ,-1 , 0
       0      .1       0      30    .035       0     130      .1       0
   309.4    .045       0   326.2      .1       0  337.28     .04       0
  427.55      .1       0
#XS Ineff= 2 , 0
          269.87 1990.27
Permanent Ineff=
       F       F
Bank Sta=309.4,326.2
XS Rating Curve= 0 ,0
Exp/Cntr(USF)=0,0
Exp/Cntr=0.3,0.1