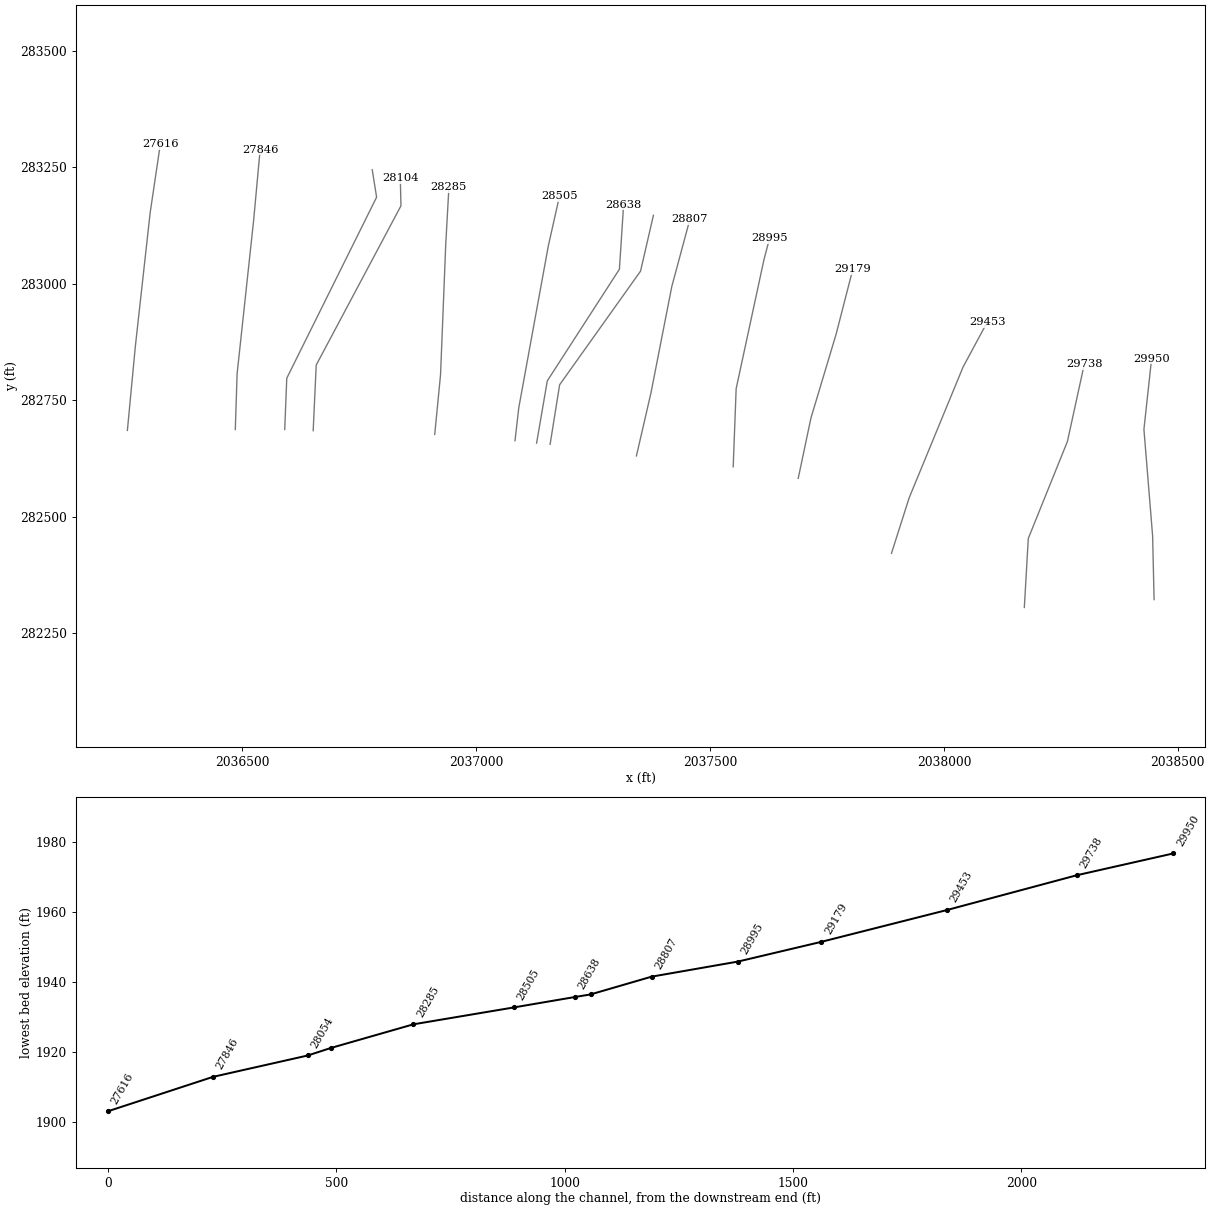
HEC-RAS study LICKCK1.prj: LICKCK1

--- LICKCK1.g01 (geometry) --- (continued)

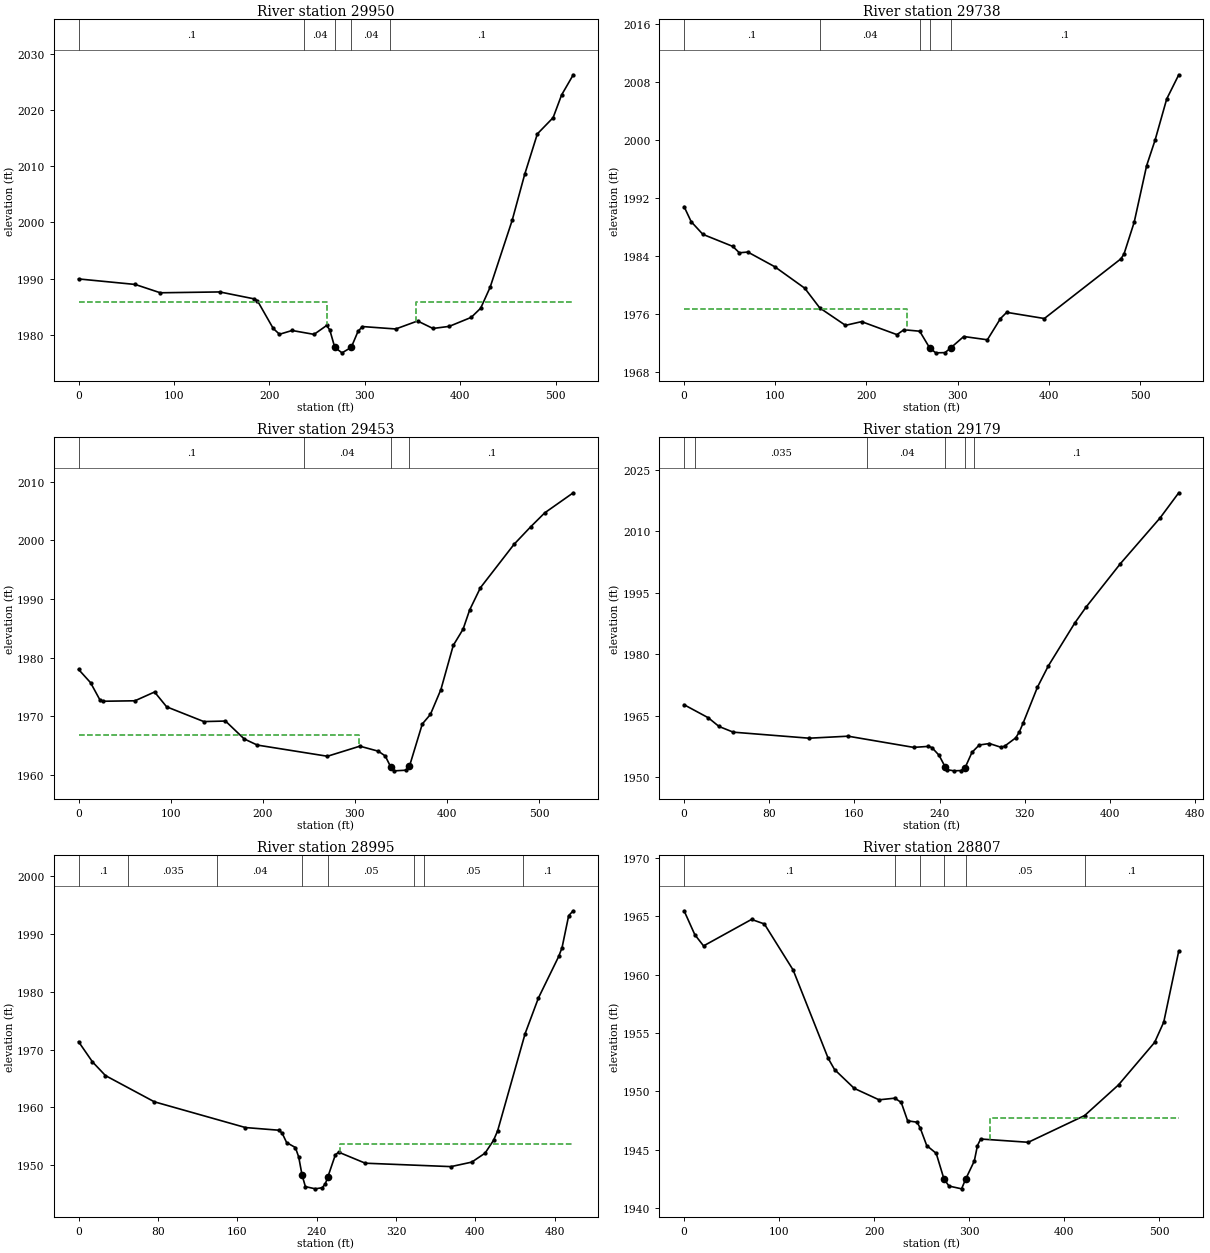
Type RM Length L Ch R = 1 ,29950   ,217.6,211.2,202.3
XS GIS Cut Line= 4
2038449.31081878282322.2743515932038446.18699202282458.941772085
2038427.59890301282687.5752669962038443.99534924282838.927078402
#Sta/Elev= 30
       0 1989.97    59.3 1988.99    85.6 1987.51   147.9 1987.66   184.2 1986.42
   187.4 1986.09   203.9 1981.18   210.5 1980.14   223.7 1980.81   246.7 1980.12
   259.9  1981.7   263.2 1980.91   268.41977.817     276 1976.84   285.7 1977.81
   292.8 1980.66   297.4 1981.51   332.3 1981.08   355.2  1982.5   371.3 1981.17
   388.3 1981.54   411.4 1983.14   421.3 1984.77   431.2 1988.49   454.3 2000.38
   467.4 2008.54   480.7 2015.74   497.2 2018.62   506.1 2022.66   518.3 2026.24
#Mann= 5 ,-1 , 0
       0      .1       0   236.7     .04       0   268.4    .045       0
   285.7     .04       0   326.7      .1       0
#XS Ineff= 2 , 0
           259.9 1985.86  353.52         1985.86
Permanent Ineff=
       F       F
Bank Sta=268.4,285.7
XS Rating Curve= 0 ,0
Exp/Cntr(USF)=0,0
Exp/Cntr=0.3,0.1

Type RM Length L Ch R = 1 ,29738   ,283.7,285.1,282.8
XS GIS Cut Line= 4
2038171.91403614282305.2578939182038180.37731908 282453.36534538
2038264.02371966282661.5519423722038300.14913858282827.503085537
#Sta/Elev= 30
       0 1990.77     7.8 1988.69    20.6 1986.95    53.4 1985.29    60.6 1984.41
    69.9 1984.51    99.4 1982.49   132.3 1979.53   148.8 1976.81     177 1974.41
   194.7 1974.92   233.4 1973.13   241.1  1973.8   258.4  1973.6   269.41971.285
     276 1970.62   286.2 1970.65   292.31971.293   306.7 1972.87   332.6 1972.42
     347 1975.35   353.8  1976.2   395.1 1975.35     479 1983.57   482.4 1984.22
   493.6 1988.61   507.3 1996.43   516.5 1999.92   529.3 2005.61   542.5 2008.94
#Mann= 5 ,-1 , 0
       0      .1       0   148.8     .04       0   258.4      .1       0
   269.4    .045       0   292.3      .1       0
#XS Ineff= 2 , 0
           244.8 1976.71
Permanent Ineff=
       F       F
Bank Sta=269.4,292.3
XS Rating Curve= 0 ,0
Exp/Cntr(USF)=0,0
Exp/Cntr=0.3,0.1

Type RM Length L Ch R = 1 ,29453   ,272.5,274.6,275.5
XS GIS Cut Line= 4
2037887.91025835282421.6673276842037925.72049954 282540.72936376
2038040.96665145 282821.409507922038092.37993726 282917.26478655
#Sta/Elev= 30
       0 1977.97      13 1975.71    23.3 1972.73    26.8 1972.54    61.2 1972.62
    82.5 1974.12    95.6 1971.59     136 1969.07   159.5 1969.16   179.8 1966.11
     194 1965.06   270.2 1963.15   305.4 1964.87   325.5 1964.01     333 1963.19
   338.7 1961.39     343 1960.66   355.6 1960.77   359.21961.416   373.2 1968.66
     382 1970.29   393.4 1974.54   406.8 1982.07   417.5 1984.85   424.6 1988.12
   436.3 1991.92   472.8 1999.33   490.8 2002.31   506.1  2004.7   537.1 2008.13
#Mann= 4 ,-1 , 0
       0      .1       0  244.92     .04       0   338.7    .045       0
   359.2      .1       0
#XS Ineff= 2 , 0
          304.95 1966.78
Permanent Ineff=
       F       F
Bank Sta=338.7,359.2
XS Rating Curve= 0 ,0
Exp/Cntr(USF)=0,0
Exp/Cntr=0.3,0.1

Type RM Length L Ch R = 1 ,29179   ,182.1,183.1,183.2
XS GIS Cut Line= 4
2037688.50995692282582.3819887672037715.67509365282711.739782718
 2037769.5805518282892.044246185 2037805.3782986283031.770935333
#Sta/Elev= 30
       0 1967.71    22.8 1964.52    32.8 1962.41    46.2 1961.02   117.4 1959.55
     154 1960.04   215.6 1957.31   229.3 1957.55   232.7 1957.28   239.4 1955.41
   245.51952.412   247.3 1951.87   253.3 1951.59   260.1 1951.66     2641952.401
   270.4  1956.1   277.2 1957.89   286.8 1958.25   297.8 1957.32   301.2 1957.63
   311.5 1959.64   314.9  1961.1   318.5 1963.28   331.9    1972   342.1 1977.18
   366.9 1987.62   377.4 1991.47   409.8 2002.12   447.1 2013.28   464.6  2019.4
#Mann= 6 ,-1 , 0
       0     .06       0      10    .035       0  172.18     .04       0
   245.5    .045       0     264     .04       0  272.18      .1       0
Bank Sta=245.5,264
XS Rating Curve= 0 ,0
Exp/Cntr(USF)=0,0
Exp/Cntr=0.3,0.1

Type RM Length L Ch R = 1 ,28995   ,187.7,188.8,186.5
XS GIS Cut Line= 4
2037549.48342147282607.085459728 2037555.8175281282774.939285377
2037615.29941296283051.9018117332037627.29068078283097.868338378
#Sta/Elev= 30
       0 1971.36      14 1967.88    27.1 1965.51    76.4 1960.98   168.3 1956.53
   201.9 1956.07   205.2 1955.58   209.8 1953.93   218.6 1953.08     222 1951.42
   225.31948.346   228.7 1946.32   238.8 1945.94   245.7 1946.14   248.8 1946.82
   251.2 1947.93   258.9 1951.81   262.2 1952.28   289.1 1950.37   375.5 1949.78
   396.5 1950.56   409.9 1952.11   418.4 1954.32   422.5 1955.94   450.3 1972.78
   463.7 1978.93   484.1 1986.09   487.5 1987.62   494.2 1993.16   498.8 1993.99
#Mann= 8 ,-1 , 0
       0      .1       0      50    .035       0     140     .04       0
   225.3    .045       0   251.2     .05       0  337.97      .1       0
  347.97     .05       0  447.97      .1       0
#XS Ineff= 2 , 0
                          263.12         1953.63
Permanent Ineff=
       F       F
Bank Sta=225.3,251.2
XS Rating Curve= 0 ,0
Exp/Cntr(USF)=0,0
Exp/Cntr=0.3,0.1

Type RM Length L Ch R = 1 ,28807   ,139.5,133.9,127.6
XS GIS Cut Line= 4
 2037342.5943725282630.5708649412037373.65425573282765.645240868
2037418.26566937 282994.278735782037456.91119391283138.321145434
#Sta/Elev= 30
       0 1965.47    11.3 1963.42    20.5 1962.46      71 1964.73    84.5 1964.34
   114.8 1960.39   151.7 1952.82   158.4 1951.86   179.1 1950.25   205.2 1949.27
   221.9 1949.41   228.6 1949.04   235.3 1947.47   245.3 1947.35   248.7 1946.82
   255.4 1945.35   265.4 1944.68   273.51942.499   278.8 1941.88   292.1 1941.64
   296.31942.457   305.5 1944.03   308.8 1945.35   312.2 1945.91   362.3 1945.63
   421.6 1947.92   457.3 1950.55   495.3 1954.19   504.9 1955.93   520.7 1962.02
#Mann= 6 ,-1 , 0
       0      .1       0   221.9     .04       0   248.7     .05       0
   273.5    .045       0   296.3     .05       0   421.6      .1       0
#XS Ineff= 2 , 0
                          322.04         1947.73
Permanent Ineff=
       F       F
Bank Sta=273.5,296.3
XS Rating Curve= 0 ,0
Exp/Cntr(USF)=0,0
Exp/Cntr=0.5,0.3

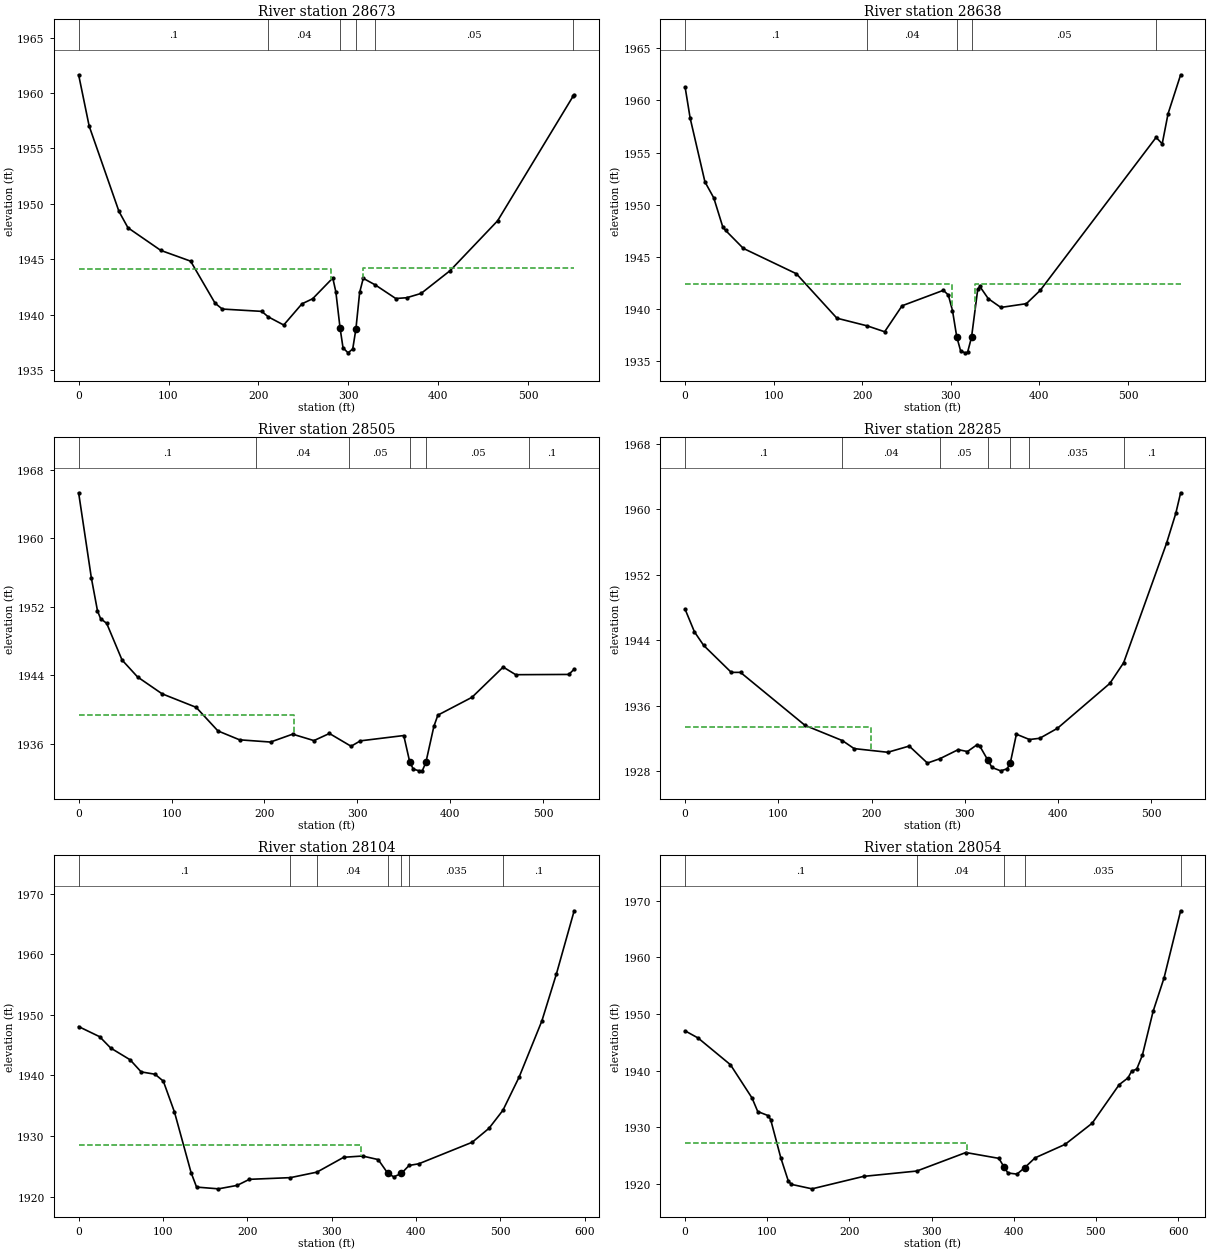
Type RM Length L Ch R = 1 ,28673   ,33.9,34.8,35.3
XS GIS Cut Line= 4
2037158.05458775282655.4535103282037178.44582045282783.286969498
2037351.36248711283027.0369694982037378.94718917283146.975936988
#Sta/Elev= 30
       0 1961.64    11.7 1957.02    44.9 1949.31    54.9 1947.84    91.4  1945.8
   124.6 1944.83   151.8 1941.04   159.8 1940.51   203.8  1940.3   210.9 1939.81
   228.2 1939.07   248.5 1940.98   260.4 1941.44   282.8 1943.31   286.2 1942.07
   290.9  1938.8   294.2 1937.01   299.8 1936.56     305 1936.91   308.51938.692
   312.7 1942.01   316.7 1943.28   330.2 1942.68   352.9 1941.46     365 1941.53
   381.1 1941.92   413.3 1943.97   466.2 1948.47   550.3 1959.72   551.4 1959.84
#Mann= 6 ,-1 , 0
       0      .1       0   210.9     .04       0   290.9    .045       0
   308.5     .04       0   330.2     .05       0   550.3      .1       0
#XS Ineff= 2 , 0
          280.66 1944.14  316.64          1944.2
Permanent Ineff=
       F       F
Bank Sta=290.9,308.5
XS Rating Curve= 0 ,0
Exp/Cntr(USF)=0,0
Exp/Cntr=0.5,0.3

Type RM Length L Ch R = 1 ,28638   ,128.7,133.5,139.1
XS GIS Cut Line= 4
2037129.17616471282658.0572315492037152.05693153282791.620302841
2037306.22359821283031.2036361842037315.24552934283169.970274945
#Sta/Elev= 30
       0 1961.28     5.7  1958.3    22.4 1952.19    32.4 1950.65    42.4 1947.91
    45.7 1947.54    65.7 1945.82   125.6 1943.39   171.4 1939.13   205.8 1938.39
   225.3 1937.83     245 1940.32   291.6  1941.8   297.2 1941.35   301.9 1939.86
   306.71937.355   311.1 1935.99   316.2 1935.81   318.9 1935.85   323.41937.303
   330.4 1941.89   332.8 1942.17   342.3    1941   356.5 1940.16   385.3 1940.52
   400.9 1941.79   531.8 1956.45   538.7 1955.84   545.3 1958.72   559.5 1962.45
#Mann= 5 ,-1 , 0
       0      .1       0   205.8     .04       0   306.7    .045       0
   323.4     .05       0   531.8      .1       0
#XS Ineff= 2 , 0
          301.35 1942.38  327.44         1942.38
Permanent Ineff=
       F       F
Bank Sta=306.7,323.4
XS Rating Curve= 0 ,0
Exp/Cntr(USF)=0,0
Exp/Cntr=0.5,0.3

Type RM Length L Ch R = 1 ,28505   ,217.9,219.4,220.5
XS GIS Cut Line= 4
 2037083.0218831282663.2280682882037091.11530267282734.045489539
2037154.31480533 283081.642754162037178.07550049283187.773859209
#Sta/Elev= 30
       0 1965.29    13.7 1955.35    20.3 1951.51    23.6 1950.61    30.2 1950.05
    46.7 1945.78    63.4  1943.8    89.8 1941.83   126.5 1940.25   149.9  1937.5
   173.2 1936.46   206.5  1936.2   230.3 1937.12   253.2 1936.37   269.9  1937.2
   293.2 1935.71   303.2 1936.34   349.9 1936.96   356.41933.846   360.2 1933.04
   366.6 1932.84   369.9 1932.86   373.7 1933.82   382.3 1938.02   386.6 1939.34
   423.3 1941.42   456.9 1944.95   470.4 1944.06   527.5 1944.09   533.3  1944.7
#Mann= 6 ,-1 , 0
       0      .1       0  191.28     .04       0  291.28     .05       0
   356.4    .045       0   373.7     .05       0  484.57      .1       0
#XS Ineff= 2 , 0
          232.08 1939.41
Permanent Ineff=
       F       F
Bank Sta=356.4,373.7
XS Rating Curve= 0 ,0
Exp/Cntr(USF)=0,0
Exp/Cntr=0.3,0.1

Type RM Length L Ch R = 1 ,28285   ,186.5,180.9,172.5
XS GIS Cut Line= 4
2036911.38240799282676.7249800692036923.82250152282804.680227804
2036934.97535493283085.3603719642036941.73186967283206.977637327
#Sta/Elev= 30
       0 1947.79      10 1945.03    19.9 1943.37    49.5 1940.07    59.4 1940.07
   128.6 1933.59   168.6 1931.73   181.2 1930.75   217.3  1930.3   240.3 1931.06
   259.8 1928.98   273.1 1929.51   292.8 1930.62   302.7 1930.39   312.5 1931.18
   315.8 1931.09   324.71929.316     329 1928.44   338.4 1928.03   345.3 1928.28
   348.7 1929.01   355.2 1932.51   369.2 1931.86   380.2 1932.01   399.2 1933.23
   455.4 1938.72   470.2 1941.25   516.2 1955.86   526.1 1959.51   531.3 1962.03
#Mann= 7 ,-1 , 0
       0      .1       0   168.6     .04       0   273.1     .05       0
   324.7    .045       0   348.7     .05       0   369.2    .035       0
   470.2      .1       0
#XS Ineff= 2 , 0
           199.7 1933.41
Permanent Ineff=
       F       F
Bank Sta=324.7,348.7
XS Rating Curve= 0 ,0
Exp/Cntr(USF)=0,0
Exp/Cntr=0.5,0.3

Type RM Length L Ch R = 1 ,28104   ,50.3,50.7,51.1
XS GIS Cut Line= 4
2036651.56160633282684.7941443552036658.01364487282825.564141169
2036839.22024208283167.3610161842036837.75539647 283227.01247706
#Sta/Elev= 30
       0 1948.06    24.9 1946.39      38 1944.52      61 1942.58    74.1 1940.58
    90.6 1940.19   100.4 1939.05   113.6 1933.95   133.3 1923.95   139.8 1921.56
   165.7 1921.27   187.9 1921.84   202.4 1922.84   251.1 1923.12   282.5 1924.03
   314.2 1926.48   336.5 1926.69   355.1  1926.1   366.61923.812   373.6 1923.25
   382.6 1923.82   391.7 1925.13   403.3 1925.41   466.5 1928.96   486.4 1931.26
   502.9 1934.23   522.2 1939.74   549.1 1948.99   566.4 1956.78   587.4 1967.18
#Mann= 7 ,-1 , 0
       0      .1       0   251.1    .035       0   282.5     .04       0
   366.6    .045       0   382.6     .04       0   391.7    .035       0
   502.9      .1       0
#XS Ineff= 3 ,-1
       0  334.63 1928.56  335.23  361.38 1924.35  388.33  414.27 1924.45
Permanent Ineff=
       F       F       F
Bank Sta=366.6,382.6
XS Rating Curve= 0 ,0
Exp/Cntr(USF)=0,0
Exp/Cntr=0.5,0.3

Type RM Length L Ch R = 1 ,28054   ,202.5,207.4,213.9
XS GIS Cut Line= 4
 2036590.7027166282687.3102066972036595.07961711282797.352335632
2036787.13690877283185.8071967362036777.76397463283244.697130231
#Sta/Elev= 30
       0 1947.01    15.8 1945.75    55.2 1941.03    81.5 1935.15    88.4 1932.77
   101.2 1932.04   104.2 1931.31   116.5 1924.58   125.7 1920.47   129.4 1919.91
   154.5 1919.12   217.2 1921.32   281.9 1922.26   341.7 1925.53   381.9  1924.5
   388.51922.895   392.9 1921.92   403.9 1921.72   413.21922.839   425.9 1924.59
   462.5 1926.97   495.4  1930.7   528.3 1937.51     539  1938.7   543.5  1939.9
   549.7 1940.27   556.5  1942.7   569.6 1950.46   582.9 1956.35   603.1 1968.21
#Mann= 5 ,-1 , 0
       0      .1       0   281.9     .04       0   388.5    .045       0
   413.2    .035       0   603.1      .1       0
#XS Ineff= 3 ,-1
       0  343.18 1927.22  357.05  383.71 1923.17  417.94  447.49  1923.2
Permanent Ineff=
       F       F       F
Bank Sta=388.5,413.2
XS Rating Curve= 0 ,0
Exp/Cntr(USF)=0,0
Exp/Cntr=0.5,0.3

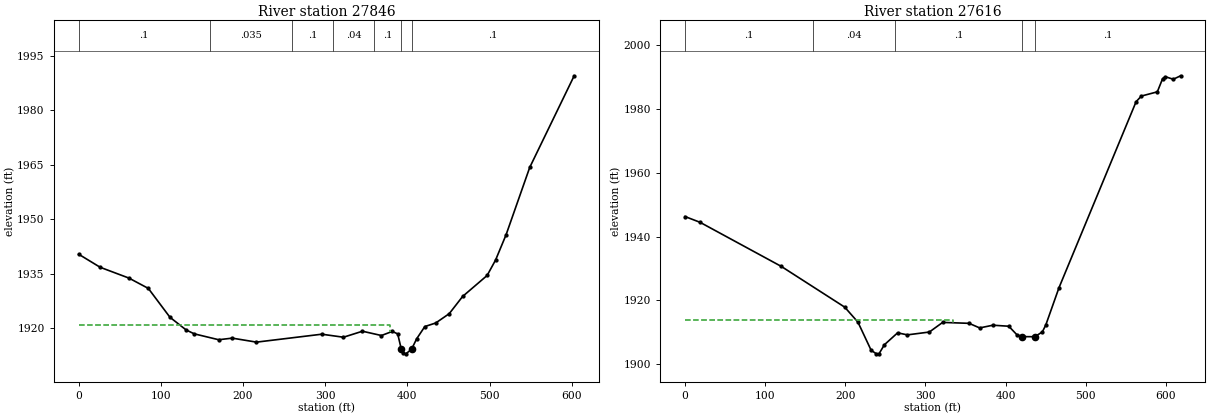
Type RM Length L Ch R = 1 ,27846   ,229.6,230,228.8
XS GIS Cut Line= 4
2036485.06106007282687.2140615462036488.86121852282806.539036706
2036524.17858765 283135.548212312036538.11220232283287.551281416
#Sta/Elev= 30
       0 1940.43    26.2 1936.83    61.2 1933.86    84.8 1931.02   111.1 1923.08
   130.8 1919.59   140.7 1918.52   170.4  1916.9   186.9 1917.34   216.4 1916.24
   295.8 1918.42   322.2 1917.59   345.3 1919.24   368.4 1918.06   381.6 1919.19
   388.2 1918.51   392.6 1914.27   394.8 1913.29   398.1 1913.02     405 1914.26
   411.3 1917.17   421.2 1920.53   434.4  1921.5   450.9 1924.07   467.2 1928.81
     497 1934.58   507.3 1938.83   520.1  1945.8   548.8 1964.29   602.9 1989.51
#Mann= 7 ,-1 , 0
       0      .1       0  159.39    .035       0  259.39      .1       0
  309.39     .04       0  359.39      .1       0   392.6    .045       0
     405      .1       0
#XS Ineff= 2 , 0
          378.86 1920.85
Permanent Ineff=
       F       F
Bank Sta=392.6,405
XS Rating Curve= 0 ,0
Exp/Cntr(USF)=0,0
Exp/Cntr=0.3,0.1

Type RM Length L Ch R = 1 ,27616   ,223.9,224.9,226.3
XS GIS Cut Line= 4
2036254.30469876 282685.217504782036271.38057701282866.020921561
2036302.98032834283152.2774924262036324.74681547283299.521375972
#Sta/Elev= 30
       0 1946.26    18.6 1944.47   120.1 1930.62   199.2 1917.85   215.7 1913.14
   232.2  1904.3   238.8  1903.2   242.1 1903.27   248.7 1906.05   265.2 1909.79
   277.4 1909.15   304.8 1910.04   321.4 1913.06   354.4 1912.77   367.6 1911.33
   384.1 1912.18   403.9 1911.86   413.8 1909.26   420.31908.599   436.41908.568
   445.8 1910.08   450.1 1912.23   466.6 1923.95   562.8 1982.29   569.4 1984.07
   589.3 1985.39   595.9 1989.52   599.2 1990.15   609.2 1989.34   618.4 1990.43
#Mann= 5 ,-1 , 0
       0      .1       0     160     .04       0  261.61      .1       0
   420.3    .045       0   436.4      .1       0
#XS Ineff= 2 , 0
          333.73  1913.9
Permanent Ineff=
       F       F
Bank Sta=420.3,436.4
XS Rating Curve= 0 ,0
Exp/Cntr(USF)=0,0
Exp/Cntr=0.3,0.1