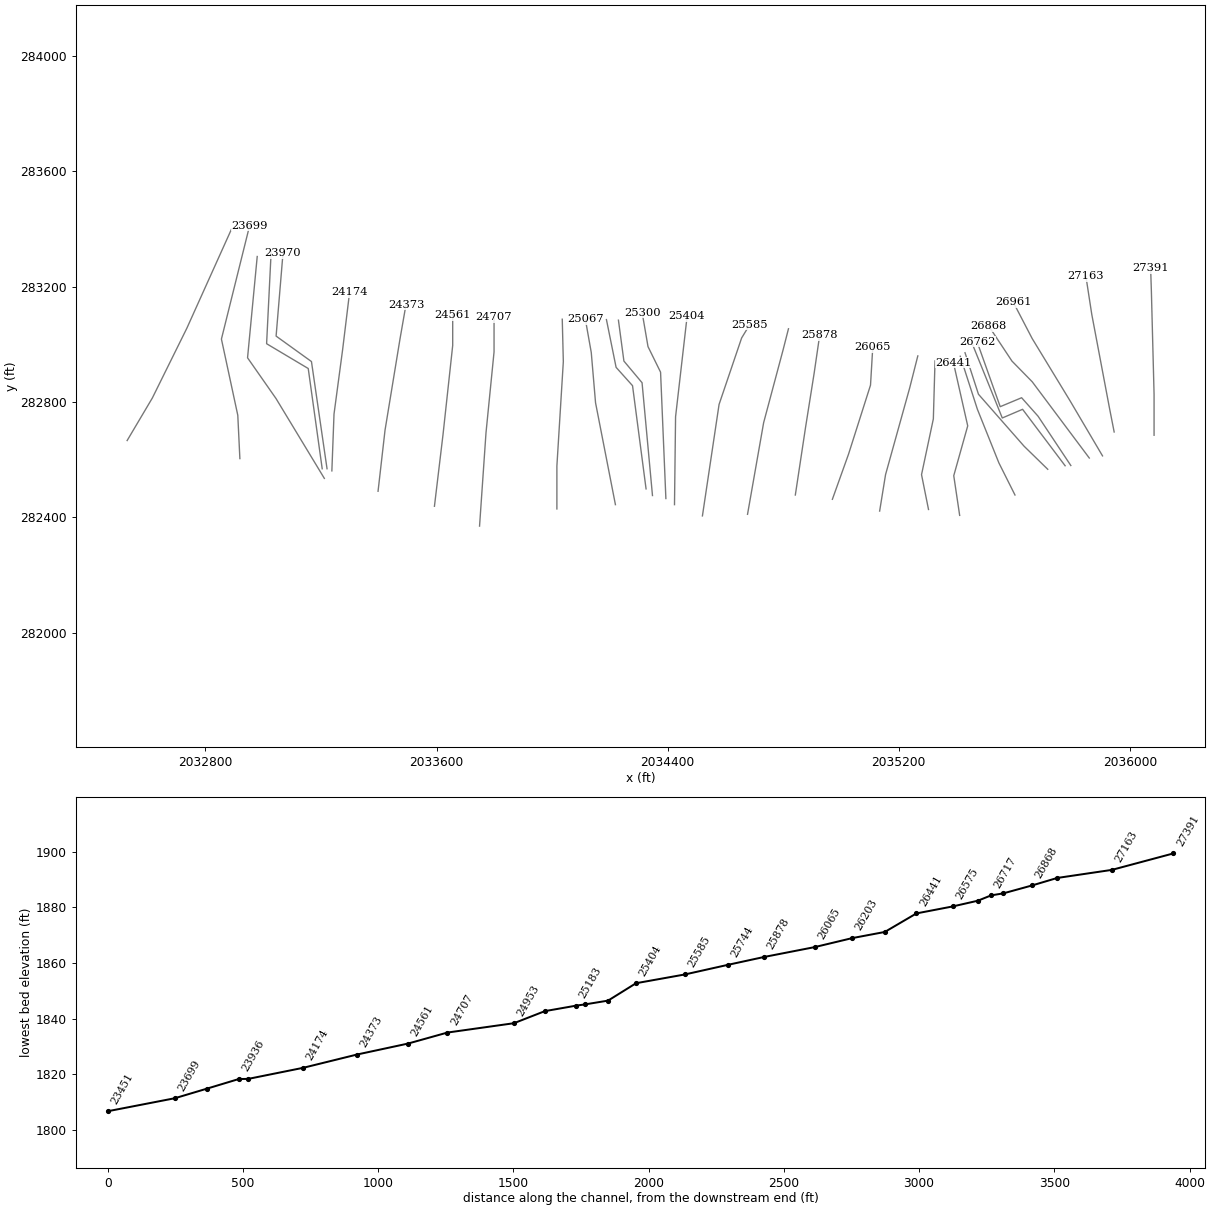
HEC-RAS study LICKCK1.prj: LICKCK1

--- LICKCK1.g01 (geometry) --- (continued)

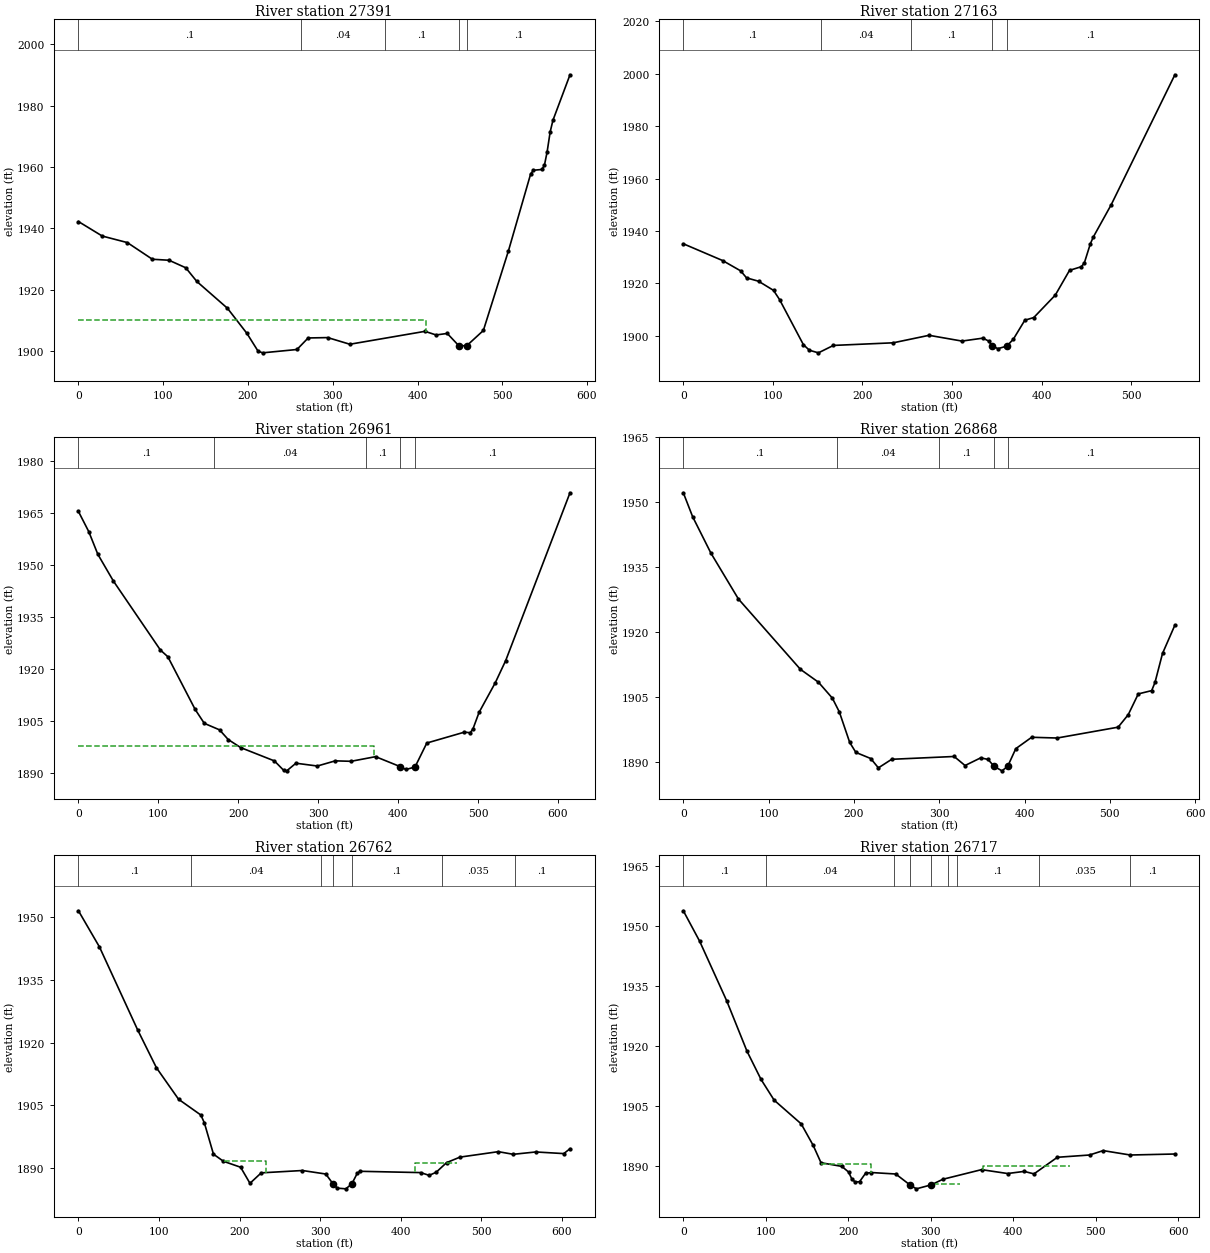
Type RM Length L Ch R = 1 ,27391   ,226.6,227.7,227
XS GIS Cut Line= 4
2036083.64087794  282684.79355052036083.64087794282826.985934625
2036074.34683343283183.8772437552036071.74576828283264.510263335
#Sta/Elev= 30
       0 1942.23    28.1  1937.5    57.7 1935.37    87.2 1929.94   106.9 1929.61
   126.6 1927.16   139.7 1922.69   175.8 1913.96   198.8 1905.76   211.9 1899.98
   217.3 1899.43   257.8 1900.52     271 1904.28   294.1  1904.4   320.2 1902.23
   408.8 1906.44   421.9 1905.26   435.1 1905.75   448.81901.728   458.11901.754
   477.7 1906.72   507.3 1932.69   533.5 1957.76   536.8 1958.95   546.7  1959.2
   549.7 1960.53   552.9 1964.91   556.5 1971.45   559.8 1975.25   579.9 1990.07
#Mann= 5 ,-1 , 0
       0      .1       0  262.19     .04       0  362.19      .1       0
   448.8    .045       0   458.1      .1       0
#XS Ineff= 2 , 0
          410.19 1910.16
Permanent Ineff=
       F       F
Bank Sta=448.8,458.1
XS Rating Curve= 0 ,0
Exp/Cntr(USF)=0,0
Exp/Cntr=0.3,0.1

Type RM Length L Ch R = 1 ,27163   ,198.1,202.4,207.4
XS GIS Cut Line= 4
 2035945.5129067282696.096268772 2035929.3597391 282778.65690318
2035868.01904534283103.9484609812035847.71529344  283235.9228483
#Sta/Elev= 30
       0 1935.13    43.9 1928.72      64 1924.79    70.6 1922.11      84 1920.83
   100.7 1917.34   107.4 1913.85   134.1 1896.58   140.8 1894.48   150.8  1893.5
   167.5 1896.33   234.3 1897.33   274.3 1900.19     311 1897.99   334.4 1899.11
   341.1 1897.96   344.51896.266   351.1 1895.09   361.1 1896.07   368.4 1898.71
   381.2 1905.95   391.2 1906.97   415.2 1915.53   431.1 1924.98   444.4 1926.39
   447.7 1927.89   454.4 1935.18   457.7 1937.74   477.6 1950.01   548.7 1999.63
#Mann= 5 ,-1 , 0
       0      .1       0  154.13     .04       0  254.13      .1       0
   344.5    .045       0   361.1      .1       0
Bank Sta=344.5,361.1
XS Rating Curve= 0 ,0
Exp/Cntr(USF)=0,0
Exp/Cntr=0.3,0.1

Type RM Length L Ch R = 1 ,26961   ,89.7,92.7,96.3
XS GIS Cut Line= 4
2035905.19522338282613.2229109272035793.66668927282802.821418903
2035661.69125725283020.3020604042035596.80974955283145.259038209
#Sta/Elev= 30
       0  1965.4    12.9  1959.6    24.3 1953.04    43.7 1945.35   102.6 1925.43
   111.9  1923.5   146.1 1908.29   157.5 1904.29   176.6 1902.41   187.5 1899.61
   203.2 1897.28   245.3 1893.45   256.8 1890.75   260.7 1890.59   272.2 1892.79
     299 1891.98   321.4 1893.47   341.2 1893.34   371.9 1894.68   402.51891.826
   409.8 1890.98   421.21891.683     436 1898.61   482.9 1901.74   490.3 1901.59
   493.7 1902.64   501.4 1907.45   521.7    1916   534.7 1922.38   615.2 1970.79
#Mann= 5 ,-1 , 0
       0      .1       0     170     .04       0  359.97      .1       0
   402.5    .045       0   421.2      .1       0
#XS Ineff= 2 , 0
          370.46  1897.8
Permanent Ineff=
       F       F
Bank Sta=402.5,421.2
XS Rating Curve= 0 ,0
Exp/Cntr(USF)=0,0
Exp/Cntr=0.3,0.1

Type RM Length L Ch R = 1 ,26868   ,90.1,106.1,125.9
XS GIS Cut Line= 4
2035859.39470129282605.7886918872035661.98919592282870.111317711
2035591.72621944282942.0472222082035511.29035488283063.732248078
#Sta/Elev= 30
       0  1952.2    10.9 1946.68    32.4 1938.23    64.6 1927.64   137.3 1911.37
   158.4  1908.4   174.7 1904.72   182.9 1901.53   195.1 1894.46   202.3 1892.16
   219.7 1890.75   228.7 1888.59   244.3 1890.57   317.5 1891.22   330.3 1889.13
   348.7 1890.91   357.3 1890.53   364.3 1888.95   373.6  1887.9   380.3 1888.95
   389.8 1893.03   408.4 1895.66   438.3 1895.49   509.8    1898   521.6 1900.88
   533.4 1905.69   549.1 1906.45     553 1908.35   561.8 1915.04   576.3 1921.59
#Mann= 5 ,-1 , 0
       0      .1       0     180     .04       0     300      .1       0
   364.3    .045       0   380.3      .1       0
Bank Sta=364.3,380.3
XS Rating Curve= 0 ,0
Exp/Cntr(USF)=0,0
Exp/Cntr=0.5,0.3

Type RM Length L Ch R = 1 ,26762   ,42.6,45.6,43.5
XS GIS Cut Line= 5
2035795.52549817282579.7643506962035682.13815517282750.774769655
2035625.18477967 282814.90469333 2035551.0921276282783.861568105
2035471.12292145283008.880025028
#Sta/Elev= 30
       0 1951.49    26.1 1942.85    73.4 1923.07    96.8 1913.99   124.3 1906.46
   151.9  1902.7   156.3 1900.82   167.6 1893.34     180 1891.64   201.3 1890.22
   212.9 1886.38   226.9 1888.88     278 1889.44     307  1888.6     3161886.247
   321.2 1885.23   331.9 1885.06   339.31886.247   346.1 1888.78   349.7 1889.25
   424.8 1888.94   435.3 1888.28     444 1889.02   456.9 1891.32   473.6 1892.64
   521.1 1893.94   539.7 1893.31   567.6 1893.87   602.4 1893.48   610.1 1894.64
#Mann= 7 ,-1 , 0
       0      .1       0     140     .04       0  300.95      .1       0
     316    .045       0   339.3      .1       0  451.29    .035       0
  541.29      .1       0
#XS Ineff= 4 ,-1
  180.42  233.211891.671  287.79     300 1886.66     355  365.24 1886.66
  417.16  469.97 1891.27
Permanent Ineff=
       F       F       F       F
Bank Sta=316,339.3
XS Rating Curve= 0 ,0
Exp/Cntr(USF)=0,0
Exp/Cntr=0.5,0.3

Type RM Length L Ch R = 1 ,26717   ,72.5,48.7,26.8
XS GIS Cut Line= 4
2035775.74830071282579.0218437022035628.53063569282774.754421053
2035558.26765921282744.6417168452035455.53132654282999.249149959
#Sta/Elev= 30
       0 1953.86    19.8 1946.25    52.6 1931.34    77.2 1918.74    94.2 1911.69
   110.1  1906.5   142.9 1900.57   157.5 1895.16   166.9 1890.85   192.2 1889.93
   200.4 1888.51   204.5 1886.69   208.6    1886   213.7 1886.12   220.9  1888.2
   227.8  1888.4   257.5 1888.03   274.61885.323   282.5 1884.32   300.51885.315
   314.6 1886.71   361.5 1889.12   393.1 1888.15   413.2 1888.68   425.1 1888.06
   453.4 1892.21   492.4 1892.78     509 1893.88   541.8 1892.78   595.9 1893.03
#Mann= 9 ,-1 , 0
       0      .1       0     100     .04       0  254.92      .1       0
   274.6    .045       0   300.5      .1       0  321.36     .04       0
  331.36      .1       0  431.36    .035       0  541.36      .1       0
#XS Ineff= 4 ,-1
  167.22  227.06 1890.59  248.18     272 1885.43     303  335.31 1885.57
  363.48  468.21 1889.92
Permanent Ineff=
       F       F       F       F
Bank Sta=274.6,300.5
XS Rating Curve= 0 ,0
Exp/Cntr(USF)=0,0
Exp/Cntr=0.5,0.3

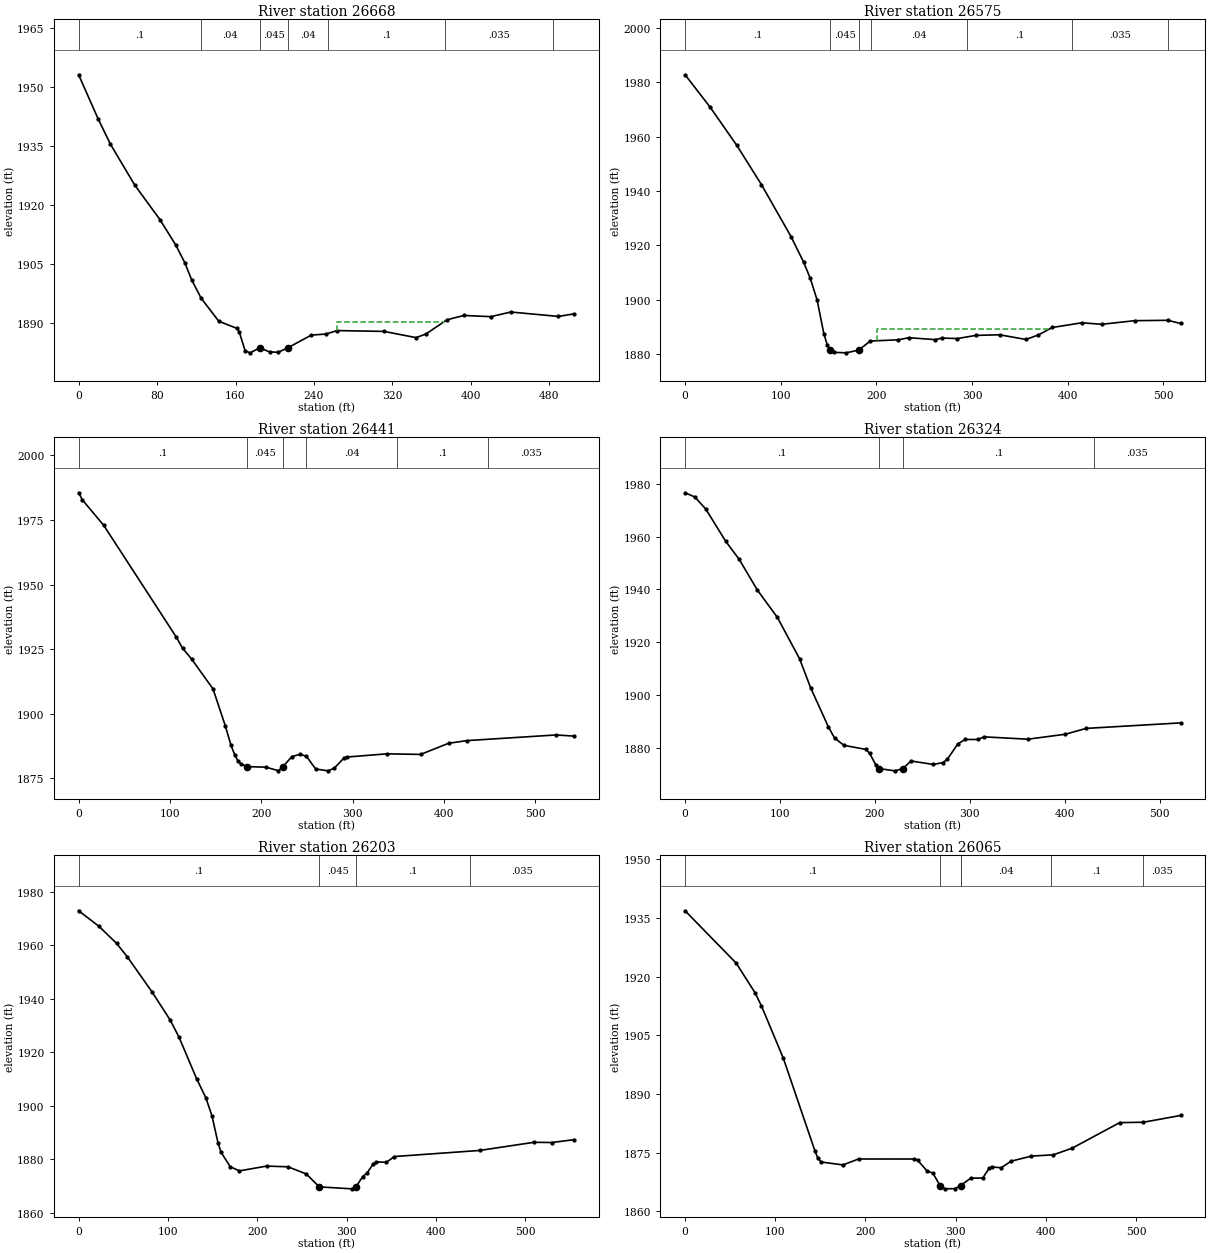
Type RM Length L Ch R = 1 ,26668   ,102,93,88.9
XS GIS Cut Line= 4
 2035715.5967154282566.7526883842035633.80912372282646.681471158
2035475.81036708282826.9859346252035429.31007932282970.957979418
#Sta/Elev= 30
       0 1953.12      20 1941.84    32.4 1935.49    57.1 1925.11    82.9  1916.3
    98.9  1909.9   108.2 1905.38   115.2    1901     125 1896.28     143 1890.43
   161.6 1888.62     164 1887.59   169.8 1882.94   174.8 1882.41   184.8 1883.68
   194.7 1882.65   203.5 1882.56   213.41883.693   237.3 1886.92   252.3 1887.19
   263.5 1888.07   311.5 1887.86   344.1 1886.28   354.1 1887.18   375.5  1890.8
   392.8 1891.92   420.4 1891.61   440.7 1892.79   489.4 1891.67   505.4 1892.33
#Mann= 7 ,-1 , 0
       0      .1       0  124.36     .04       0   184.8    .045       0
   213.4     .04       0  254.36      .1       0  374.09    .035       0
  484.09      .1       0
#XS Ineff= 1 ,-1
  263.48   373.21890.186
Permanent Ineff=
       T
Bank Sta=184.8,213.4
XS Rating Curve= 0 ,0
Exp/Cntr(USF)=0,0
Exp/Cntr=0.3,0.1

Type RM Length L Ch R = 1 ,26575   ,145.1,134.2,116
XS GIS Cut Line= 4
 2035602.2093724282477.5298611022035546.44510534282589.058395205
2035472.09274927282774.939285377 2035412.7945274282958.763773188
#Sta/Elev= 30
       0 1982.81    25.8 1971.05    54.1 1956.77    79.8 1942.34   110.7 1923.21
   123.8 1913.84   130.9 1907.75     138  1899.8     145 1887.47   148.6 1883.26
   151.71881.371   155.6 1880.54   168.3 1880.35   181.61881.367   193.5  1884.7
   222.8 1885.15   233.9 1885.93   261.6 1885.22   268.7 1885.81   284.4  1885.6
     304 1886.78   328.7    1887   356.3 1885.28   369.1 1886.91   383.8 1889.69
   414.9 1891.43   435.5 1890.87     470  1892.2   504.5 1892.34     518 1891.17
#Mann= 7 ,-1 , 0
       0      .1       0   151.7    .045       0   181.6      .1       0
  194.69     .04       0  294.69      .1       0  404.89    .035       0
  504.89      .1       0
#XS Ineff= 1 ,-1
  200.57  380.09 1889.18
Permanent Ineff=
       F
Bank Sta=151.7,181.6
XS Rating Curve= 0 ,0
Exp/Cntr(USF)=0,0
Exp/Cntr=0.3,0.1

Type RM Length L Ch R = 1 ,26441   ,115,117.1,117.8
XS GIS Cut Line= 4
2035410.75205552282406.895122837 2035390.3051576282544.446981564
2035438.63418904282717.3162094242035389.33946639282935.621409732
#Sta/Elev= 30
       0 1985.54     4.2 1982.75    27.5 1972.91   107.1 1929.53   113.7 1925.37
   123.7 1921.13   147.1 1909.57   160.7 1895.12   166.8  1887.7   170.9    1884
   174.3 1881.68   177.7 1880.52   184.6 1879.46     205 1879.27   218.6 1877.89
   223.41879.354   233.4 1883.37   242.5 1884.23   249.3 1883.48   259.5 1878.55
   273.1 1877.84   279.9 1878.89   290.2 1882.73   293.6 1883.19   337.6 1884.43
   374.3  1884.2   404.9 1888.51   425.1 1889.55   522.5 1891.74   542.4 1891.29
#Mann= 6 ,-1 , 0
       0      .1       0   184.6    .045       0   223.4      .1       0
  249.06     .04       0  348.56      .1       0  448.56    .035       0
Bank Sta=184.6,223.4
XS Rating Curve= 0 ,0
Exp/Cntr(USF)=0,0
Exp/Cntr=0.3,0.1

Type RM Length L Ch R = 1 ,26324   ,119,120.5,121.4
XS GIS Cut Line= 4
2035302.94113922282427.342020755 2035278.7766235282548.164599367
2035319.67041933282741.4807251462035325.44597821282942.662692765
#Sta/Elev= 30
       0 1976.69    10.2 1975.11    21.7 1970.56    42.8 1958.26      57 1951.42
    76.2 1939.74    97.2  1929.4   120.6 1913.71   132.3 1902.64   150.8 1887.98
   157.5 1883.57   167.5 1880.83   190.4 1879.29   194.4 1877.82   201.1  1873.3
   204.81871.991   220.9 1871.16   229.31871.981     238  1874.9   261.4 1873.59
   271.5 1874.27   276.3 1875.55   287.3 1881.35     295 1883.07   308.4 1883.06
   315.1 1884.06   361.2 1883.17   400.6 1885.05   422.6 1887.27   522.1 1889.36
#Mann= 4 ,-1 , 0
       0      .1       0   204.8    .045       0   229.3      .1       0
  430.81    .035       0
Bank Sta=204.8,229.3
XS Rating Curve= 0 ,0
Exp/Cntr(USF)=0,0
Exp/Cntr=0.3,0.1

Type RM Length L Ch R = 1 ,26203   ,138.9,138.4,138
XS GIS Cut Line= 4
2035133.78952916 282421.765594052035154.23642708282548.164599367
2035237.88282766282849.2916414462035265.90288249282959.934934873
#Sta/Elev= 30
       0 1972.92    22.9 1967.07    42.4 1960.75    54.4 1955.75    82.2 1942.56
   102.2 1932.21   112.2 1925.79   132.2 1910.03   142.4    1903   149.2 1896.32
     156 1886.17   159.4 1882.64   169.7 1877.24   179.9 1875.66   210.5 1877.46
   234.3 1877.19   254.8 1874.52   269.4 1869.68   305.9 1868.95   310.51869.705
   317.9 1873.51   322.9 1874.86   329.7 1878.27   333.1 1878.99   344.6 1878.89
   353.5 1881.03   448.8  1883.3   509.7 1886.35   529.6 1886.27   554.7 1887.34
#Mann= 4 ,-1 , 0
       0      .1       0   269.4    .045       0   310.5      .1       0
  438.04    .035       0
Bank Sta=269.4,310.5
XS Rating Curve= 0 ,0
Exp/Cntr(USF)=0,0
Exp/Cntr=0.3,0.1

Type RM Length L Ch R = 1 ,26065   ,184.8,187,189.2
XS GIS Cut Line= 4
2034970.21434581282462.6593898882035025.97861286282618.799337632
2035102.18977783282858.5856859542035110.00376981282990.307264992
#Sta/Elev= 30
       0 1936.87    56.7 1923.46    77.6 1915.87    84.6 1912.55     109 1899.09
   143.8 1875.52   147.3  1873.5   150.8 1872.59   175.1 1871.84   192.3 1873.36
   254.1 1873.35   257.7 1873.08     268 1870.36   274.9 1869.69   282.61866.535
   288.1 1865.72     299 1865.77   305.4 1866.55   316.8 1868.48     330 1868.48
   336.9 1870.93   340.3 1871.31   350.6 1871.12   361.2 1872.78   383.8 1874.09
   408.3 1874.43   429.2 1876.13   481.8 1882.66   508.1 1882.76   549.4  1884.5
#Mann= 6 ,-1 , 0
       0      .1       0   282.6    .045       0   305.4      .1       0
   305.8     .04       0   405.8      .1       0  507.41    .035       0
Bank Sta=282.6,305.4
XS Rating Curve= 0 ,0
Exp/Cntr(USF)=0,0
Exp/Cntr=0.3,0.1

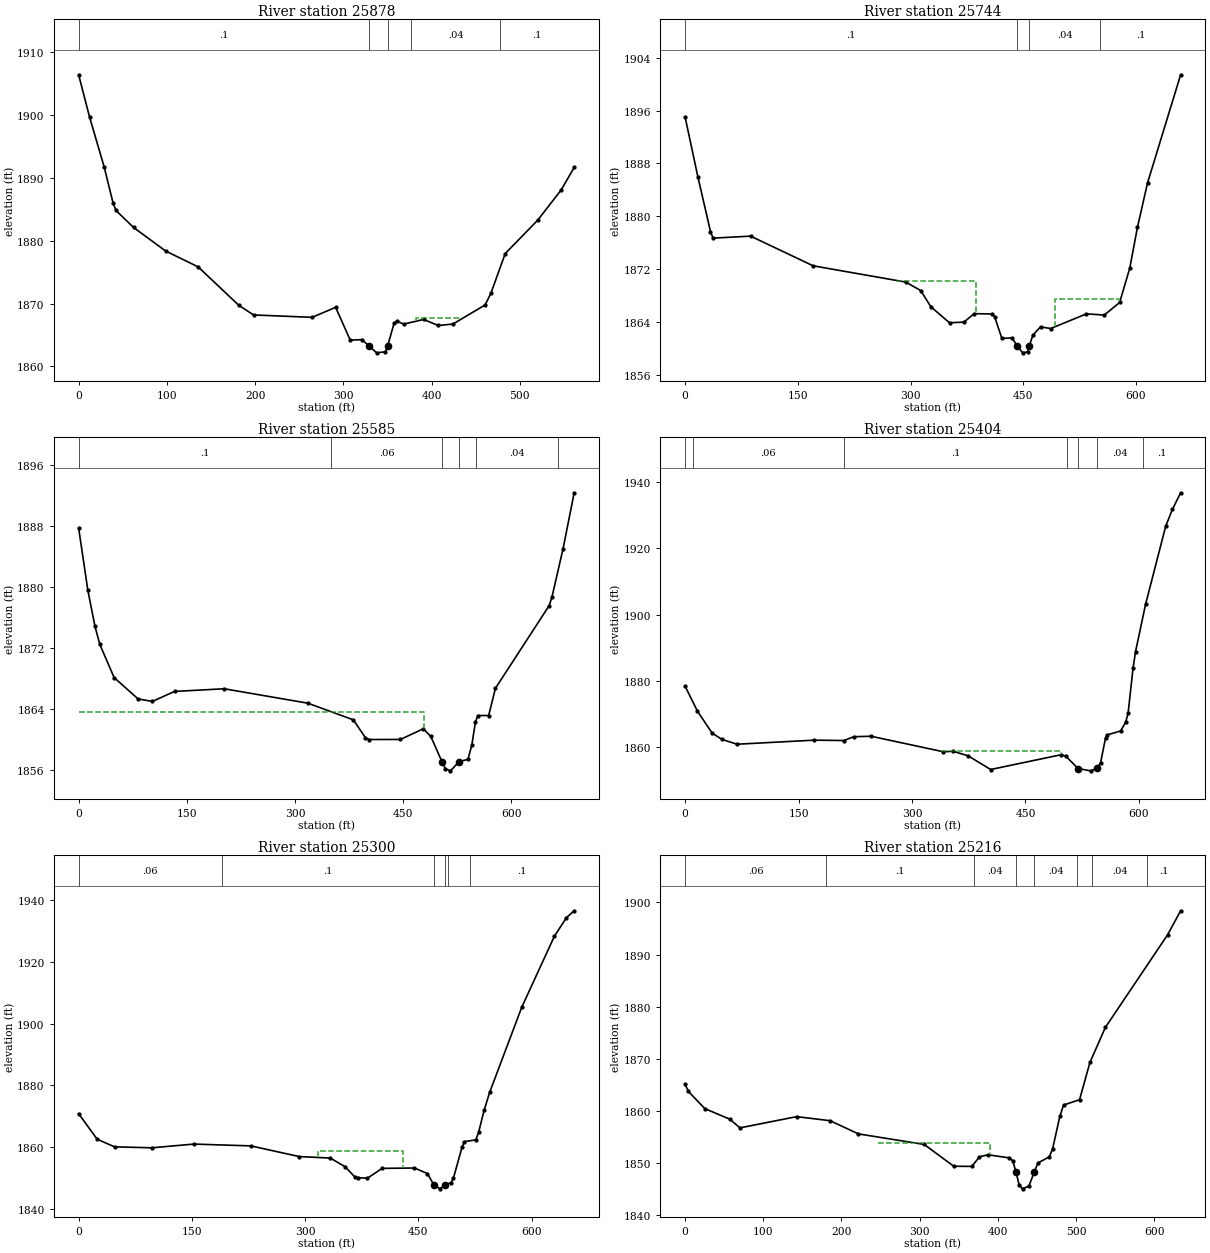
Type RM Length L Ch R = 1 ,25878   ,135.6,133.9,132.3
XS GIS Cut Line= 4
2034841.95653159282477.5298611022034877.27390072282711.739782718
2034907.01484315282899.4794817922034926.39431773283032.608046268
#Sta/Elev= 30
       0 1906.41    12.4 1899.68      29 1891.71      39 1886.03    42.3 1884.83
    62.2 1882.12    98.7 1878.36   135.4 1875.85   181.5 1869.73   198.2  1868.2
   264.6 1867.82   291.2 1869.41   307.8 1864.19   321.1 1864.27   329.21863.249
   337.7 1862.17   347.7 1862.34   350.11863.252   357.6 1866.95     361 1867.19
   368.2 1866.74   390.9 1867.48   407.5 1866.52   424.1 1866.75   460.6 1869.79
   467.2 1871.67   483.4 1877.97   520.2 1883.28   546.8 1888.09   561.5 1891.67
#Mann= 5 ,-1 , 0
       0      .1       0   329.2    .045       0   350.1      .1       0
  376.86     .04       0  476.94      .1       0
#XS Ineff= 1 ,-1
   382.8433.42151867.673
Permanent Ineff=
       T
Bank Sta=329.2,350.1
XS Rating Curve= 0 ,0
Exp/Cntr(USF)=0,0
Exp/Cntr=0.3,0.1

Type RM Length L Ch R = 1 ,25744   ,159.1,159,157.9
XS GIS Cut Line= 4
2034676.52253934 282410.612740642034732.28680639282728.469062834
2034799.20392685282979.4082645662034818.22776974283054.094462583
#Sta/Elev= 30
       0 1895.03    17.1 1885.93    33.8  1877.7    37.1  1876.7    87.2    1877
   170.4 1872.51   293.6 1870.05   313.6 1868.77     327 1866.32   351.9 1863.89
   371.1 1863.99   384.7 1865.27   408.5 1865.22   411.9 1864.82   421.6 1861.52
     435  1861.6   442.31860.346   449.2 1859.34     456  1859.5     4581860.362
   462.8 1862.01     473 1863.27   486.6 1863.02   534.1 1865.24   557.9 1865.06
   578.3 1866.96   591.8 1872.16     602 1878.33   615.5 1885.08   659.5 1901.42
#Mann= 4 ,-1 , 0
       0      .1       0   442.3    .045       0     458     .04       0
  552.71      .1       0
#XS Ineff= 2 ,-1
281.0989386.5812 1870.22492.7869   577.7 1867.55
Permanent Ineff=
       T       T
Bank Sta=442.3,458
XS Rating Curve= 0 ,0
Exp/Cntr(USF)=0,0
Exp/Cntr=0.3,0.1

Type RM Length L Ch R = 1 ,25585   ,176.9,181,184.2
XS GIS Cut Line= 4
2034520.38259159282405.0363139352034578.00566755282791.668565492
2034656.07564142283022.1608693062034683.59641028283067.417244766
#Sta/Elev= 30
       0 1887.75    12.8 1879.56    22.7 1874.83    29.3 1872.49    49.2 1868.12
    82.4 1865.32   102.3 1864.99     133  1866.3   201.8 1866.65   317.8 1864.76
     381 1862.57   397.8 1860.22     403 1859.99   446.3    1860     478  1861.4
   488.4 1860.39   503.81857.095   508.7 1856.14   515.6 1855.88   527.81857.091
   539.9 1857.39   545.3 1859.28   550.2 1862.27   553.7 1863.14   568.6 1863.14
     578 1866.71   652.5 1877.56   656.3 1878.65   671.7 1884.99   687.2 1892.37
#Mann= 6 ,-1 , 0
       0      .1       0     350     .06       0   503.8    .045       0
   527.8     .06       0   550.9     .04       0  664.26      .1       0
#XS Ineff= 2 , 0
          478.56 1863.56
Permanent Ineff=
       F       F
Bank Sta=503.8,527.8
XS Rating Curve= 0 ,0
Exp/Cntr(USF)=0,0
Exp/Cntr=0.3,0.1

Type RM Length L Ch R = 1 ,25404   ,92.8,103.4,111.3
XS GIS Cut Line= 4
2034423.72452871282444.0713008712034427.44214651282748.915960753
2034466.47713344283089.077989767 2034466.8479101283096.987891772
#Sta/Elev= 30
       0 1878.34    16.2 1870.81    35.9 1864.09      49  1862.2    68.7 1860.77
   170.4    1862   210.1 1861.89   222.9 1863.04   245.9 1863.18   341.3  1858.5
   354.5 1858.63   374.3 1857.25     404 1853.12   496.5 1857.56   503.1 1857.22
   519.6 1853.42   536.1 1852.72   544.11853.428   549.3 1855.12   555.9 1862.66
   558.4 1863.61   575.8 1864.77   582.4 1867.36   585.7 1870.08   592.3 1883.82
   595.6 1888.81   608.8 1903.04   635.4 1926.67   644.3 1931.78   655.2 1936.82
#Mann= 7 ,-1 , 0
       0      .1       0      10     .06       0     210      .1       0
  504.87     .04       0   519.6    .045       0   544.1     .04       0
  604.87      .1       0
#XS Ineff= 1 ,-1
338.1785  496.57 1858.63
Permanent Ineff=
       T
Bank Sta=519.6,544.1
XS Rating Curve= 0 ,0
Exp/Cntr(USF)=0,0
Exp/Cntr=0.3,0.1

Type RM Length L Ch R = 1 ,25300   ,80.2,84.5,88.1
XS GIS Cut Line= 4
2034393.90976317282465.2627389172034375.50755504282903.569877942
2034332.01142674282992.235062554 2034311.9362906283109.340023363
#Sta/Elev= 30
       0  1870.8    24.6 1862.52    47.6 1860.07    96.8 1859.75   152.7 1860.96
   228.2 1860.37   292.2 1856.91   333.3 1856.43     353 1853.61   366.1 1850.23
   369.4 1850.09   382.5 1849.91   401.9 1853.09   444.8 1853.21     462 1851.41
   470.31847.805   478.5 1846.46   485.31847.815   493.1 1848.41   496.3 1849.86
   507.7 1859.88     511 1861.76     526 1862.32   529.7 1864.74     537 1871.85
   544.3 1877.67   586.9 1905.31   630.2 1928.34   646.1 1934.32   656.3 1936.54
#Mann= 6 ,-1 , 0
       0     .06       0     190      .1       0   470.3    .045       0
   485.3      .1       0  488.69     .04       0  518.69      .1       0
#XS Ineff= 1 ,-1
317.0262429.0005 1858.63
Permanent Ineff=
       T
Bank Sta=470.3,485.3
XS Rating Curve= 0 ,0
Exp/Cntr(USF)=0,0
Exp/Cntr=0.5,0.3

Type RM Length L Ch R = 1 ,25216   ,32.5,33.2,33.5
XS GIS Cut Line= 4
2034347.51336373  282475.67105222034311.45247104282866.950326012
2034248.62473016282942.0462056412034229.66487937283083.873324843
#Sta/Elev= 30
       0 1865.16     4.3 1863.77    25.3 1860.48    57.1 1858.47    70.2  1856.8
   142.7 1858.95   185.5 1858.17   221.8 1855.64   305.9 1853.62   343.7 1849.44
   366.8 1849.41   376.6 1851.24   387.3 1851.64   414.2 1851.06     419 1850.53
   423.5 1848.25   427.4 1845.78   431.7 1845.11   439.9 1845.66   446.8 1848.38
   451.5 1850.09   465.9 1851.23   470.2 1852.82   479.4 1858.99   484.1 1861.17
   504.6 1862.19   517.9 1869.34   537.7 1876.07   617.2 1893.79 633.938 1898.41
#Mann= 8 ,-1 , 0
       0     .06       0     180      .1       0     370     .04       0
   423.5    .045       0   446.8     .04       0  500.85      .1       0
  520.85     .04       0  590.85      .1       0
#XS Ineff= 3 ,-1
  247.19  390.43 1853.85  395.79  415.67  1848.6  449.43  469.87 1848.48
Permanent Ineff=
       F       F       F
Bank Sta=423.5,446.8
XS Rating Curve= 0 ,0
Exp/Cntr(USF)=0,0
Exp/Cntr=0.5,0.3

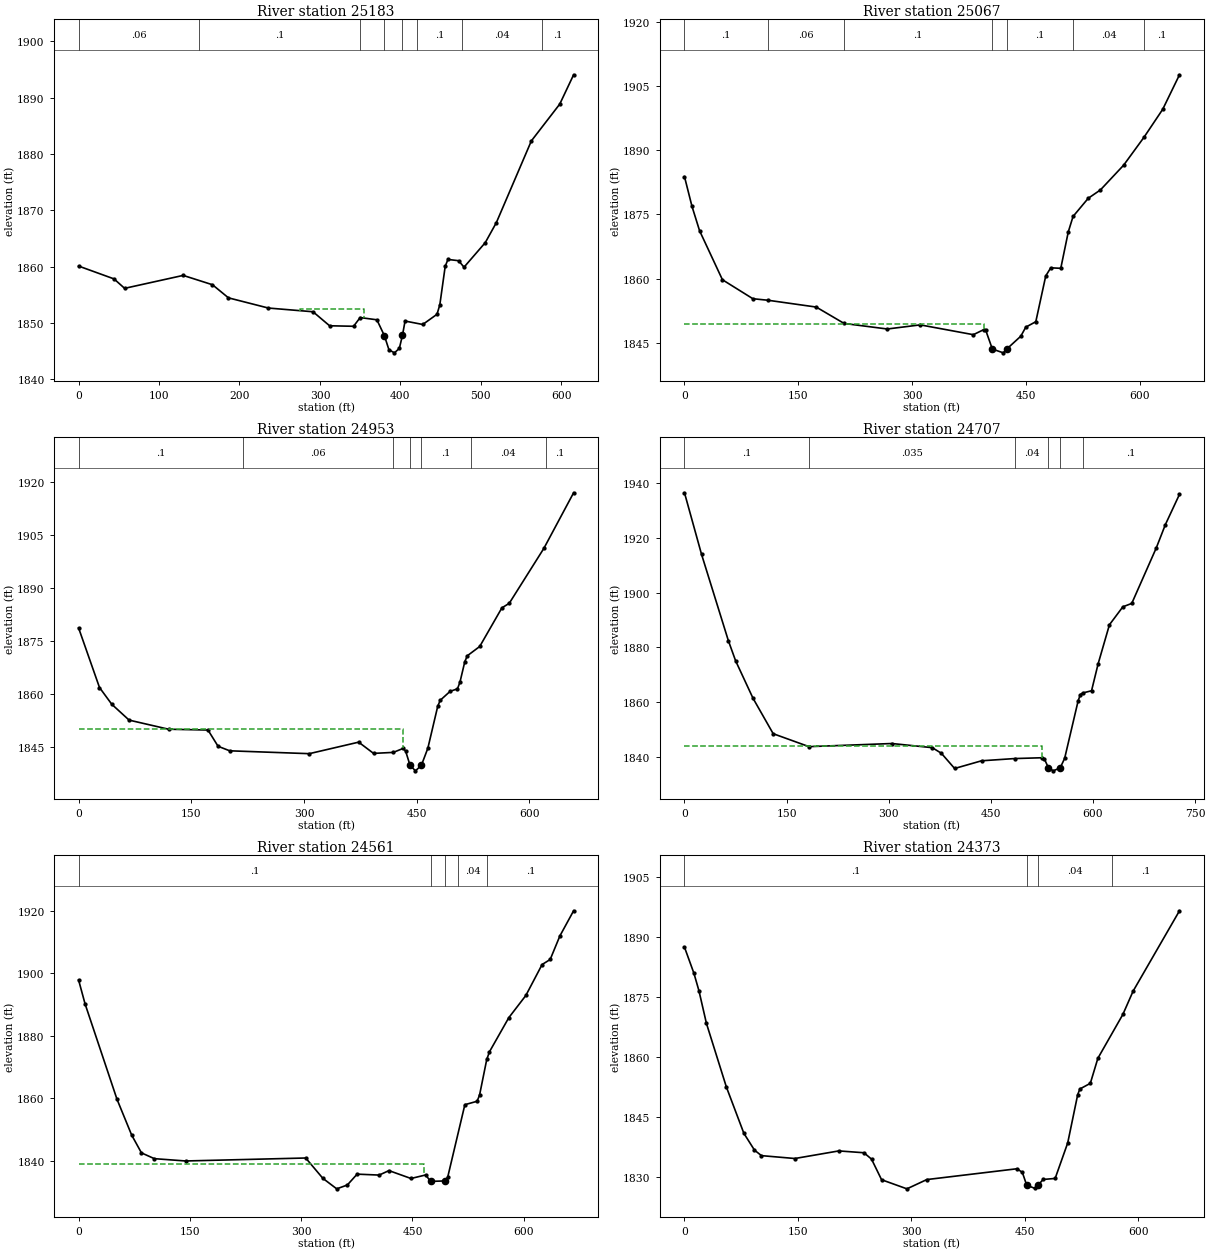
Type RM Length L Ch R = 1 ,25183   ,126.6,116.2,106.2
XS GIS Cut Line= 4
2034325.31971469282498.7212991482034278.47773037282856.727893619
2034221.59817798282920.2991580582034188.13961775283085.919031201
#Sta/Elev= 30
       0 1860.08      44  1857.8    57.2 1856.12     130 1858.42   166.4 1856.76
   186.3 1854.43   235.9 1852.62   291.4 1851.96     312 1849.47   341.8 1849.38
     350 1850.93   370.8 1850.53   380.1 1847.71   385.8  1845.2   392.6 1844.66
   398.7 1845.45  402.59 1847.78   405.8 1850.31   427.8  1849.7   445.5 1851.51
     449 1853.18   455.7 1860.02   459.1 1861.26   472.4 1861.03   479.1 1859.88
   505.5 1864.24   519.3  1867.8   562.8 1882.32   598.1 1888.86615.3267 1894.07
#Mann= 8 ,-1 , 0
       0     .06       0     150      .1       0     350     .04       0
   380.1    .045       0  402.59     .04       0  421.06      .1       0
  476.36     .04       0  576.36      .1       0
#XS Ineff= 3 ,-1
  274.92  354.241852.536  359.83  376.64 1848.05  405.98  428.16 1847.98
Permanent Ineff=
       F       F       F
Bank Sta=380.1,402.59
XS Rating Curve= 0 ,0
Exp/Cntr(USF)=0,0
Exp/Cntr=0.5,0.3

Type RM Length L Ch R = 1 ,25067   ,116.9,114.3,112.1
XS GIS Cut Line= 4
2034219.25554952282444.0713008712034150.47962015282797.244992198
2034135.60914894282971.9730289592034115.16225102283087.219180866
#Sta/Elev= 30
       0 1883.82     9.9 1876.87    19.9 1871.18      50 1859.74    90.1 1855.31
   110.1 1854.95   173.6 1853.36   210.4 1849.53   267.2 1848.24   310.7  1849.2
   380.6 1846.91   394.2 1848.08     397  1847.9  405.651843.552   420.1 1842.67
  424.571843.552   443.1 1846.55   449.7 1848.67   462.9 1849.94     476 1860.63
   482.6 1862.53   495.8 1862.41   505.7 1870.92     512 1874.53     532 1878.77
     548 1880.71   578.6 1886.49   605.3 1892.98   630.1 1899.54652.2136 1907.61
#Mann= 7 ,-1 , 0
       0      .1       0   110.1     .06       0   210.4      .1       0
  405.65    .045       0  424.57      .1       0     512     .04       0
   605.3      .1       0
#XS Ineff= 2 , 0
           394.21849.471
Permanent Ineff=
       F       F
Bank Sta=405.65,424.57
XS Rating Curve= 0 ,0
Exp/Cntr(USF)=0,0
Exp/Cntr=0.3,0.1

Type RM Length L Ch R = 1 ,24953   ,246.2,245.8,245.1
XS GIS Cut Line= 4
2034016.64537923282429.2008296572034016.64537923282577.905541795
2034038.95108605 282940.373277632034035.23346825283087.219180866
#Sta/Elev= 30
       0 1878.77    27.8 1861.91    44.2 1857.16    67.2 1852.69   119.7 1850.11
   172.2 1849.88   185.6 1845.28   201.1    1844     307 1843.19   372.7 1846.45
   392.5 1843.27   418.8 1843.55   431.9 1844.68   435.2 1843.92  441.091839.885
   448.3 1838.33  456.161839.885   464.8 1844.75   477.9 1856.59   481.2 1858.29
   494.4 1860.83   504.2 1861.55   507.5 1863.43     514 1869.27   517.4 1870.92
   533.8 1873.53   563.3 1884.46   573.1 1885.75   619.1 1901.28658.7511 1917.04
#Mann= 7 ,-1 , 0
       0      .1       0   218.7     .06       0   418.7      .1       0
  441.09    .045       0  456.16      .1       0  521.86     .04       0
  621.86      .1       0
#XS Ineff= 2 , 0
           431.6 1850.17
Permanent Ineff=
       F       F
Bank Sta=441.09,456.16
XS Rating Curve= 0 ,0
Exp/Cntr(USF)=0,0
Exp/Cntr=0.3,0.1

Type RM Length L Ch R = 1 ,24707   ,145.7,145.5,145.3
XS GIS Cut Line= 4
2033748.97689738282369.718944802 2033771.2826042282693.151693701
2033799.16473773282973.8318378612033799.16473773283094.654416473
#Sta/Elev= 30
       0 1936.45      25 1914.03    64.5 1882.44    75.1 1875.13   100.7 1861.44
   130.3 1848.52   182.9  1843.8   304.7 1844.94   363.9 1843.43   377.2 1841.41
   396.8 1835.83   436.4 1838.64   484.9 1839.45   525.4 1839.75   528.7 1839.27
  534.59 1836.07   541.8 1834.97   551.91836.095   558.4 1839.52   578.2  1860.5
   581.5 1862.81   584.8 1863.38   597.9 1864.19   607.6 1874.04   624.2 1888.29
   643.9 1894.83     657 1896.08   693.1 1916.39   706.4 1924.86727.0852 1935.88
#Mann= 6 ,-1 , 0
       0      .1       0   182.9    .035       0   484.9     .04       0
  534.59    .045       0   551.9     .04       0   584.8      .1       0
#XS Ineff= 2 , 0
             525    1844
Permanent Ineff=
       F       F
Bank Sta=534.59,551.9
XS Rating Curve= 0 ,0
Exp/Cntr(USF)=0,0
Exp/Cntr=0.3,0.1

Type RM Length L Ch R = 1 ,24561   ,189.5,188.4,188.2
XS GIS Cut Line= 4
2033592.83694964282438.4948741662033622.57789206282687.575266996
 2033656.0364523282996.137544681 2033656.0364523283102.089652079
#Sta/Elev= 30
       0 1897.77     8.7 1890.16    51.7 1859.68    71.5 1848.21    84.7 1842.51
   102.1 1840.66   144.2 1839.92   306.1 1840.87   329.2 1834.37   347.9 1831.01
   362.2 1832.24   375.4 1835.71   405.1 1835.41   418.3 1836.84     448 1834.32
   467.8 1835.45   474.4 1833.39   493.8 1833.54   497.5 1834.77   520.6 1857.92
   537.1 1859.01   540.4 1860.98   550.1 1872.38   553.8 1874.85   579.8 1885.73
   602.8 1892.84   624.7 1902.73   635.6 1904.35   648.7 1911.89667.1728 1919.92
#Mann= 5 ,-1 , 0
       0      .1       0   474.4    .045       0   493.8      .1       0
  510.85     .04       0  550.85      .1       0
#XS Ineff= 2 , 0
             465    1839
Permanent Ineff=
       F       F
Bank Sta=474.4,493.8
XS Rating Curve= 0 ,0
Exp/Cntr(USF)=0,0
Exp/Cntr=0.3,0.1

Type RM Length L Ch R = 1 ,24373   ,199,199.2,199.9
XS GIS Cut Line= 4
2033397.66201496282490.5415234142033421.82653068 282702.44573821
2033473.87317993283020.3020604042033494.32007785283137.407021212
#Sta/Elev= 30
       0 1887.54    12.5    1881    19.1 1876.65      29 1868.48    55.4 1852.54
    78.5 1840.96    92.5 1836.76   101.7 1835.38   145.9 1834.66     204 1836.56
   237.2  1836.1   247.2 1834.51   260.5 1829.35     294 1827.07   320.3 1829.39
   439.7  1832.1   446.6 1831.16   452.3 1827.99   463.3 1827.17  467.291827.975
     474 1829.42   489.9 1829.67   506.5 1838.55   519.7 1850.63   522.6 1852.06
   536.4 1853.47   546.4 1859.75   579.4 1870.71     593 1876.56654.2434 1896.65
#Mann= 4 ,-1 , 0
       0      .1       0   452.3    .045       0  467.29     .04       0
  565.37      .1       0
Bank Sta=452.3,467.29
XS Rating Curve= 0 ,0
Exp/Cntr(USF)=0,0
Exp/Cntr=0.3,0.1

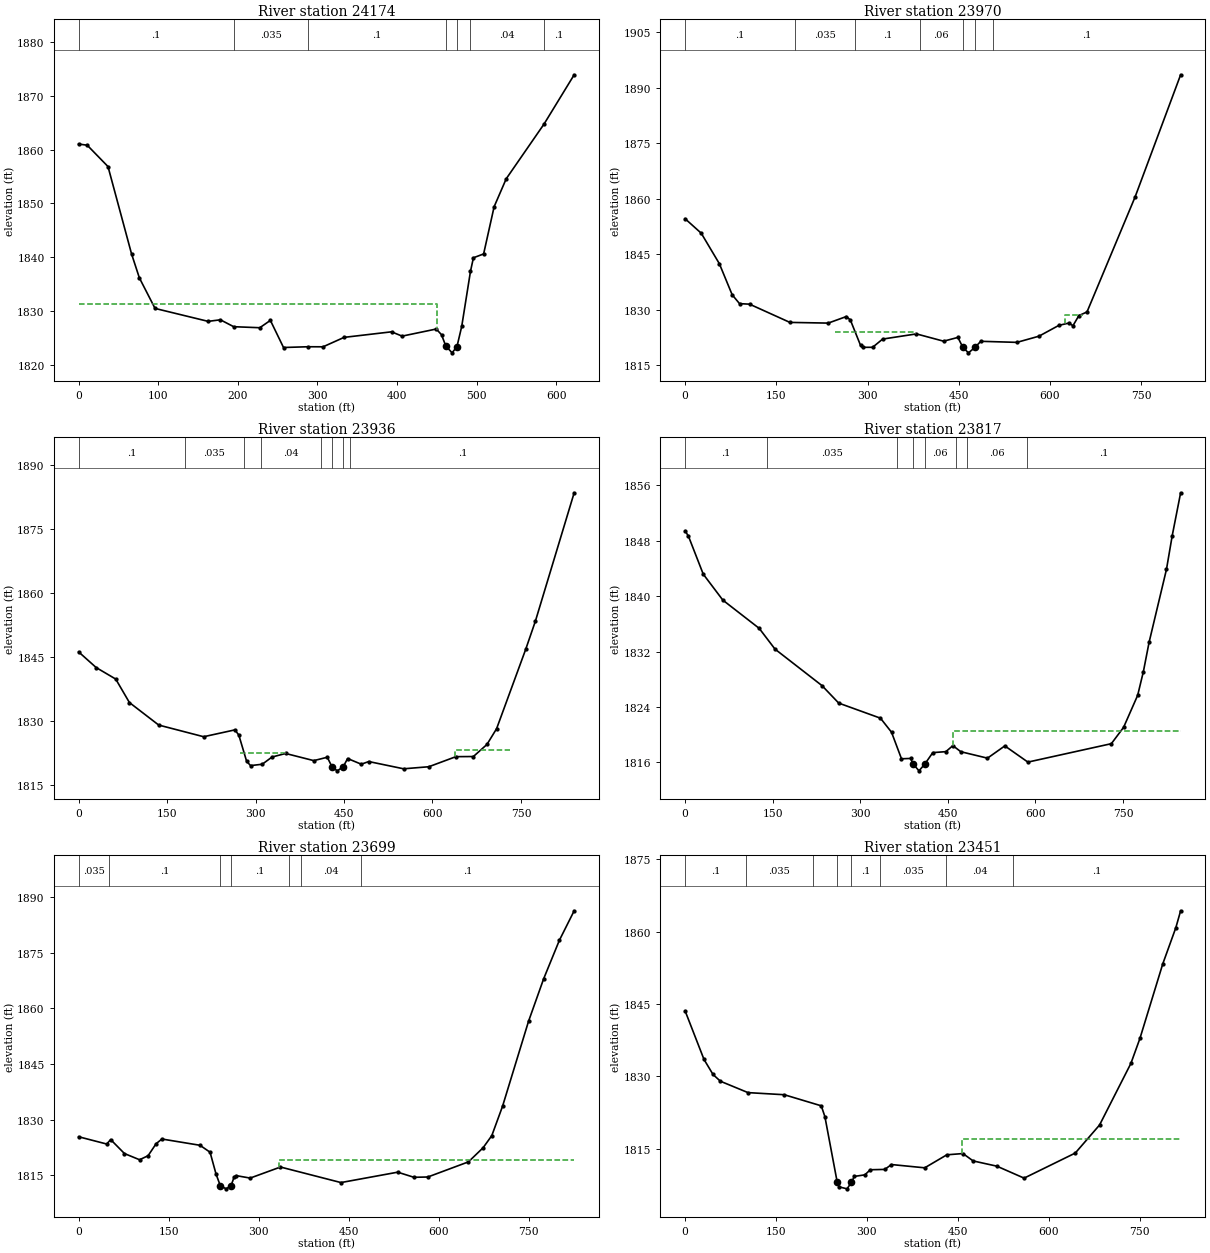
Type RM Length L Ch R = 1 ,24174   ,191.9,203.9,222.1
XS GIS Cut Line= 4
2033237.80444941282561.1762616792033245.23968502282758.210005261
2033274.98062744282981.2670734682033299.14514317283180.159625952
#Sta/Elev= 30
       0 1861.03    10.8 1860.81    36.9 1856.85    66.5 1840.64    76.3  1836.2
      96 1830.53   162.7 1828.13   178.1 1828.42   194.8 1827.14   227.6 1826.95
   240.9 1828.31   257.4 1823.28     288 1823.42   307.1 1823.41   333.5 1825.16
   393.1 1826.19   406.4 1825.39   449.3 1826.71   455.9 1825.65   461.3 1823.55
   469.2 1822.29  475.321823.455   481.3 1827.21   492.3 1837.43     496 1839.93
   508.8 1840.64     522  1849.4   537.2 1854.59   584.8 1864.76622.5602 1873.88
#Mann= 7 ,-1 , 0
       0      .1       0   194.8    .035       0     288      .1       0
   461.3    .045       0  475.32      .1       0   492.3     .04       0
   584.8      .1       0
#XS Ineff= 2 , 0
             450 1831.39
Permanent Ineff=
       F       F
Bank Sta=461.3,475.32
XS Rating Curve= 0 ,0
Exp/Cntr(USF)=0,0
Exp/Cntr=0.5,0.3

Type RM Length L Ch R = 1 ,23970   ,33.5,34,36.3
XS GIS Cut Line= 4
2033221.07516929282568.6114972862033167.16971114 282940.37327763
2033044.77485716283028.6610199422033068.65283935283315.852675777
#Sta/Elev= 30
       0 1854.55    26.5 1850.64    56.3  1842.4    77.4 1833.99    89.5 1831.59
     106 1831.45   172.3 1826.52   235.3 1826.33   265.2 1828.11   271.8 1827.14
   288.4 1820.34   291.7 1819.78   308.3 1819.79   324.8 1822.01   380.3 1823.41
     425 1821.44   448.5 1822.46  456.71 1819.78   465.9 1818.29  476.881819.791
   486.1 1821.41   545.5 1821.12   581.8 1822.79   614.7 1825.73   631.1 1826.34
   637.7 1825.62   647.4 1828.35   660.8 1829.35   739.8 1860.41814.7468 1893.47
#Mann= 7 ,-1 , 0
       0      .1       0     180    .035       0     280      .1       0
  385.65     .06       0  456.71    .045       0  476.88     .06       0
  505.65      .1       0
#XS Ineff= 4 ,-1
  246.88  378.66 1823.95  417.12  446.34 1820.28   486.7  512.96 1820.38
 624.885 653.765 1828.54
Permanent Ineff=
       F       F       F       T
Bank Sta=456.71,476.88
XS Rating Curve= 0 ,0
Exp/Cntr(USF)=0,0
Exp/Cntr=0.5,0.3

Type RM Length L Ch R = 1 ,23936   ,124.8,118.5,112.2
XS GIS Cut Line= 4
2033204.34588918282568.6114972862033156.01685773282916.208761908
2033011.90072504283002.2342761632033027.75904351283323.287911384
#Sta/Elev= 30
       0 1846.19    29.8 1842.51    62.9 1839.81    86.1  1834.3   135.8 1829.01
     212 1826.27     265 1827.88   271.6 1826.66   284.8 1820.52   291.5 1819.49
   311.3 1819.81   327.9  1821.5   350.9 1822.34   398.7 1820.66   421.6 1821.45
  429.631819.211   438.5 1818.26  448.55  1819.2   456.1 1821.15   479.2 1819.82
     492 1820.44     551 1818.74   593.7 1819.22   639.7 1821.59   669.3 1821.62
   692.3 1824.45   708.7 1828.16     758 1846.78   774.4 1853.38840.2247 1883.56
#Mann= 8 ,-1 , 0
       0      .1       0     180    .035       0     280      .1       0
     310     .04       0  410.94     .06       0  429.63    .045       0
  448.55     .06       0  460.94      .1       0
#XS Ineff= 4 ,-1
  274.25  354.31 1822.39  403.95  423.69  1819.4  452.52  469.06 1819.42
  638.68  731.63 1823.26
Permanent Ineff=
       F       F       F       F
Bank Sta=429.63,448.55
XS Rating Curve= 0 ,0
Exp/Cntr(USF)=0,0
Exp/Cntr=0.5,0.3

Type RM Length L Ch R = 1 ,23817   ,124,118.3,113.4
XS GIS Cut Line= 4
2033211.78112478282535.1529370552033044.48832363282812.115463411
2032945.97145184282953.3849399422032979.43001207283304.699822367
#Sta/Elev= 30
       0 1849.43     5.8 1848.64    31.1 1843.17    64.7 1839.42   126.9 1835.35
     154 1832.35   234.5 1827.08   263.1 1824.56   334.6 1822.38   353.5 1820.36
   370.6 1816.52   386.2 1816.57  390.471815.777   400.6 1814.78  410.721815.776
   424.2 1817.41   446.6 1817.55   458.6 1818.42   472.2 1817.54   517.9 1816.61
   547.6 1818.38   587.1 1816.04     730  1818.7     751 1821.06   775.1 1825.68
   784.9 1829.11   794.7 1833.35   824.4 1843.85   834.3 1848.74848.6993 1854.92
#Mann= 8 ,-1 , 0
       0      .1       0     140    .035       0  363.57     .06       0
  390.47    .045       0  410.72     .06       0  463.57      .1       0
  483.57     .06       0  585.79      .1       0
#XS Ineff= 2 , 0
                           458.6         1820.51
Permanent Ineff=
       F       F
Bank Sta=390.47,410.72
XS Rating Curve= 0 ,0
Exp/Cntr(USF)=0,0
Exp/Cntr=0.3,0.1

Type RM Length L Ch R = 1 ,23699   ,256.7,248.1,236.7
XS GIS Cut Line= 4
 2032919.4036268282603.8201840222032912.21352544282753.913549915
 2032855.5511599 283018.33792246  2032953.136345283411.826572082
#Sta/Elev= 30
       0 1825.38    46.8 1823.42    53.4 1824.62    76.4 1820.85   101.6 1819.18
   115.8 1820.27   129.2 1823.51   138.8 1824.77   202.3 1823.08   219.1 1821.21
   229.1 1815.31   236.11812.228   245.9 1811.34   254.11812.202   259.3 1814.54
   262.7  1814.9     286 1814.24   336.5 1817.22   437.3 1813.03   531.9 1815.83
     559 1814.45   582.1 1814.53   649.8 1818.61   674.2  1822.4   688.8 1825.69
   706.7  1833.6     750 1856.49   775.3 1867.99   801.5 1878.36   826.1 1886.29
#Mann= 7 ,-1 , 0
       0    .035       0      50      .1       0   236.1    .045       0
   254.1      .1       0  350.27     .06       0  370.27     .04       0
  470.69      .1       0
#XS Ineff= 2 , 0
                          334.33         1819.22
Permanent Ineff=
       F       F
Bank Sta=236.1,254.1
XS Rating Curve= 0 ,0
Exp/Cntr(USF)=0,0
Exp/Cntr=0.3,0.1

Type RM Length L Ch R = 1 ,23451   ,289,287.3,282.6
XS GIS Cut Line= 4
2032529.19124156282666.3905271972032616.31006093282813.723824657
2032735.93061041283056.1128328242032890.17816106283399.234935294
#Sta/Elev= 30
       0 1843.58    31.2  1833.5    46.1 1830.38    58.3 1828.98   103.8 1826.62
   163.7 1826.18   224.7 1823.88   230.7 1821.63     2511808.047   254.1 1807.07
   267.3 1806.66   274.5 1808.03   279.3 1809.24   296.6 1809.56   305.6 1810.62
   329.5 1810.69   340.5  1811.7   395.4 1811.02   431.9 1813.72   458.5 1813.98
   475.3 1812.45   514.5 1811.36   559.4 1808.88   643.8 1814.08   683.9  1819.9
   735.6 1832.67   750.5 1837.85   788.2 1853.32   809.8 1860.84   817.7 1864.34
#Mann= 8 ,-1 , 0
       0      .1       0     100    .035       0  211.16      .1       0
     251    .045       0   274.5      .1       0  321.16    .035       0
  431.16     .04       0  541.46      .1       0
#XS Ineff= 2 , 0
                          457.27         1817.08
Permanent Ineff=
       F       F
Bank Sta=251,274.5
XS Rating Curve= 0 ,0
Exp/Cntr(USF)=0,0
Exp/Cntr=0.3,0.1