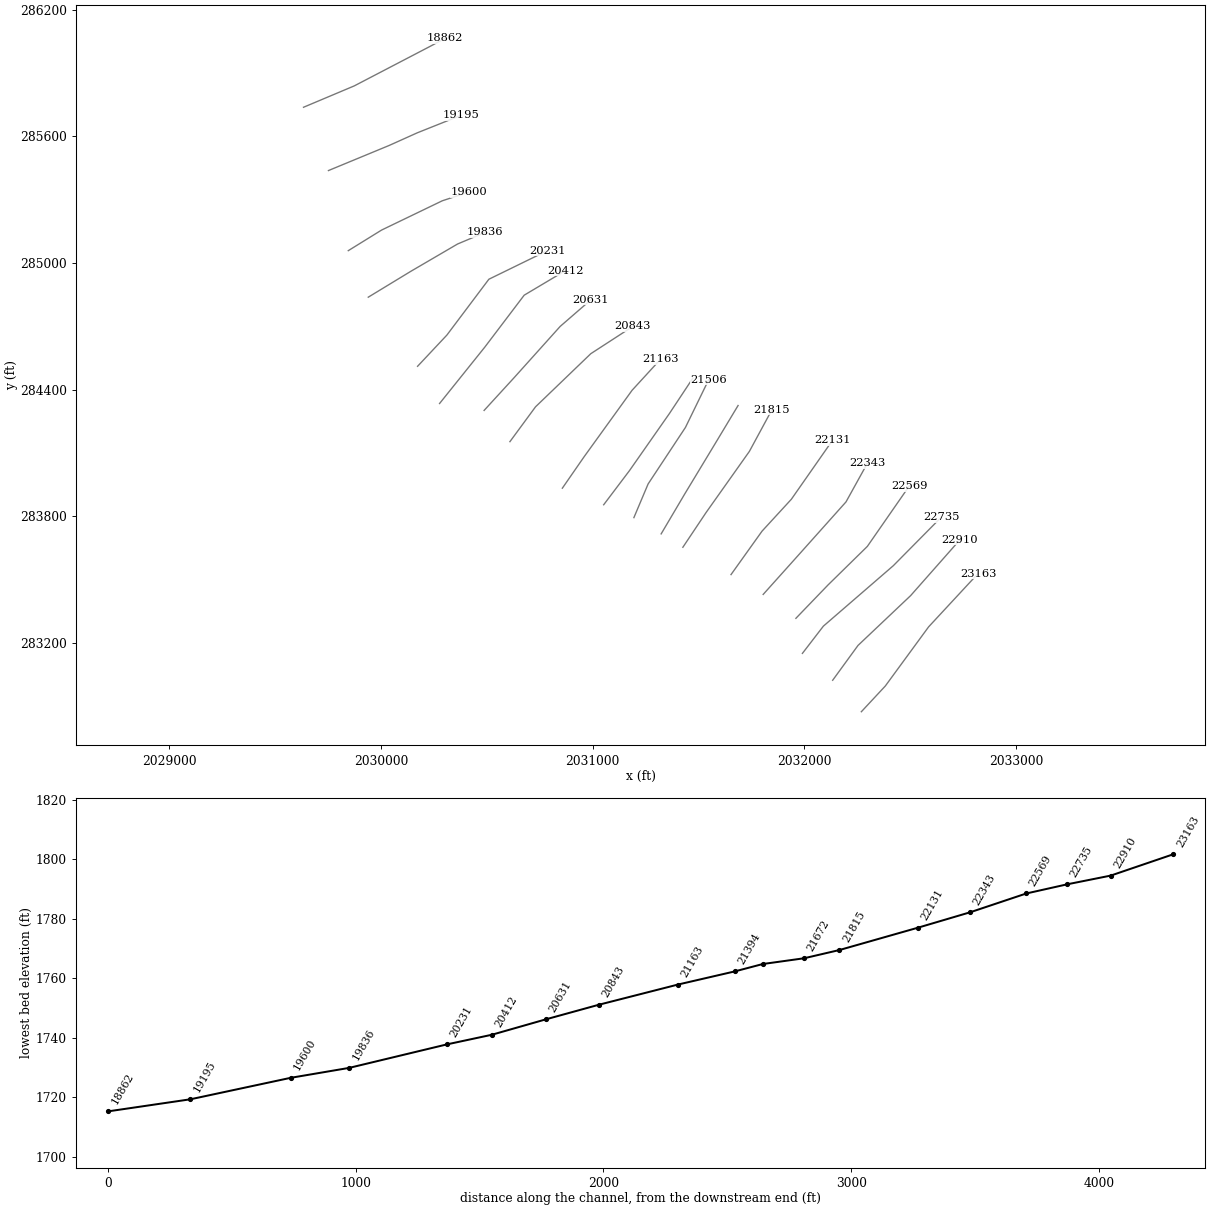
HEC-RAS study LICKCK1.prj: LICKCK1

--- LICKCK1.g01 (geometry) --- (continued)

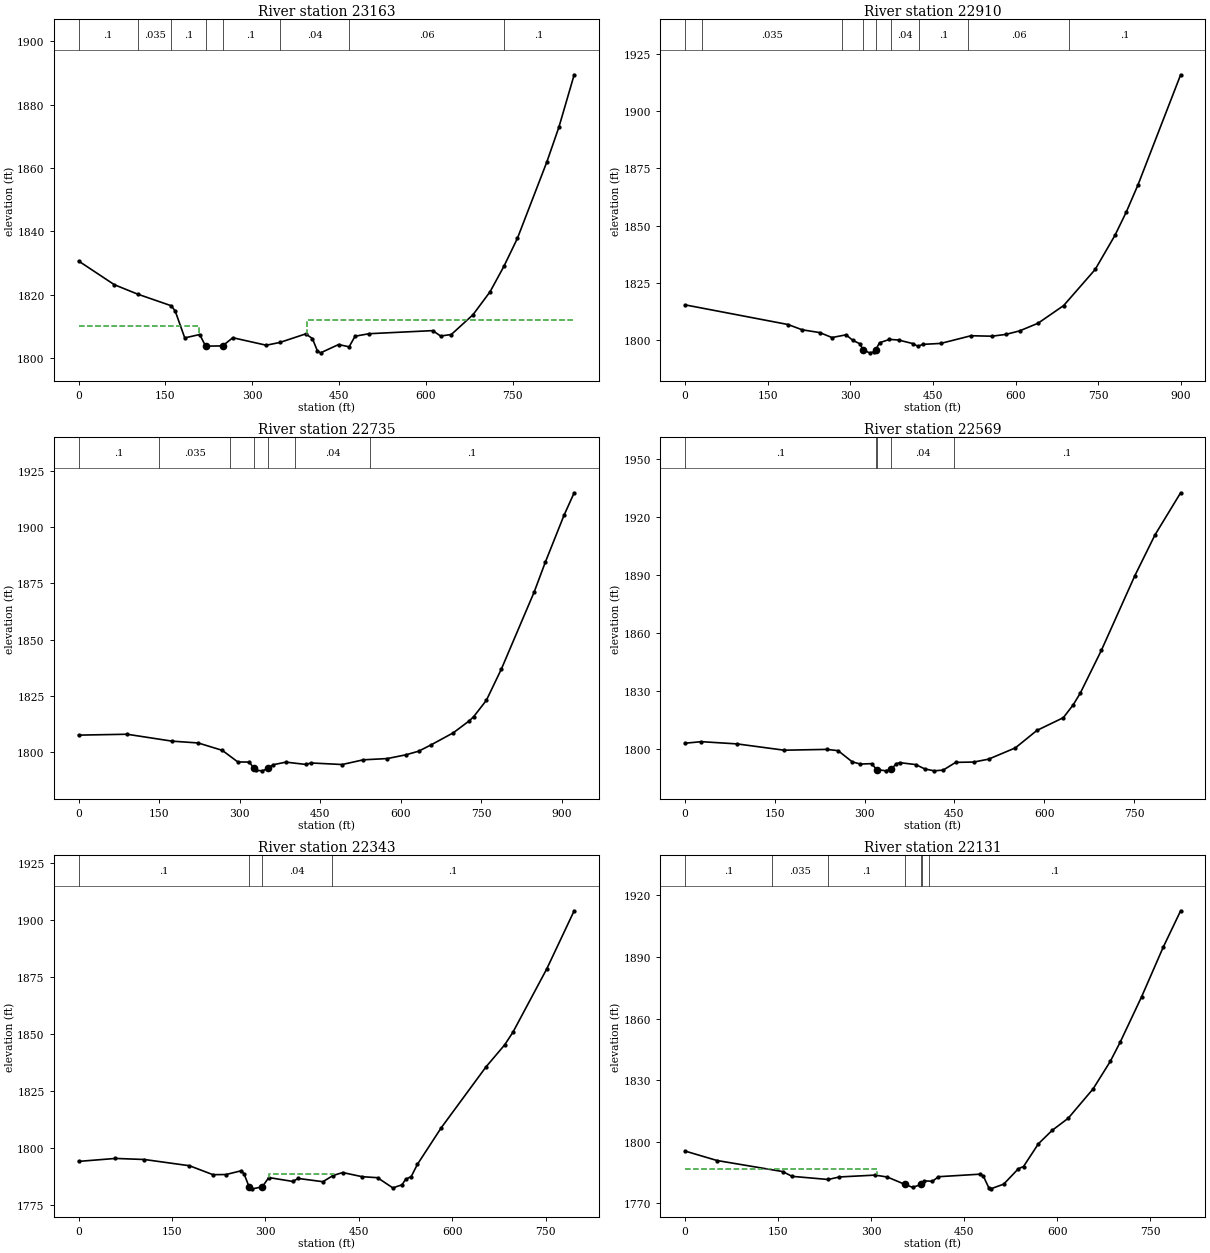
Type RM Length L Ch R = 1 ,23163   ,260.5,253.4,249.4
XS GIS Cut Line= 4
2032270.04087971282874.3444554852032383.36478035282996.302558082
2032587.97887816283276.4664766122032820.92415873 283528.29921237
#Sta/Elev= 30
       0 1830.68    61.8 1823.22   102.1 1820.25   160.3 1816.58     167 1814.89
   183.4 1806.47   209.3 1807.53   219.41803.879   248.71803.941   266.5 1806.52
   324.3 1804.16   347.8 1805.03   392.5 1807.73   404.1 1806.25   412.8 1802.31
   418.2 1801.76   449.4 1804.38   467.5 1803.65   477.8    1807   502.2 1807.79
     612 1808.76   625.6 1807.06   644.1 1807.53   681.6 1813.76   711.1    1821
     735    1829   758.3  1837.8   809.2 1861.87   830.2 1872.92   856.5 1889.37
#Mann= 8 ,-1 , 0
       0      .1       0   102.1    .035       0   160.3      .1       0
   219.4    .045       0   248.7      .1       0   347.8     .04       0
   467.5     .06       0     735      .1       0
#XS Ineff= 2 , 0
           208.4 1810.17   394.3         1812.03
Permanent Ineff=
       F       F
Bank Sta=219.4,248.7
XS Rating Curve= 0 ,0
Exp/Cntr(USF)=0,0
Exp/Cntr=0.3,0.1

Type RM Length L Ch R = 1 ,22910   ,174.6,175.2,173.5
XS GIS Cut Line= 4
2032134.53914573283023.3476387962032254.30050328283188.325019097
2032502.98532984 283424.418208872032735.93061041283688.842581415
#Sta/Elev= 30
       0  1815.5   186.7 1806.93   212.6 1804.61   244.3 1803.41   266.6 1801.25
   292.1 1802.43   304.4 1800.01   316.7 1798.58   323.41795.802   334.7 1794.57
   343.2 1795.01   345.61795.777   352.8 1798.97   370.9 1800.43   387.3 1800.17
     414 1798.56   422.1 1797.42   431.4 1798.27   463.9 1798.68   518.8 1802.03
   556.7 1801.83   582.2 1802.62     607 1804.15   640.4 1807.48   686.9 1815.19
   744.1 1830.94   779.9 1845.78   800.6 1856.02   821.7 1867.79   899.2 1915.88
#Mann= 9 ,-1 , 0
       0      .1       0      30    .035       0  283.86      .1       0
   323.4    .045       0   345.6      .1       0  373.86     .04       0
  423.86      .1       0  513.86     .06       0  696.77      .1       0
Bank Sta=323.4,345.6
XS Rating Curve= 0 ,0
Exp/Cntr(USF)=0,0
Exp/Cntr=0.3,0.1

Type RM Length L Ch R = 1 ,22735   ,162,165.4,162.3
XS GIS Cut Line= 4
2031991.61863385283150.6964065932032090.60922503283279.614385809
2032421.13969072283566.074122733 2032647.7891529283795.871494112
#Sta/Elev= 30
       0 1807.54    90.2 1807.93   173.9 1804.86   222.6 1804.05   267.4 1800.77
   296.4 1795.61   318.1 1795.54     3261792.731   331.1 1791.88   341.9 1791.65
     3531792.713   361.5 1794.33     386 1795.52   423.3 1794.49   432.6 1795.15
   490.7 1794.46   530.2 1796.56   574.7 1797.11     609 1798.76     633 1800.38
   655.7 1803.13   697.5 1808.55   727.6 1813.93   735.8 1815.82   759.2 1823.02
   787.2 1836.96   848.3 1871.25   869.1 1884.54   903.9  1905.4   922.7 1915.35
#Mann= 7 ,-1 , 0
       0      .1       0     150    .035       0  282.54      .1       0
     326    .045       0     353      .1       0  402.54     .04       0
  542.54      .1       0
Bank Sta=326,353
XS Rating Curve= 0 ,0
Exp/Cntr(USF)=0,0
Exp/Cntr=0.3,0.1

Type RM Length L Ch R = 1 ,22569   ,221.3,226.4,223.8
XS GIS Cut Line= 4
2031960.84326501283316.7620658712032112.64458941283474.784756021
2032298.37123203283657.3634894452032496.68951144 283943.82322637
#Sta/Elev= 30
       0 1802.84    27.1 1803.64      87 1802.48   165.5 1799.23   236.8 1799.65
   255.6 1798.99   279.4 1793.18     293 1792.06   311.6 1792.28   320.11789.229
   334.9  1788.6   343.91789.291     353 1792.22   358.5  1792.8   385.2  1791.8
   400.6 1789.55   416.1 1788.56   431.3 1788.95   452.1 1792.94   482.4 1793.11
     507 1794.59   551.8 1800.42   587.8 1809.44     632 1816.04   648.5 1822.68
   660.3 1828.72   695.6 1850.88   751.4 1889.39   785.2 1910.57     828 1932.31
#Mann= 5 ,-1 , 0
       0      .1       0  319.12     .04       0   320.1    .045       0
   343.9     .04       0  449.12      .1       0
Bank Sta=320.1,343.9
XS Rating Curve= 0 ,0
Exp/Cntr(USF)=0,0
Exp/Cntr=0.3,0.1

Type RM Length L Ch R = 1 ,22343   ,210.7,212.3,210.3
XS GIS Cut Line= 4
2031806.34839399283430.0237187562031964.69285716283606.996942294
2032197.63813773283868.2734056422032298.37123203284050.852139067
#Sta/Elev= 30
       0 1794.29    59.1 1795.59   105.6 1795.12     178 1792.39   215.8 1788.46
   236.8 1788.53   261.6 1790.21     266 1788.62   273.81783.182   279.2 1782.25
   294.91783.119   305.5  1787.2   343.6 1785.51   352.9  1786.8   392.4 1785.38
   408.7  1788.1   424.2  1789.4   455.2 1787.59   480.1 1787.14   504.7 1782.67
   519.5 1784.03   525.3 1786.46   534.3 1787.66   544.1 1792.96   582.5 1809.06
   654.4 1835.77   684.4 1845.44   697.6 1850.96   751.9 1878.72     796 1904.25
#Mann= 4 ,-1 , 0
       0      .1       0   273.8    .045       0   294.9     .04       0
  407.47      .1       0
#XS Ineff= 1 ,-1
  306.16  410.791788.571
Permanent Ineff=
       F
Bank Sta=273.8,294.9
XS Rating Curve= 0 ,0
Exp/Cntr(USF)=0,0
Exp/Cntr=0.3,0.1

Type RM Length L Ch R = 1 ,22131   ,312.3,315.8,316.1
XS GIS Cut Line= 4
2031654.34540029283523.8826886742031801.00157891283729.765400976
2031939.50958358 283880.865042432032134.67995379284161.028960961
#Sta/Elev= 30
       0 1795.44    51.6 1790.83   157.2 1785.46   172.5 1783.12   230.7 1781.59
     249 1782.83   306.5 1783.72   326.1 1782.79  354.57 1779.19   366.9 1777.76
   380.9 1779.17   385.5 1780.95   398.9 1780.69   408.6 1782.94   476.4 1784.19
   481.1 1783.17   489.8 1777.57   492.9 1777.03   513.8 1779.31   537.6 1786.85
   545.8 1787.91   569.8 1798.99   591.8 1805.49   617.8 1811.41     658 1825.74
   685.7 1839.13   701.7 1848.51   736.3 1870.68   770.9 1894.67   799.2 1912.55
#Mann= 7 ,-1 , 0
       0      .1       0     140    .035       0     230      .1       0
  354.57    .045       0   380.9      .1       0  382.78     .04       0
  392.78      .1       0
#XS Ineff= 2 , 0
          309.45 1786.85
Permanent Ineff=
       F       F
Bank Sta=354.57,380.9
XS Rating Curve= 0 ,0
Exp/Cntr(USF)=0,0
Exp/Cntr=0.3,0.1

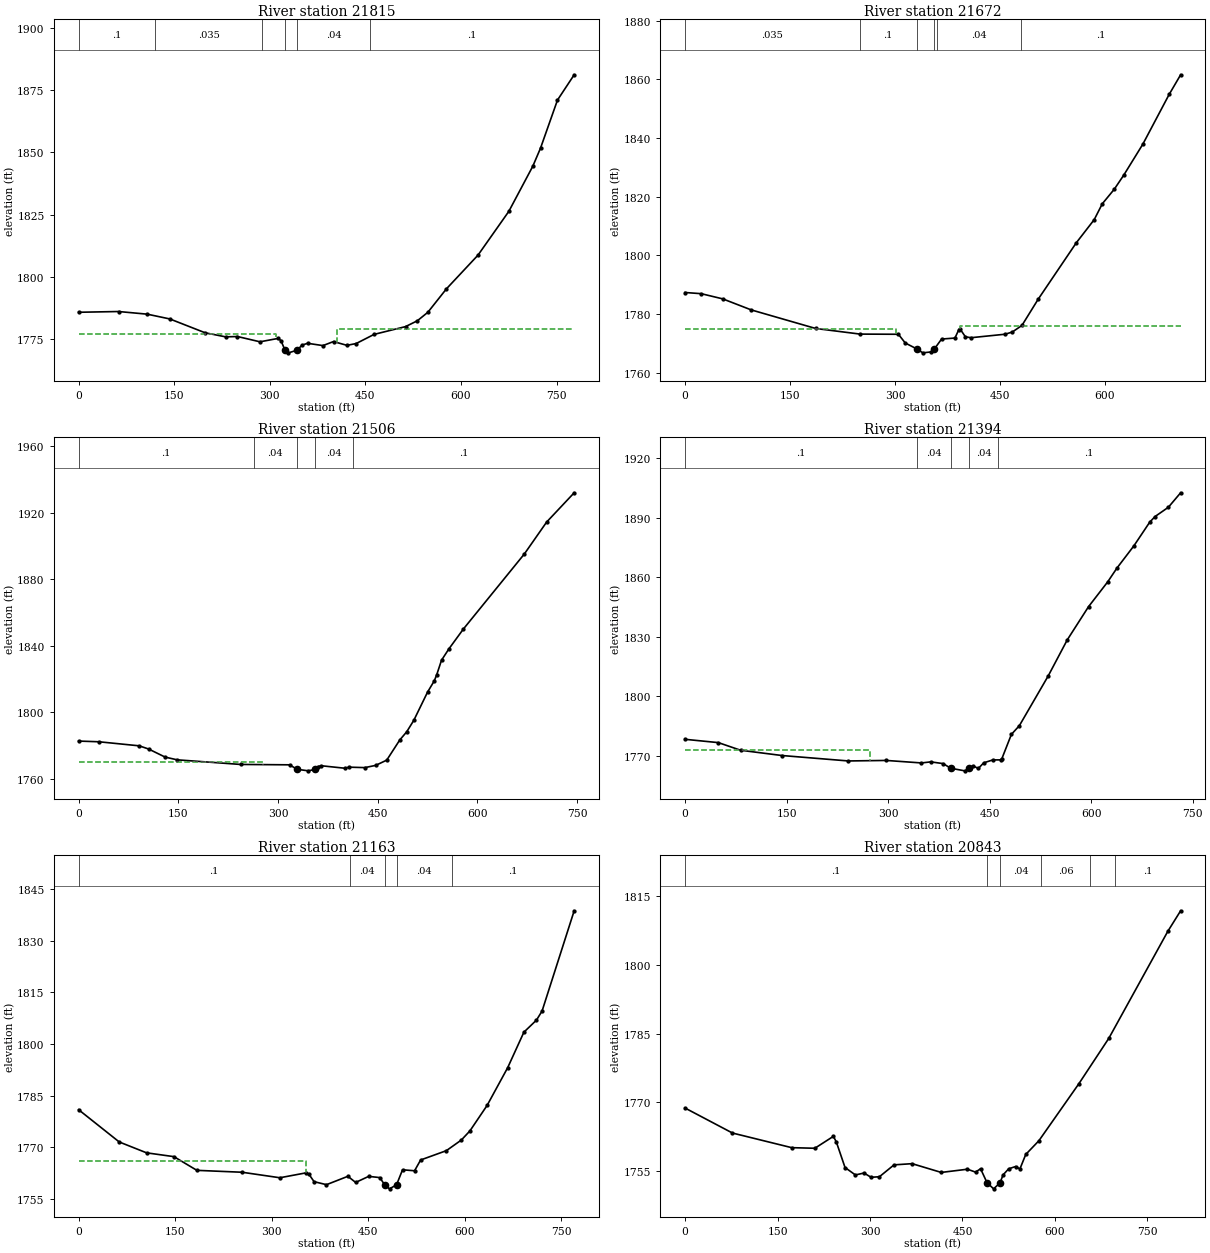
Type RM Length L Ch R = 1 ,21815   ,141.7,142.7,144.2
XS GIS Cut Line= 4
2031426.87696235283653.3564924642031536.57720637283817.906858491
2031741.19130417284107.5145046122031848.22021687284305.832784021
#Sta/Elev= 30
       0 1785.84    62.7 1786.14   107.6 1785.08   143.1 1783.16   198.6  1777.6
   230.7 1775.97   249.3  1776.1   284.6 1773.98   312.9 1775.33   317.6 1774.45
   323.81770.631   329.3 1769.55   342.9 1770.61   350.5 1772.64   359.3 1773.38
   383.4 1772.46     400 1774.08   421.1 1772.56   435.6 1773.29   463.7 1776.96
     513 1780.08   531.5 1782.41   548.1 1785.84   577.2 1795.24   626.7 1808.76
   675.1 1826.34   712.8 1844.49   724.9 1851.75   751.5 1871.04   777.7  1881.2
#Mann= 6 ,-1 , 0
       0      .1       0     120    .035       0  287.76      .1       0
   323.8    .045       0   342.9     .04       0  457.76      .1       0
#XS Ineff= 2 , 0
          310.09 1777.22   405.4         1779.22
Permanent Ineff=
       F       F
Bank Sta=323.8,342.9
XS Rating Curve= 0 ,0
Exp/Cntr(USF)=0,0
Exp/Cntr=0.3,0.1

Type RM Length L Ch R = 1 ,21672   ,166.9,166.5,165.3
XS GIS Cut Line= 4
2031324.31137476283716.7361697962031435.84411206283906.048316006
2031583.79584432 284151.585233372031687.67684782284324.720239203
#Sta/Elev= 30
       0 1787.35      23 1786.95    53.8 1785.18    94.5 1781.42   186.7 1775.08
   250.2 1773.17   304.9 1773.11   314.7 1770.13   330.91768.153   339.8 1766.78
   351.2 1767.08   356.41768.136   366.6 1771.48   385.7 1771.82   391.2 1774.67
   393.4 1774.78   400.7 1772.23   408.7 1771.94   457.5 1773.13   467.7 1773.88
   481.5 1776.13   504.5    1785   559.3 1804.35   584.8  1812.2   596.3 1817.59
   613.5 1822.58   626.9 1827.33   654.2 1837.89   691.9 1854.89   708.3 1861.58
#Mann= 6 ,-1 , 0
       0    .035       0  249.72      .1       0   330.9    .045       0
   356.4      .1       0  359.72     .04       0  479.72      .1       0
#XS Ineff= 2 , 0
          300.82 1774.75  392.89         1775.91
Permanent Ineff=
       F       F
Bank Sta=330.9,356.4
XS Rating Curve= 0 ,0
Exp/Cntr(USF)=0,0
Exp/Cntr=0.3,0.1

Type RM Length L Ch R = 1 ,21506   ,110.4,112,116.6
XS GIS Cut Line= 4
2031195.52439439283793.7032633272031262.70910623283953.266953961
2031438.99202126284220.8392357032031549.16884316284447.488697885
#Sta/Elev= 30
       0 1782.76    30.5 1782.34    91.1  1779.9   105.3 1777.98   130.2 1773.11
   148.4 1771.47   243.6  1768.7   317.3 1768.47   328.91765.757   345.8 1764.85
   355.2 1765.72   360.5 1767.46   365.2 1767.91   400.8 1766.41   406.7 1767.06
   430.6 1766.79   446.9 1768.13   463.6  1771.3   483.3 1783.48   493.6 1788.32
   504.4  1795.3     525 1812.22   535.1 1818.98   538.7 1822.56     546 1831.39
     557 1838.16     579 1850.22   670.7 1895.36   704.2 1914.54   745.6 1932.14
#Mann= 5 ,-1 , 0
       0      .1       0  263.13     .04       0   328.9    .045       0
   355.2     .04       0  413.13      .1       0
#XS Ineff= 2 , 0
           276.9 1770.32
Permanent Ineff=
       F       F
Bank Sta=328.9,355.2
XS Rating Curve= 0 ,0
Exp/Cntr(USF)=0,0
Exp/Cntr=0.3,0.1

Type RM Length L Ch R = 1 ,21394   ,232.2,230.3,221.5
XS GIS Cut Line= 4
2031052.80711566283854.7060634322031174.56764872  284016.2251379
2031363.44220053 284286.945328842031473.61902243284453.784516279
#Sta/Elev= 30
       0 1778.28    49.2 1776.61    82.1 1772.76   143.2 1770.11   241.3 1767.37
   297.3 1767.63   349.3 1766.37     363 1766.91   381.3 1766.04   392.51763.697
   413.3 1762.39   419.5 1763.57   425.3 1764.95   433.3 1763.57   441.3 1766.43
   454.8  1767.9   466.2 1767.91   468.1  1768.5   482.2 1780.76     494 1785.17
   536.4  1810.1   564.8 1828.43   596.2 1845.14   624.5 1857.63   638.2  1864.6
   663.1 1875.74   686.6 1887.72   694.5 1890.57   714.2 1895.25   732.3 1902.54
#Mann= 5 ,-1 , 0
       0      .1       0  342.27     .04       0   392.5    .045       0
   419.5     .04       0  462.27      .1       0
#XS Ineff= 2 , 0
          273.46 1773.02
Permanent Ineff=
       F       F
Bank Sta=392.5,419.5
XS Rating Curve= 0 ,0
Exp/Cntr(USF)=0,0
Exp/Cntr=0.3,0.1

Type RM Length L Ch R = 1 ,21163   ,320.5,320.4,316.2
XS GIS Cut Line= 4
2030857.50853468283933.1569509392030960.50982332284082.331231036
 2031187.1592855284397.1221507332031322.51938097284545.073882991
#Sta/Elev= 30
       0 1780.93    63.1 1771.56   105.5 1768.41     148  1767.3   183.7 1763.32
   253.9 1762.77   312.6 1761.17   352.6 1762.57   357.6 1762.22   365.7 1760.03
     385 1759.16   418.2 1761.59   430.3 1759.81   450.5 1761.57   467.8 1761.22
   475.41759.104   482.9 1757.95   493.81759.124   503.1 1763.48   521.8  1763.2
   531.2 1766.33   571.2 1769.04   594.4 1772.12   607.7 1774.76   634.4 1782.16
   666.4 1793.13   691.6 1803.45   711.1 1806.95   719.8 1809.57   769.7 1838.71
#Mann= 5 ,-1 , 0
       0      .1       0  421.28     .04       0   475.4    .045       0
   493.8     .04       0  579.18      .1       0
#XS Ineff= 2 , 0
          352.62  1766.1
Permanent Ineff=
       F       F
Bank Sta=475.4,493.8
XS Rating Curve= 0 ,0
Exp/Cntr(USF)=0,0
Exp/Cntr=0.3,0.1

Type RM Length L Ch R = 1 ,20843   ,211.6,211.9,213.5
XS GIS Cut Line= 4
2030609.78327502284153.5209977262030730.71245194284318.424420809
2030991.98891529284570.257156567 2031190.3071947284699.321433643
#Sta/Elev= 30
       0 1768.76    76.9 1763.31     173 1760.12   210.5 1759.99   240.6 1762.59
   245.4 1761.36   259.5 1755.79   276.3 1754.17   290.3 1754.59   301.7 1753.66
   315.3 1753.78     339 1756.37   368.3 1756.63   415.6 1754.72   458.1 1755.42
   471.2 1754.79   479.4 1755.52   489.91752.474   500.6 1751.14   511.1 1752.47
   515.8 1754.17   524.9  1755.5   536.2 1756.01   543.2 1755.47   552.7 1758.64
     574 1761.63   638.9 1774.07   687.5 1783.98   783.2 1807.31     804 1811.79
#Mann= 6 ,-1 , 0
       0      .1       0   489.9    .045       0   511.1     .04       0
  577.38     .06       0  657.38    .035       0  697.38      .1       0
Bank Sta=489.9,511.1
XS Rating Curve= 0 ,0
Exp/Cntr(USF)=0,0
Exp/Cntr=0.3,0.1

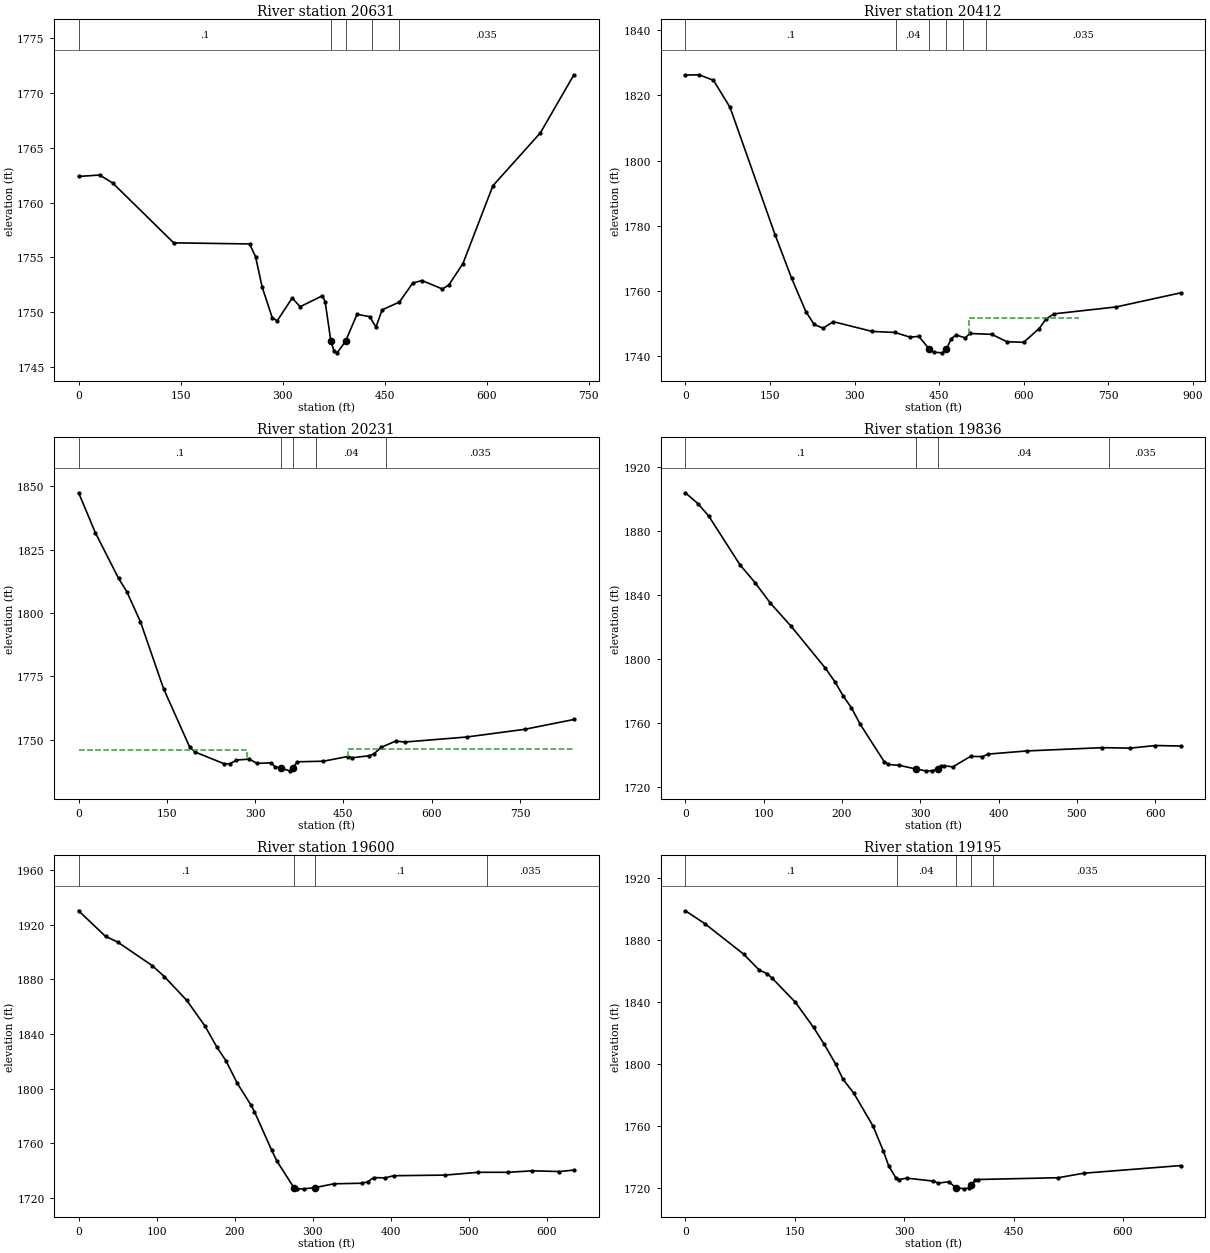
Type RM Length L Ch R = 1 ,20631   ,217.2,219.2,218.2
XS GIS Cut Line= 4
2030487.85276397284301.4292112272030629.97935764284456.932425476
2030847.18509223284699.3214336432030991.98891529284825.237801521
#Sta/Elev= 30
       0 1762.38    30.9 1762.51    50.3 1761.77   139.7 1756.32   251.2 1756.22
     260 1755.07   269.8 1752.28   284.5  1749.5   291.8  1749.2   313.9 1751.28
   325.6 1750.49   358.3 1751.49   362.3 1750.96   370.81747.338   375.5 1746.41
     380 1746.28   392.41747.345   409.2  1749.8   427.8 1749.58   437.1 1748.63
     446  1750.2   471.4 1750.91     491 1752.64   504.5 1752.88   534.7 1752.11
   544.1 1752.47   564.9 1754.43   608.9 1761.53   678.7 1766.36     728 1771.66
#Mann= 5 ,-1 , 0
       0      .1       0   370.8    .045       0   392.4      .1       0
  430.67     .04       0  470.67    .035       0
Bank Sta=370.8,392.4
XS Rating Curve= 0 ,0
Exp/Cntr(USF)=0,0
Exp/Cntr=0.3,0.1

Type RM Length L Ch R = 1 ,20412   ,180.4,181,181.6
XS GIS Cut Line= 4
2030277.41352758284334.1639667942030491.47135297284601.736248537
2030677.19799559  284847.27316592030872.54361698284963.850391568
#Sta/Elev= 30
       0 1826.21    24.1  1826.3    49.8 1824.62    79.2 1816.31     159 1777.29
   188.4 1763.92   213.6 1753.71   228.4 1749.76   244.2 1748.62   262.2 1750.62
   331.3 1747.63   371.2 1747.33   398.4 1745.87   413.8 1746.12   432.71742.171
   439.9 1741.28   454.9 1741.07   462.81742.176   471.4  1745.4   479.9 1746.57
   496.1 1745.63   504.3    1747     543 1746.74   570.1 1744.49   599.6 1744.29
   627.3 1748.53     639 1751.38   653.4 1753.02   763.7 1755.14     878 1759.46
#Mann= 6 ,-1 , 0
       0      .1       0  372.66     .04       0   432.7    .045       0
   462.8     .04       0  492.66      .1       0  532.66    .035       0
#XS Ineff= 1 ,-1
   502.9   697.81751.767
Permanent Ineff=
       T
Bank Sta=432.7,462.8
XS Rating Curve= 0 ,0
Exp/Cntr(USF)=0,0
Exp/Cntr=0.3,0.1

Type RM Length L Ch R = 1 ,20231   ,398.4,395.2,384.9
XS GIS Cut Line= 4
2030173.53252408284510.4468818242030312.04052875284658.398614082
2030510.35880816284922.822986628 2030787.4070763285058.490952987
#Sta/Elev= 30
       0 1847.35    28.5 1831.59    67.9 1813.62    81.9  1808.4   105.1 1796.54
   144.3 1770.24   188.6 1747.27   197.6 1745.27   247.1 1740.65     257 1740.59
   268.2 1742.09   289.8 1742.45   303.3 1740.77   326.8    1741     334 1739.38
   343.91738.908   358.6 1737.84   364.11738.904   371.3  1741.4   415.8 1741.63
     457 1743.47   465.2    1743   493.9 1743.79   502.1 1744.58   514.4 1747.14
   538.6 1749.52   555.1  1749.2   659.2 1751.16   757.8 1754.18   841.7 1758.07
#Mann= 5 ,-1 , 0
       0      .1       0   343.9    .045       0   364.1      .1       0
  402.67     .04       0  522.67    .035       0
#XS Ineff= 2 , 0
          285.46 1745.86  457.57         1746.34
Permanent Ineff=
       F       F
Bank Sta=343.9,364.1
XS Rating Curve= 0 ,0
Exp/Cntr(USF)=0,0
Exp/Cntr=0.3,0.1

Type RM Length L Ch R = 1 ,19836   ,236.5,236,233.4
XS GIS Cut Line= 4
 2029940.5872435284837.8294383092030142.05343211284960.597896991
 2030362.4070759285089.6621740672030492.46534537285144.624036896
#Sta/Elev= 30
       0 1904.13      16 1897.37    29.8 1889.58    69.7 1859.04      89 1847.85
   108.6 1834.99   135.1 1820.49   178.6 1794.39   191.2 1785.58   201.7 1776.73
   211.9 1769.56   223.4 1759.05     254 1735.62   259.1 1733.92     273 1733.39
   294.11731.132   306.7 1729.93   314.8 1729.95   322.51731.094   326.2 1732.81
     330 1733.18   341.4 1732.38   364.2 1738.98   379.4 1738.84     387 1740.43
   436.5 1742.41   532.5 1744.45   568.2 1744.15   600.2 1745.79   632.5 1745.48
#Mann= 4 ,-1 , 0
       0      .1       0   294.1    .045       0   322.5     .04       0
  541.29    .035       0
Bank Sta=294.1,322.5
XS Rating Curve= 0 ,0
Exp/Cntr(USF)=0,0
Exp/Cntr=0.3,0.1

Type RM Length L Ch R = 1 ,19600   ,404.8,404.4,401.2
XS GIS Cut Line= 4
2029846.14996759285058.1830820972030003.54542744285155.768267203
2030290.00516437 285294.276271872030414.81135565285335.546845082
#Sta/Elev= 30
       0 1930.14    34.5 1911.39    49.9 1907.29    94.4 1889.99   109.9 1881.95
   138.7 1864.47   161.9 1845.79   177.3 1830.28   188.7 1820.45   203.4 1803.84
   220.5 1788.25   225.4 1783.04   247.5 1754.76   254.3 1746.73   275.81727.535
   279.8 1726.67   289.3 1726.59     3031727.509   327.2 1730.28   363.6  1730.7
   370.9 1731.86   378.2 1734.84   392.8 1734.61   403.7  1736.2   469.3 1736.64
   512.5 1738.71   550.6  1738.7   581.7 1739.79   616.2 1739.26   634.8 1740.31
#Mann= 4 ,-1 , 0
       0      .1       0   275.8    .045       0     303      .1       0
  523.38    .035       0
Bank Sta=275.8,303
XS Rating Curve= 0 ,0
Exp/Cntr(USF)=0,0
Exp/Cntr=0.3,0.1

Type RM Length L Ch R = 1 ,19195   ,331.8,333,334.2
XS GIS Cut Line= 4
2029752.51903709285437.6211069042030039.89786263285556.715034606
2030171.93678248285616.2619984572030379.05665674285699.109948162
#Sta/Elev= 30
       0 1899.04    26.6 1890.76    79.8 1871.05   101.1 1860.81   111.8 1858.43
   118.9 1855.55   150.9  1839.9   175.7  1823.7   189.9 1813.13   205.9 1800.15
   215.9 1790.37     231 1781.11   257.4 1759.82   271.6 1743.62   278.7 1734.24
   288.7 1726.38   292.9  1725.4   303.8 1726.28   339.5 1724.41   346.7 1723.07
   360.9 1723.96   370.8 1720.23   382.6 1719.38   388.2 1719.91   391.91721.789
     397 1724.86   400.6 1725.41   511.2 1726.56     546 1729.47     679 1734.41
#Mann= 5 ,-1 , 0
       0      .1       0     290     .04       0   370.8    .045       0
   391.9     .04       0  421.08    .035       0
Bank Sta=370.8,391.9
XS Rating Curve= 0 ,0
Exp/Cntr(USF)=0,0
Exp/Cntr=0.3,0.1

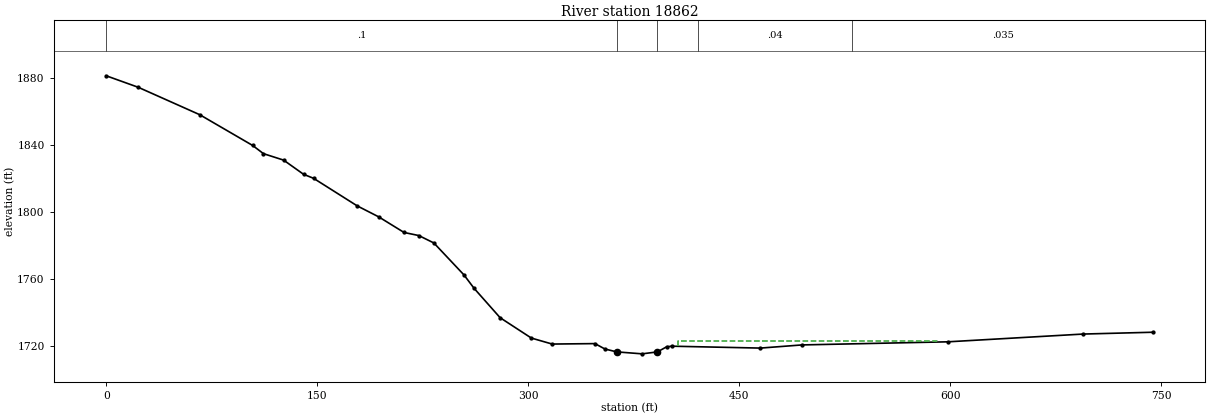
Type RM Length L Ch R = 1 ,18862   ,540.5,543,540.8
XS GIS Cut Line= 4
2029634.65022824285737.3555398662029874.54576223285838.644765327
2030231.72355728286025.2301806492030302.77946007286063.432278924
#Sta/Elev= 30
       0 1881.58    22.8 1874.69    66.5  1858.3   104.1 1839.91   111.8    1835
   126.1 1831.15   140.3 1822.66   147.4 1820.27   178.4 1803.79   193.7 1797.22
   211.7 1787.89   222.2 1786.04   232.9 1781.61   254.3  1762.5   261.5 1754.47
     280 1736.91   302.2 1724.74     317 1721.16   347.4 1721.43   354.5 1718.19
   362.91716.479   380.9 1715.31   391.81716.465   398.4 1719.54   402.1 1719.88
     465 1718.75   494.6 1720.64   598.3  1722.5   694.4 1727.14   744.1 1728.23
#Mann= 5 ,-1 , 0
       0      .1       0   362.9    .045       0   391.8      .1       0
   420.4     .04       0   530.4    .035       0
#XS Ineff= 1 ,-1
  406.24  590.391722.855
Permanent Ineff=
       T
Bank Sta=362.9,391.8
XS Rating Curve= 0 ,0
Exp/Cntr(USF)=0,0
Exp/Cntr=0.3,0.1