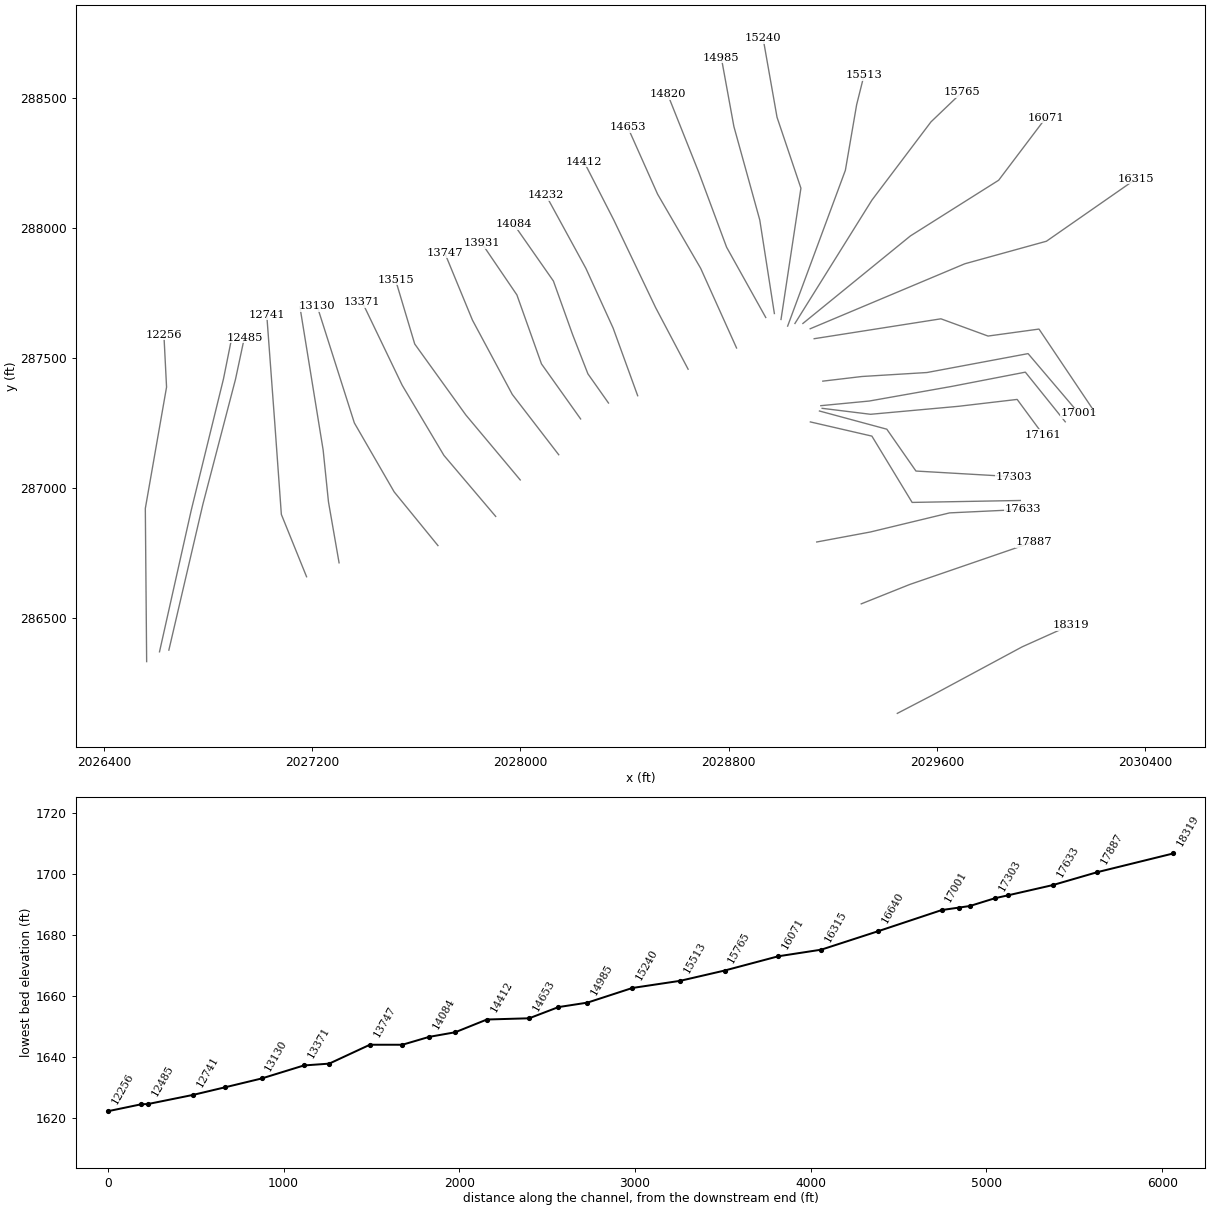
HEC-RAS study LICKCK1.prj: LICKCK1

--- LICKCK1.g01 (geometry) --- (continued)

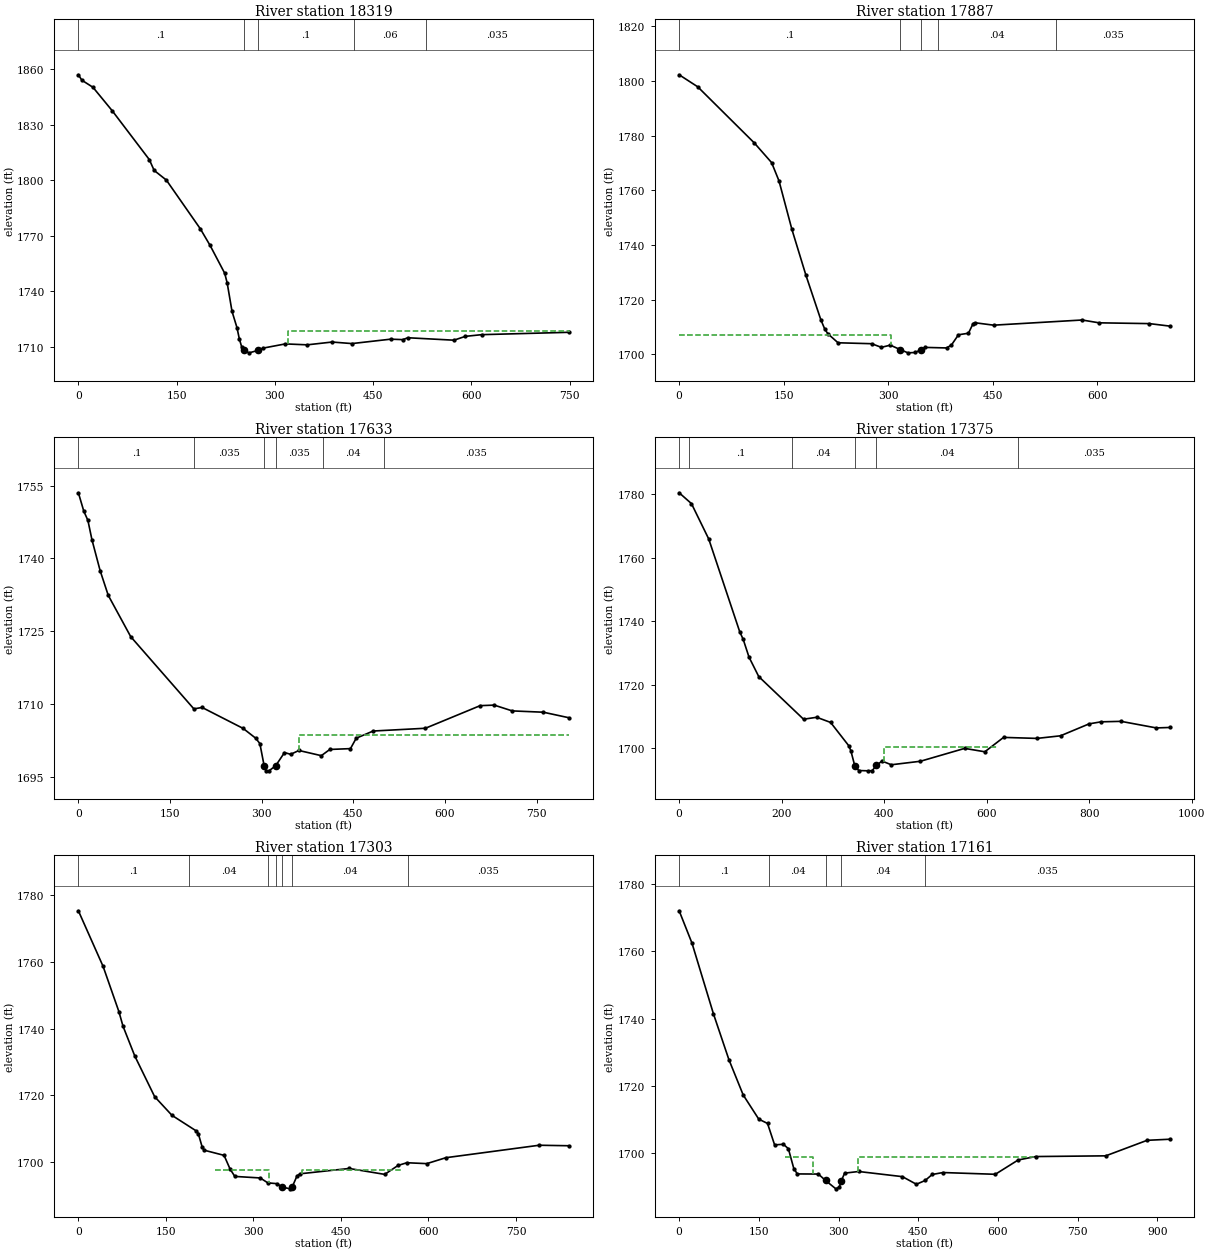
Type RM Length L Ch R = 1 ,18319   ,432.4,432.7,427.8
XS GIS Cut Line= 4
2029448.06481292286131.8504179772029581.34010958286201.153572239
2029927.85588089286387.7389875622030114.73731309286471.749906624
#Sta/Elev= 30
       0 1857.05     5.3 1854.12    22.3 1850.27    51.5 1837.68   108.3 1811.19
   115.7 1805.33   134.3 1800.12   186.2 1773.76   201.1 1764.77   223.4 1749.74
   227.2 1744.48   234.6 1729.08   242.1 1720.39   245.8 1714.16   249.5 1709.73
   252.5 1707.97   260.7 1706.69   273.91707.966   282.1 1709.25     316 1711.52
   349.4 1711.02   387.4 1712.53   417.7  1711.7   476.8 1714.08   495.5 1713.83
   502.9 1714.85   573.4 1713.53   590.8  1715.6   615.8 1716.52   748.7 1717.79
#Mann= 5 ,-1 , 0
       0      .1       0   252.5    .045       0   273.9      .1       0
  420.22     .06       0  530.22    .035       0
#XS Ineff= 2 , 0
                          320.24         1718.44
Permanent Ineff=
       F       F
Bank Sta=252.5,273.9
XS Rating Curve= 0 ,0
Exp/Cntr(USF)=0,0
Exp/Cntr=0.3,0.1

Type RM Length L Ch R = 1 ,17887   ,253.3,253.4,255.3
XS GIS Cut Line= 3
 2029309.4585044 286553.000355422029496.04391972286627.634521549
2029971.00991835 286791.06368237
#Sta/Elev= 30
       0 1802.26    26.6 1797.87   107.9  1777.3   132.6 1770.13   143.2 1763.45
   161.7 1745.71   181.9 1728.87   203.2 1712.65     209 1709.14   213.6 1707.45
   227.9 1704.23   276.1 1703.89     290 1702.56   302.8 1703.36   317.11701.742
   328.1 1700.55   338.9 1700.68   346.41701.708   352.4 1702.54   383.6 1702.34
   390.6 1703.44   400.6 1707.16   414.9 1707.72   421.5  1711.2   424.1 1711.56
     451 1710.67   577.9 1712.56   602.2 1711.53   674.5 1711.24   703.3 1710.34
#Mann= 5 ,-1 , 0
       0      .1       0   317.1    .045       0   346.4    .035       0
  370.96     .04       0  540.96    .035       0
#XS Ineff= 2 , 0
          303.45 1707.12
Permanent Ineff=
       F       F
Bank Sta=317.1,346.4
XS Rating Curve= 0 ,0
Exp/Cntr(USF)=0,0
Exp/Cntr=0.3,0.1

Type RM Length L Ch R = 1 ,17633   ,283.9,258.1,227.3
XS GIS Cut Line= 4
 2029138.3847343286790.9191502062029344.74767055286829.393595947
2029649.04555959286902.8448105432029928.44108413286916.089336357
#Sta/Elev= 30
       0 1753.51     8.9 1749.72    15.6 1747.83    22.2 1743.86    35.6  1737.5
    48.9 1732.41    85.7 1723.91   189.1 1709.05   202.5 1709.35   269.8 1705.03
   290.1 1703.04   297.1 1701.92   304.11697.342     307 1696.37     312 1696.31
     3231697.361   337.4 1700.07   347.5 1699.71     361  1700.5   397.7 1699.43
   411.6 1700.71   445.4 1700.88   454.8 1703.02   482.5  1704.5   568.1 1705.07
   657.7 1709.72   680.7 1709.83   710.2 1708.64   761.1 1708.37   802.7 1707.24
#Mann= 6 ,-1 , 0
       0      .1       0     190    .035       0   304.1    .045       0
     323    .035       0  399.92     .04       0  499.92    .035       0
#XS Ineff= 2 , 0
                          361.32         1703.76
Permanent Ineff=
       F       F
Bank Sta=304.1,323
XS Rating Curve= 0 ,0
Exp/Cntr(USF)=0,0
Exp/Cntr=0.5,0.3

Type RM Length L Ch R = 1 ,17375   ,70.4,72.7,77
XS GIS Cut Line= 4
 2029113.9009961287252.6124990952029350.34395356287198.048739681
 2029504.9412719286943.0680947262029920.78652955286950.562029579
#Sta/Elev= 30
       0 1780.45      24 1777.04    57.7 1765.91   118.3 1736.64     125 1734.29
   136.3 1728.71   155.3 1722.59   242.7 1709.16   268.4 1709.77   295.5 1708.15
   331.2 1700.76     335 1699.24   342.7 1694.48   350.4 1693.01   369.4 1692.91
   376.7 1692.99   384.9 1694.61   395.8    1696   413.9 1694.82   470.8 1695.93
   557.1 1699.98   596.4 1698.91     633 1703.44   698.1 1703.12   744.1 1703.94
   799.9  1707.7   823.2 1708.34   862.2 1708.49   931.1 1706.42   956.8 1706.56
#Mann= 6 ,-1 , 0
       0    .035       0      20      .1       0     220     .04       0
   342.7    .045       0   384.9     .04       0  660.84    .035       0
#XS Ineff= 2 ,-1
  295.97  330.121700.536     399  621.551700.545
Permanent Ineff=
       F       F
Bank Sta=342.7,384.9
XS Rating Curve= 0 ,0
Exp/Cntr(USF)=0,0
Exp/Cntr=0.5,0.3

Type RM Length L Ch R = 1 ,17303   ,123.7,141.5,158.8
XS GIS Cut Line= 4
2029148.87776496287294.5846217212029407.70585449287224.631084011
2029519.63151482287063.7379472772029895.31683609287041.994102316
#Sta/Elev= 30
       0 1775.28    42.4 1758.61    69.5 1745.05    76.4 1740.75    96.7 1731.77
   130.7  1719.6   160.4    1714   202.1 1709.32   205.5 1708.54   212.3 1704.43
   215.7 1703.55   249.7 1702.01   259.9 1697.94   268.1  1695.7   311.6 1695.24
   324.7 1693.77   340.4 1693.53   348.7 1692.51   363.3 1691.98   366.5 1692.56
   374.8 1695.89   380.6  1696.5   464.1 1698.08     525 1696.31   547.8 1698.98
   562.9  1699.8   597.1 1699.53   629.9 1701.31   789.7 1705.04   840.4 1704.89
#Mann= 7 ,-1 , 0
       0      .1       0     190     .04       0   324.7    .035       0
  338.11     .04       0   348.7    .045       0   366.5     .04       0
  564.11    .035       0
#XS Ineff= 2 ,-1
  234.04  326.141697.579  383.97  555.291697.533
Permanent Ineff=
       F       F
Bank Sta=348.7,366.5
XS Rating Curve= 0 ,0
Exp/Cntr(USF)=0,0
Exp/Cntr=0.5,0.3

Type RM Length L Ch R = 1 ,17161   ,61.8,63.9,63.1
XS GIS Cut Line= 5
 2029159.2072032287304.9159363592029345.34307401287281.967678313
2029681.91752535287312.5653557082029908.58386235287339.162782531
2030008.75504403287203.084652044
#Sta/Elev= 30
       0 1772.02    24.2 1762.39    64.6 1741.38    93.6 1727.82   120.5 1717.32
   149.8 1710.14   166.3 1708.86   179.6  1702.5   196.1 1702.67   205.5 1701.37
   215.8 1695.43   222.4 1693.87   261.9 1693.83   275.4 1691.93   294.9 1689.44
   301.5 1689.96  305.31 1691.91   311.4  1694.1   337.7 1694.59   420.1 1693.06
   446.4  1690.8   462.9 1691.92   476.1  1693.7   496.4 1694.28   594.9 1693.76
   637.9 1698.01   670.8 1699.03   802.7 1699.24   880.5 1703.85   922.7 1704.17
#Mann= 5 ,-1 , 0
       0      .1       0     170     .04       0   275.4    .045       0
  305.31     .04       0   462.9    .035       0
#XS Ineff= 2 ,-1
  199.43  252.281698.942  336.99666.93571698.849
Permanent Ineff=
       T       T
Bank Sta=275.4,305.31
XS Rating Curve= 0 ,0
Exp/Cntr(USF)=0,0
Exp/Cntr=0.5,0.3

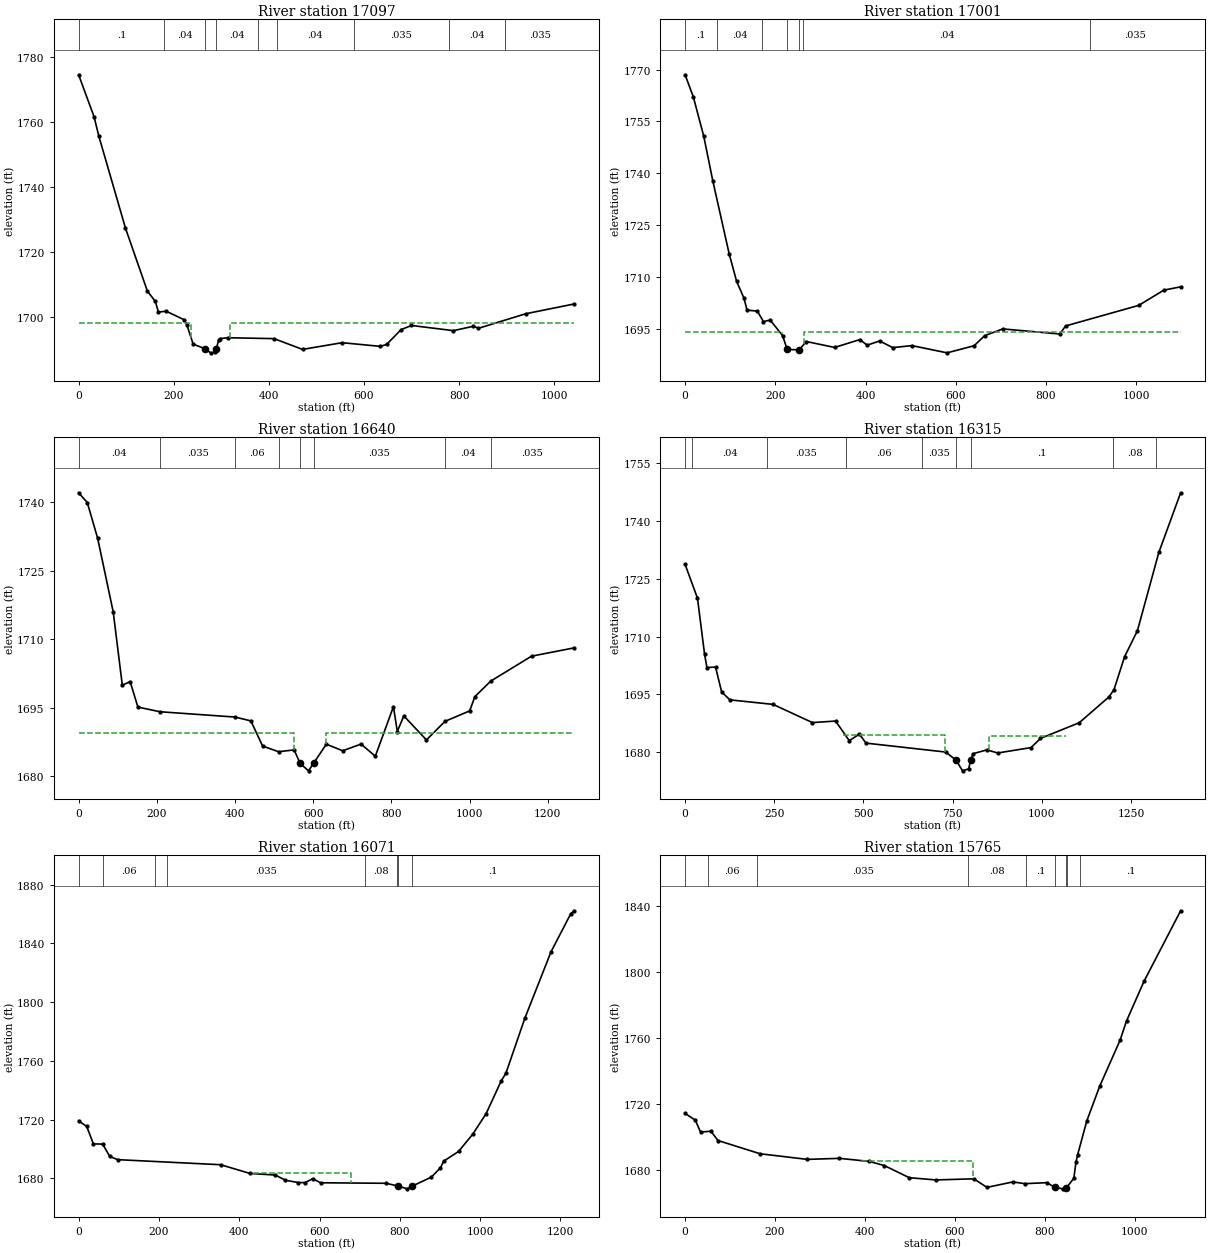
Type RM Length L Ch R = 1 ,17097   ,95.6,96.6,95.5
XS GIS Cut Line= 5
 2029154.1075903287315.1151621572029340.24346111287332.963807304
2029656.41946086287389.0595491942029940.04019326287444.017218877
2030093.37752867287253.149191511
#Sta/Elev= 30
       0 1774.67    32.5 1761.69    42.4 1755.78    98.5 1727.36   144.6 1707.92
   161.1 1704.81   167.7 1701.49   184.2 1701.74   220.8 1699.19   227.4 1697.61
   240.8 1691.59   266.51690.127   277.4 1688.91   287.4 1689.12   289.6 1690.18
   294.1 1692.76   297.4  1693.3   314.1 1693.57   410.7 1693.29   470.7 1689.97
   554.1 1692.04   634.3  1690.9   647.7 1691.52   677.8 1696.06   699.8 1697.35
     788 1695.75   830.1 1697.12   840.6 1696.48   940.1 1700.97  1041.8 1703.98
#Mann= 9 ,-1 , 0
       0      .1       0     180     .04       0   266.5    .045       0
   289.6     .04       0  376.99    .035       0  416.99     .04       0
   578.1    .035       0   778.1     .04       0     897    .035       0
#XS Ineff= 2 , 0
          236.67 1698.16     319         1698.09
Permanent Ineff=
       F       F
Bank Sta=266.5,289.6
XS Rating Curve= 0 ,0
Exp/Cntr(USF)=0,0
Exp/Cntr=0.5,0.3

Type RM Length L Ch R = 1 ,17001   ,364.6,360.5,351.2
XS GIS Cut Line= 5
2029161.75700965 287409.458000792029312.19559017287427.306645937
2029562.07662222287442.6054846342029950.52563689287515.318235592
2030145.63824695287285.724239682
#Sta/Elev= 30
       0 1768.49    18.3 1762.08    41.4 1750.69    61.3 1737.89    97.6 1716.78
   114.1 1708.81   130.6 1703.88   137.2 1700.47   160.3 1700.15   173.5 1697.16
   188.7 1697.57   216.2 1693.07   226.1 1689.11   252.61688.954   268.8 1691.38
   331.3 1689.67   387.1 1691.93   403.6 1690.33   431.1 1691.54   460.3 1689.62
   502.8  1690.2   580.5 1688.11   640.6 1690.16   663.9 1693.07     704 1695.03
   830.5 1693.56   843.3 1695.88  1005.4 1701.83  1061.1 1706.24  1098.3 1707.19
#Mann= 7 ,-1 , 0
       0      .1       0      70     .04       0  171.49     .06       0
   226.1    .045       0   252.6     .06       0  261.49     .04       0
  897.04    .035       0
#XS Ineff= 2 , 0
             214    1694     264            1694
Permanent Ineff=
       F       F
Bank Sta=226.1,252.6
XS Rating Curve= 0 ,0
Exp/Cntr(USF)=0,0
Exp/Cntr=0.5,0.3

Type RM Length L Ch R = 1 ,16640   ,310.9,325,339.3
XS GIS Cut Line= 5
 2029128.6095258287572.6456135612029615.62255766287649.139807048
2029796.65881558287582.8448393592029992.46741143287609.687228303
2030206.37046157287290.929741812
#Sta/Elev= 30
       0    1742    22.1 1739.87    48.6 1732.06    88.5 1715.92   111.7 1699.92
   131.7 1700.72   151.6 1695.14     208 1694.12   400.1 1692.96   440.5 1692.12
   470.4 1686.63   511.2 1685.38   551.2 1685.78   566.5 1682.81     588  1681.2
  600.84 1682.85   633.4 1687.03   675.4 1685.59   722.3 1687.05   758.7  1684.4
   805.1 1695.23     815  1689.8   831.6 1693.21   889.5 1687.96   936.9 1692.02
  1000.1 1694.31  1013.2  1697.4  1053.9 1700.82  1158.2 1706.27  1267.3 1708.09
#Mann= 8 ,-1 , 0
       0     .04       0     208    .035       0   400.1     .06       0
   511.2    .035       0   566.5    .045       0  600.84    .035       0
   936.9     .04       0  1053.9    .035       0
#XS Ineff= 2 , 0
           549.6 1689.37  633.88         1689.37
Permanent Ineff=
       F       T
Bank Sta=566.5,600.84
XS Rating Curve= 0 ,0
Exp/Cntr(USF)=0,0
Exp/Cntr=0.3,0.1

Type RM Length L Ch R = 1 ,16315   ,237.7,244.1,251
XS GIS Cut Line= 4
 2029113.3106871287610.8927103042029707.41558985 287860.77374236
2030021.04178314287947.4671616442030365.26565383288187.148967902
#Sta/Elev= 30
       0 1728.73    34.7 1719.96    54.5 1705.49    61.1 1701.95    85.4 1702.06
   102.4 1695.61   125.7 1693.55   246.5 1692.38     357 1687.65   421.9 1688.05
   460.2 1682.96   488.7 1684.65   507.1 1682.32   730.4    1680   759.6 1677.91
     778 1675.12   795.1 1675.64  800.55 1677.91   807.6 1679.58   846.1 1680.56
   876.7 1679.76   969.9 1681.16   996.4 1683.54  1104.9 1687.61  1188.3 1694.31
  1202.5 1696.21  1232.3 1704.78  1268.3 1711.55  1328.2 1731.841389.353 1747.33
#Mann= 9 ,-1 , 0
       0      .1       0      20     .04       0     230    .035       0
     450     .06       0  664.52    .035       0   759.6    .045       0
  800.55      .1       0  1199.9     .08       0  1319.9      .1       0
#XS Ineff= 2 ,-1
  442.88  729.091684.389  850.98 1067.721684.212
Permanent Ineff=
       T       T
Bank Sta=759.6,800.55
XS Rating Curve= 0 ,0
Exp/Cntr(USF)=0,0
Exp/Cntr=0.3,0.1

Type RM Length L Ch R = 1 ,16071   ,298,306.4,312.3
XS GIS Cut Line= 4
2029085.26281616287631.2911619012029498.33146099287967.865613241
2029837.45571877288182.0493550032030018.49197669 288421.73116126
#Sta/Elev= 30
       0 1719.22    20.2  1715.4    36.7 1703.57      60 1703.39    77.3 1695.04
    97.3 1692.82   353.8 1689.37   426.8 1683.42   490.3 1682.34   514.7 1678.82
   546.9 1677.27   564.3 1677.19   583.1 1679.87   602.5 1677.09   765.5 1676.74
     795 1674.89   818.8 1672.96  831.02 1674.82   878.7 1680.96   901.3 1687.31
   909.4 1691.82   946.3 1698.39   982.2 1710.35    1015 1724.15  1052.4 1746.31
  1064.2 1751.58  1111.3 1788.97  1176.6 1834.26  1225.8 1860.191234.298 1862.19
#Mann= 8 ,-1 , 0
       0      .1       0      60     .06       0     190     .04       0
     220    .035       0  712.83     .08       0  792.83      .1       0
     795    .045       0  831.02      .1       0
#XS Ineff= 1 ,-1
  435.86  677.931683.469
Permanent Ineff=
       T
Bank Sta=795,831.02
XS Rating Curve= 0 ,0
Exp/Cntr(USF)=0,0
Exp/Cntr=0.3,0.1

Type RM Length L Ch R = 1 ,15765   ,243.5,252,261.1
XS GIS Cut Line= 4
2029054.66513876287631.2911619012029350.44268691288105.555161516
2029577.37546092288406.4323225632029697.21636405288521.173612792
#Sta/Elev= 30
       0 1714.04    22.7 1709.93    34.3 1702.73    57.5 1703.22      73 1697.59
   166.8 1689.55   271.6 1686.14   343.1 1686.77   409.4 1684.92   443.1 1682.37
   498.3 1675.04   557.4 1673.67   641.8 1674.35   671.2 1669.16   728.8 1672.47
   755.2  1671.4   804.3 1672.02   822.1 1669.13   839.7 1668.27   847.9 1668.93
   847.9 1668.94   864.2 1674.66     869  1684.3   872.6 1688.85   893.1 1709.52
   921.9 1730.63     967 1758.38   981.4 1770.13  1020.4 1794.251101.714 1836.97
#Mann= 9 ,-1 , 0
       0      .1       0      50     .06       0     160    .035       0
  628.94     .08       0  758.94      .1       0   822.1    .045       0
   847.9      .1       0  848.94     .08       0  878.94      .1       0
#XS Ineff= 1 ,-1
  392.05  639.531684.991
Permanent Ineff=
       T
Bank Sta=822.1,847.9
XS Rating Curve= 0 ,0
Exp/Cntr(USF)=0,0
Exp/Cntr=0.3,0.1

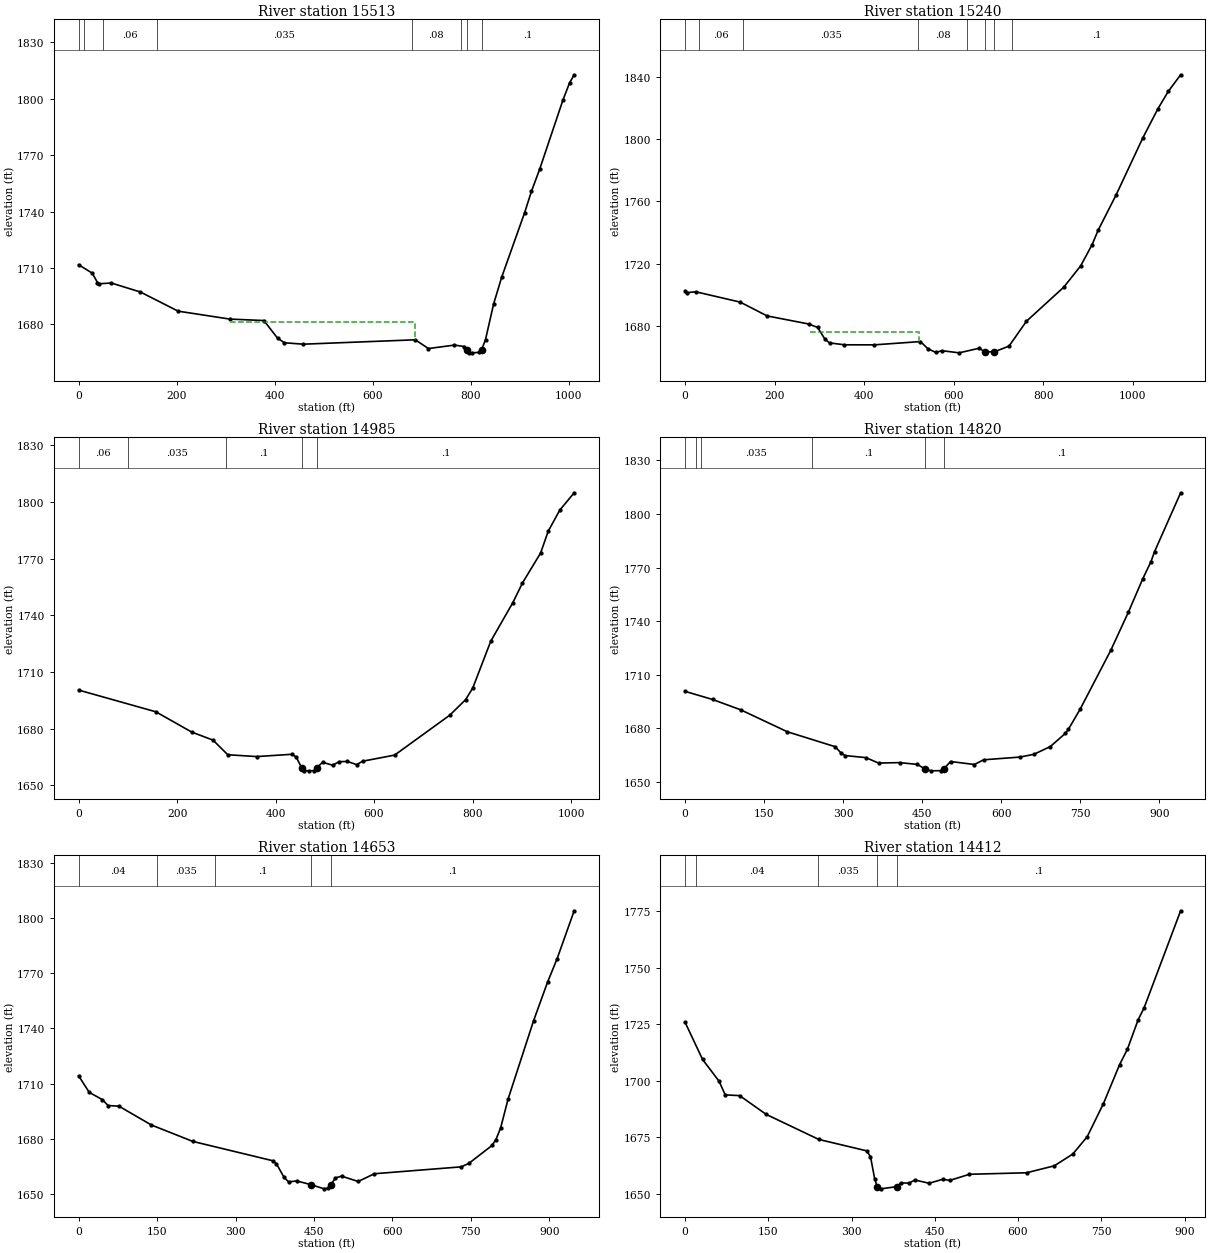
Type RM Length L Ch R = 1 ,15513   ,259,272.5,279.9
XS GIS Cut Line= 4
2029026.61726782287621.0919361032029248.45042893288220.296451746
2029291.79713857288472.7272902512029319.84500952288584.918774031
#Sta/Elev= 30
       0 1711.72    27.9 1707.21    38.4 1702.28    41.9 1701.61    66.4 1702.02
   125.9 1697.24   202.9 1687.06   308.2 1682.85   377.8 1682.07   405.8  1672.7
   419.8 1670.26   458.3 1669.51   686.7 1671.84   713.4 1667.19   766.6 1669.03
   786.6 1668.25  792.361666.656   796.6 1664.97   803.2 1664.91   816.5 1665.16
  822.141666.657   829.9 1671.99   846.5 1690.97   863.1 1705.27   909.5 1739.25
   923.5 1750.66   940.4 1762.52   987.5 1798.99  1001.4  1808.41010.719 1812.65
#Mann= 8 ,-1 , 0
       0     .04       0      10      .1       0      50     .06       0
     160    .035       0  678.95     .08       0  778.95      .1       0
  792.36    .045       0  822.14      .1       0
#XS Ineff= 1 ,-1
  309.41  686.461681.318
Permanent Ineff=
       T
Bank Sta=792.36,822.14
XS Rating Curve= 0 ,0
Exp/Cntr(USF)=0,0
Exp/Cntr=0.3,0.1

Type RM Length L Ch R = 1 ,15240   ,272.5,255.4,233.2
XS GIS Cut Line= 4
2029001.11920332287646.5900005982029077.61339681288151.451677608
2028985.82036463288424.2809677092028932.27442919288727.707935205
#Sta/Elev= 30
       0 1702.42       4 1701.29    23.9 1701.83   123.1 1695.18   183.2  1686.3
   276.1 1681.11     296 1678.88   312.6  1671.2   322.6 1668.96   355.8 1667.73
   422.1 1667.69   525.6 1669.81   542.1 1665.21   560.2 1662.81   573.2 1663.96
     612 1662.56   657.2 1665.55     669 1663.21   690.7 1663.23   723.4  1666.9
   762.2 1682.86   845.7 1704.82   883.5 1718.55     909 1732.21   922.3 1741.35
   962.8 1764.32  1022.2 1800.84  1055.6 1819.41  1078.9 1830.671106.596  1841.4
#Mann= 8 ,-1 , 0
       0     .04       0      30     .06       0     130    .035       0
  520.62     .08       0  630.62      .1       0     669    .045       0
   690.7    .035       0  730.62      .1       0
#XS Ineff= 1 ,-1
     279  522.331676.217
Permanent Ineff=
       T
Bank Sta=669,690.7
XS Rating Curve= 0 ,0
Exp/Cntr(USF)=0,0
Exp/Cntr=0.3,0.1

Type RM Length L Ch R = 1 ,14985   ,163.4,165.2,167
XS GIS Cut Line= 4
2028975.62113883287669.5382586442028919.52539694 288029.06096803
2028820.08294541288388.5836774162028771.63662286288653.763548169
#Sta/Elev= 30
       0 1700.51   156.8 1689.02   229.6 1678.29     273 1674.01   302.9 1666.28
   361.8 1665.31   433.9 1666.53   441.9 1665.06  452.871659.419   457.9 1657.91
   468.6 1657.76   478.4  1657.9  483.841659.422   495.4 1662.28   515.8 1660.76
   529.4 1662.62   545.9 1662.72   564.6 1661.05   577.1 1662.87   641.8 1666.09
   753.8 1687.22   785.9 1695.43   800.5  1701.6   837.1 1726.42   881.8 1746.75
   901.5 1757.23   938.2 1773.02   953.9 1784.69   977.2 1795.761006.464 1804.95
#Mann= 5 ,-1 , 0
       0     .06       0     100    .035       0     300      .1       0
  452.87    .045       0  483.84      .1       0
Bank Sta=452.87,483.84
XS Rating Curve= 0 ,0
Exp/Cntr(USF)=0,0
Exp/Cntr=0.3,0.1

Type RM Length L Ch R = 1 ,14820   ,164.9,166.5,169.4
XS GIS Cut Line= 4
2028942.47365498287654.2394199472028792.03507446287924.518903598
2028684.94320358288212.6470323972028565.10230045288513.524193444
#Sta/Elev= 30
       0 1700.75    52.1 1696.21   105.4 1690.44   194.2 1678.13   284.9 1669.79
   296.2 1666.19   303.7 1664.84   343.2 1663.68   367.1 1660.64     407 1660.89
   440.6  1659.9  456.011657.255   467.2 1656.29   486.1 1656.41  490.711657.256
   503.9 1661.51   549.1 1659.83   566.6 1662.47   635.6 1663.99   662.2 1665.56
   693.3 1669.88   721.5 1677.18   727.4 1679.46   750.1 1690.93   808.2 1723.84
   841.6  1745.2   868.8  1763.8     884 1773.14     891 1778.86940.5784 1811.84
#Mann= 6 ,-1 , 0
       0     .04       0      20     .06       0      30    .035       0
     240      .1       0  456.01    .045       0  490.71      .1       0
Bank Sta=456.01,490.71
XS Rating Curve= 0 ,0
Exp/Cntr(USF)=0,0
Exp/Cntr=0.3,0.1

Type RM Length L Ch R = 1 ,14653   ,239.2,240.6,239.5
XS GIS Cut Line= 4
 2028830.2821712287536.9483232682028692.59262293287842.925097213
2028526.85520371288128.5034195622028412.11391348288386.033870966
#Sta/Elev= 30
       0 1714.17    20.3 1705.18    45.5 1701.21    56.3 1698.01    77.1 1697.66
     139 1687.42   218.2 1678.47   371.1 1667.94   378.3 1666.28   392.7 1658.93
   401.4 1656.43   416.9 1656.91  443.611654.983   469.5 1652.62   477.3 1653.04
  482.841654.981   491.1  1658.6   503.1 1659.52   534.6 1656.63   565.6 1660.85
   731.6  1664.6     746 1666.45   790.6 1676.25   798.1  1679.5     807 1685.78
   821.3 1701.57   870.1 1744.27   896.8 1765.27   914.9  1777.9947.6526 1804.12
#Mann= 5 ,-1 , 0
       0     .04       0     150    .035       0     260      .1       0
  443.61    .045       0  482.84      .1       0
Bank Sta=443.61,482.84
XS Rating Curve= 0 ,0
Exp/Cntr(USF)=0,0
Exp/Cntr=0.3,0.1

Type RM Length L Ch R = 1 ,14412   ,180.8,180.2,179.8
XS GIS Cut Line= 4
2028644.14630039287455.3545168822028519.20578436 287692.48651669
2028358.56797804 288029.060968032028243.82668781 288253.44393559
#Sta/Elev= 30
       0 1725.89    31.5 1709.46    61.2 1699.84    72.3 1693.79    98.3 1693.46
   146.2 1685.15   240.9 1674.08     327 1669.04   334.1 1666.47   341.6 1656.68
  346.091653.187   352.5 1652.22  381.511653.185   388.8 1654.85   403.4 1654.76
   414.3 1656.13   439.7 1654.69   464.5 1656.46   476.8 1655.94   512.4 1658.66
   615.4 1659.33   665.4 1662.41   698.6 1667.61   724.6 1675.27   753.9 1689.95
   783.1 1707.23     797 1713.95   816.5 1727.08     827 1732.21 892.995 1775.24
#Mann= 5 ,-1 , 0
       0      .1       0      20     .04       0     240    .035       0
  346.09    .045       0  381.51      .1       0
Bank Sta=346.09,381.51
XS Rating Curve= 0 ,0
Exp/Cntr(USF)=0,0
Exp/Cntr=0.3,0.1

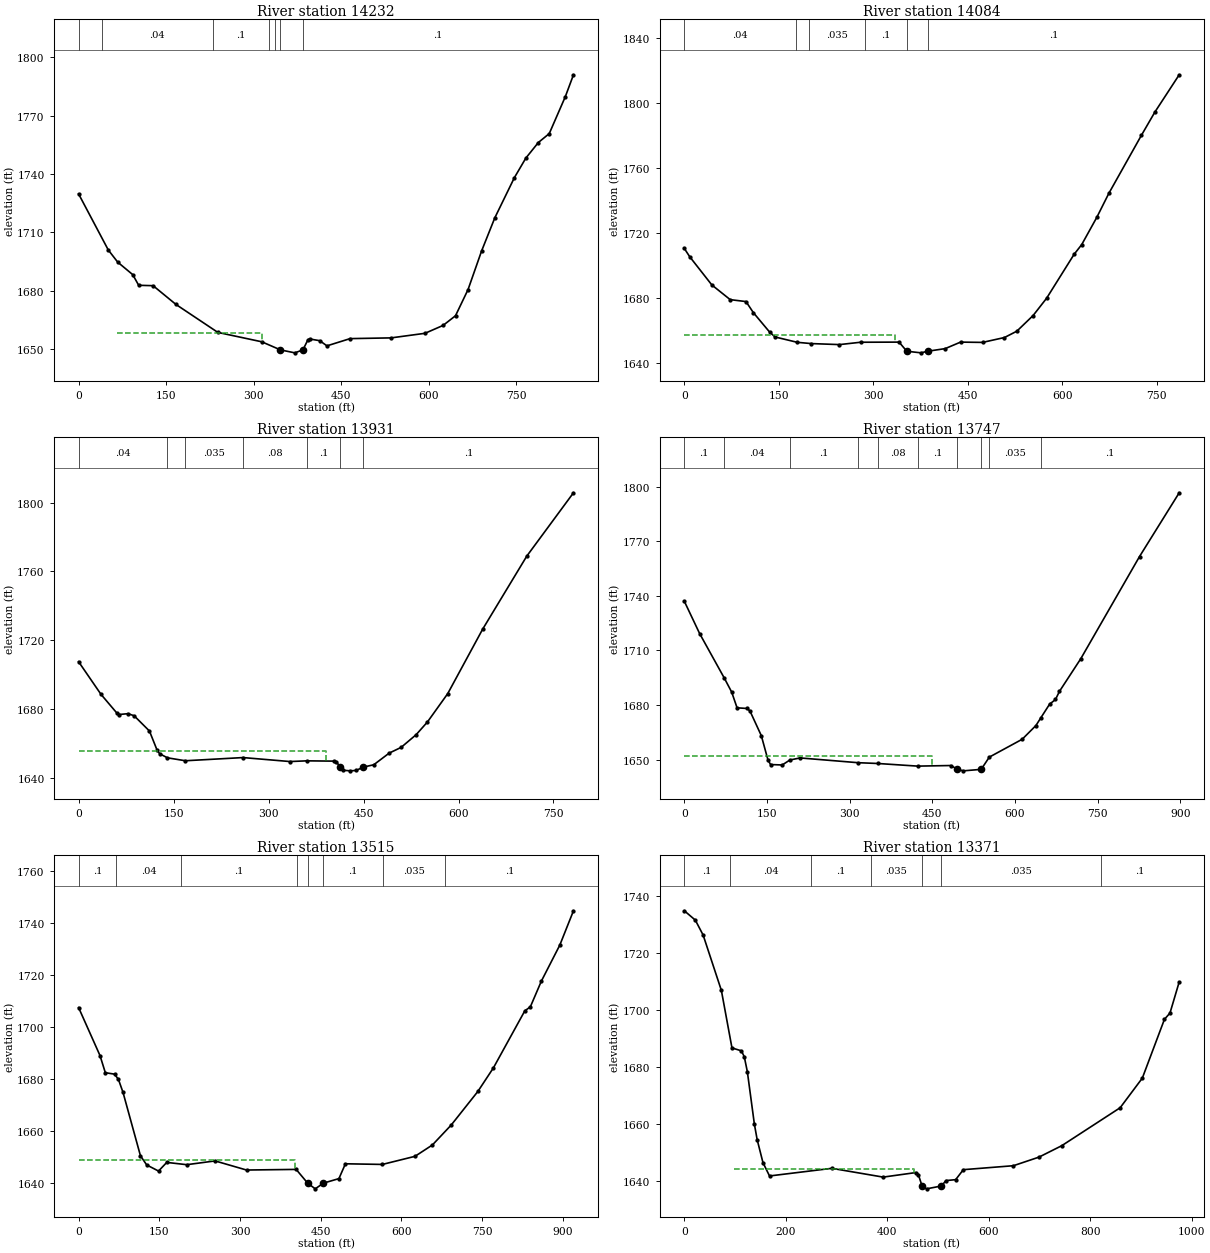
Type RM Length L Ch R = 1 ,14232   ,150.5,148.1,146.2
XS GIS Cut Line= 4
2028450.36101022  287353.36225892028356.01817159287613.442516754
2028251.47610716287842.9250972132028098.48772018288123.403806663
#Sta/Elev= 30
       0 1729.75    50.9 1700.92    67.1 1694.66    92.8 1688.25     103 1682.77
   127.7 1682.57     167  1672.9   238.7 1658.55   313.9 1653.73  346.061649.554
   370.6 1648.04  384.541649.555   393.2 1654.81   396.8 1655.13   413.4 1654.29
   425.7 1651.63   465.4 1655.35   535.7 1655.73   593.8 1658.08   624.8 1662.14
   646.1 1667.11   667.6 1680.57   690.9 1700.48   713.5 1717.47     747  1738.1
   766.7 1748.18   788.1 1756.18   806.8 1760.76   834.4 1779.79848.3258 1791.01
#Mann= 7 ,-1 , 0
       0      .1       0      40     .04       0     230      .1       0
  326.66     .08       0  336.66      .1       0  346.06    .045       0
  384.54      .1       0
#XS Ineff= 1 ,-1
   65.46  313.751658.164
Permanent Ineff=
       T
Bank Sta=346.06,384.54
XS Rating Curve= 0 ,0
Exp/Cntr(USF)=0,0
Exp/Cntr=0.3,0.1

Type RM Length L Ch R = 1 ,14084   ,154.2,152.8,154.9
XS GIS Cut Line= 5
2028338.16952644287325.3143879552028259.12552651287437.505871735
2028200.47997817287587.9444522592028126.53559113287794.478774672
2027973.54720416288013.762129333
#Sta/Elev= 30
       0 1710.75     8.6 1705.63    43.7 1688.28    72.8 1679.26    97.9 1678.07
   109.6 1671.24   135.5 1659.25   144.1 1656.28   179.3    1653   201.3 1652.23
   246.2  1651.6   279.8 1653.05   340.8 1653.13  353.111647.506   375.7 1646.53
  386.021647.506     414 1649.12   438.4 1653.13   473.3 1652.95   508.1 1655.95
   527.7 1659.84   553.6  1669.5     575 1680.12   618.6 1707.13   630.7 1713.11
   654.7 1729.91   673.7  1744.6   725.6 1780.45   746.8 1794.64785.4552  1817.6
#Mann= 6 ,-1 , 0
       0     .04       0  177.24     .08       0  197.24    .035       0
  287.24      .1       0  353.11    .045       0  386.02      .1       0
#XS Ineff= 2 , 0
          334.63 1657.39
Permanent Ineff=
       T       F
Bank Sta=353.11,386.02
XS Rating Curve= 0 ,0
Exp/Cntr(USF)=0,0
Exp/Cntr=0.3,0.1

Type RM Length L Ch R = 1 ,13931   ,181.5,184.7,188
XS GIS Cut Line= 4
2028231.07765556287264.1190331662028080.63907504287475.752968478
 2027986.2962364287740.9328392312027851.15649458287939.817742296
#Sta/Elev= 30
       0 1707.44    35.4 1688.44    60.2 1677.67    63.6 1676.71    78.1 1677.21
    87.7 1675.99   111.9 1667.11   123.7 1656.21     128 1653.89   140.4 1651.51
   168.7 1649.81   259.7 1651.66   333.8 1649.35   360.4 1649.76   403.4 1649.59
   406.9 1649.22  413.341646.135   417.4 1644.28   429.1 1643.94   438.3 1644.17
  449.761646.133   466.1 1647.46   490.5 1654.25   509.4 1657.59   533.1 1664.98
   550.9 1672.36     583 1688.88   638.1 1726.35   707.9 1768.93781.5707 1805.75
#Mann= 7 ,-1 , 0
       0     .04       0   140.4     .08       0   168.7    .035       0
   259.7     .08       0   360.4      .1       0  413.34    .045       0
  449.76      .1       0
#XS Ineff= 2 , 0
             390 1655.25
Permanent Ineff=
       T       F
Bank Sta=413.34,449.76
XS Rating Curve= 0 ,0
Exp/Cntr(USF)=0,0
Exp/Cntr=0.3,0.1

Type RM Length L Ch R = 1 ,13747   ,225.9,231.6,237.2
XS GIS Cut Line= 4
2028146.93404273287126.4294848912027968.44759126287358.461871799
2027815.45920428287644.040194148 2027708.3673334287904.120452002
#Sta/Elev= 30
       0 1737.01    27.8 1719.27    72.3 1694.98    85.9 1687.19    95.7 1678.54
   113.8 1678.18   119.1 1676.79   139.7 1663.26   151.8 1649.87   156.5  1647.4
   177.6 1647.17   191.6 1649.91   210.1 1651.03   315.2 1648.42   351.3 1647.98
   423.4 1646.54   483.7 1646.87  495.591644.762   506.3 1643.95  538.65 1644.76
   553.4 1651.48     613 1661.27     638 1668.82   647.1 1673.15   662.8 1680.54
   673.5 1683.11   680.6 1687.53   719.6  1705.6     826 1761.58897.9813 1796.56
#Mann= 10 ,-1 , 0
       0      .1       0    72.3     .04       0   191.6      .1       0
   315.2    .035       0   351.3     .08       0   423.4      .1       0
  495.59    .045       0  538.65      .1       0   553.4    .035       0
   647.1      .1       0
#XS Ineff= 2 , 0
             450  1652.2
Permanent Ineff=
       F       F
Bank Sta=495.59,538.65
XS Rating Curve= 0 ,0
Exp/Cntr(USF)=0,0
Exp/Cntr=0.3,0.1

Type RM Length L Ch R = 1 ,13515   ,146.5,144.4,141.6
XS GIS Cut Line= 4
2027999.04526865287029.5368398082027789.96113979287279.417871863
2027593.62604317287552.2471619652027519.68165614287799.578387571
#Sta/Elev= 30
       0 1707.41    39.8 1688.96    49.7 1682.38    66.8 1681.83      74 1679.83
    82.5 1674.88     115 1650.46   126.6 1646.94   148.6 1644.58   163.9 1647.91
   201.1 1647.03   253.7 1648.48   312.2 1644.98   404.5 1645.22  425.891639.939
     440 1637.75  455.051639.937     484 1641.68   496.1 1647.38   564.8 1647.13
   625.4 1650.24   657.8 1654.61   692.7 1662.25   742.3 1675.17   771.3 1684.26
   829.6 1706.15   839.9 1707.69   860.5 1717.62   894.7 1731.42920.0951 1744.61
#Mann= 8 ,-1 , 0
       0      .1       0      70     .04       0     190      .1       0
  405.82     .12       0  425.89    .045       0  455.05      .1       0
  565.82    .035       0  681.95      .1       0
#XS Ineff= 2 , 0
           401.8 1648.71
Permanent Ineff=
       T       F
Bank Sta=425.89,455.05
XS Rating Curve= 0 ,0
Exp/Cntr(USF)=0,0
Exp/Cntr=0.3,0.1

Type RM Length L Ch R = 1 ,13371   ,241,240.2,240.1
XS GIS Cut Line= 4
2027904.70243002286889.2974850832027705.81752695287123.879678441
2027545.17972063287394.1591620932027392.19133366287712.884968286
#Sta/Elev= 30
       0 1734.77    21.7 1731.48    37.1 1726.23      73 1706.82    93.9 1686.62
   112.5  1685.6   118.2 1683.51   124.2  1678.3   138.1 1659.84   143.6 1654.39
     155 1646.36   167.9 1641.67   290.7 1644.35   391.9 1641.27   456.7 1642.87
   461.3 1642.16   468.61638.157   477.5 1637.15  506.851638.156   515.7 1640.05
   534.8 1640.37     550 1643.88   648.7 1645.27     699 1648.28     744  1652.3
   859.1 1665.62   902.8 1676.02   946.4 1696.67   957.3 1698.86975.4996 1709.79
#Mann= 7 ,-1 , 0
       0      .1       0      90     .04       0     250      .1       0
  367.55    .035       0   468.6    .045       0  506.85    .035       0
  821.96      .1       0
#XS Ineff= 1 ,-1
   98.35   453.71644.264
Permanent Ineff=
       T
Bank Sta=468.6,506.85
XS Rating Curve= 0 ,0
Exp/Cntr(USF)=0,0
Exp/Cntr=0.3,0.1

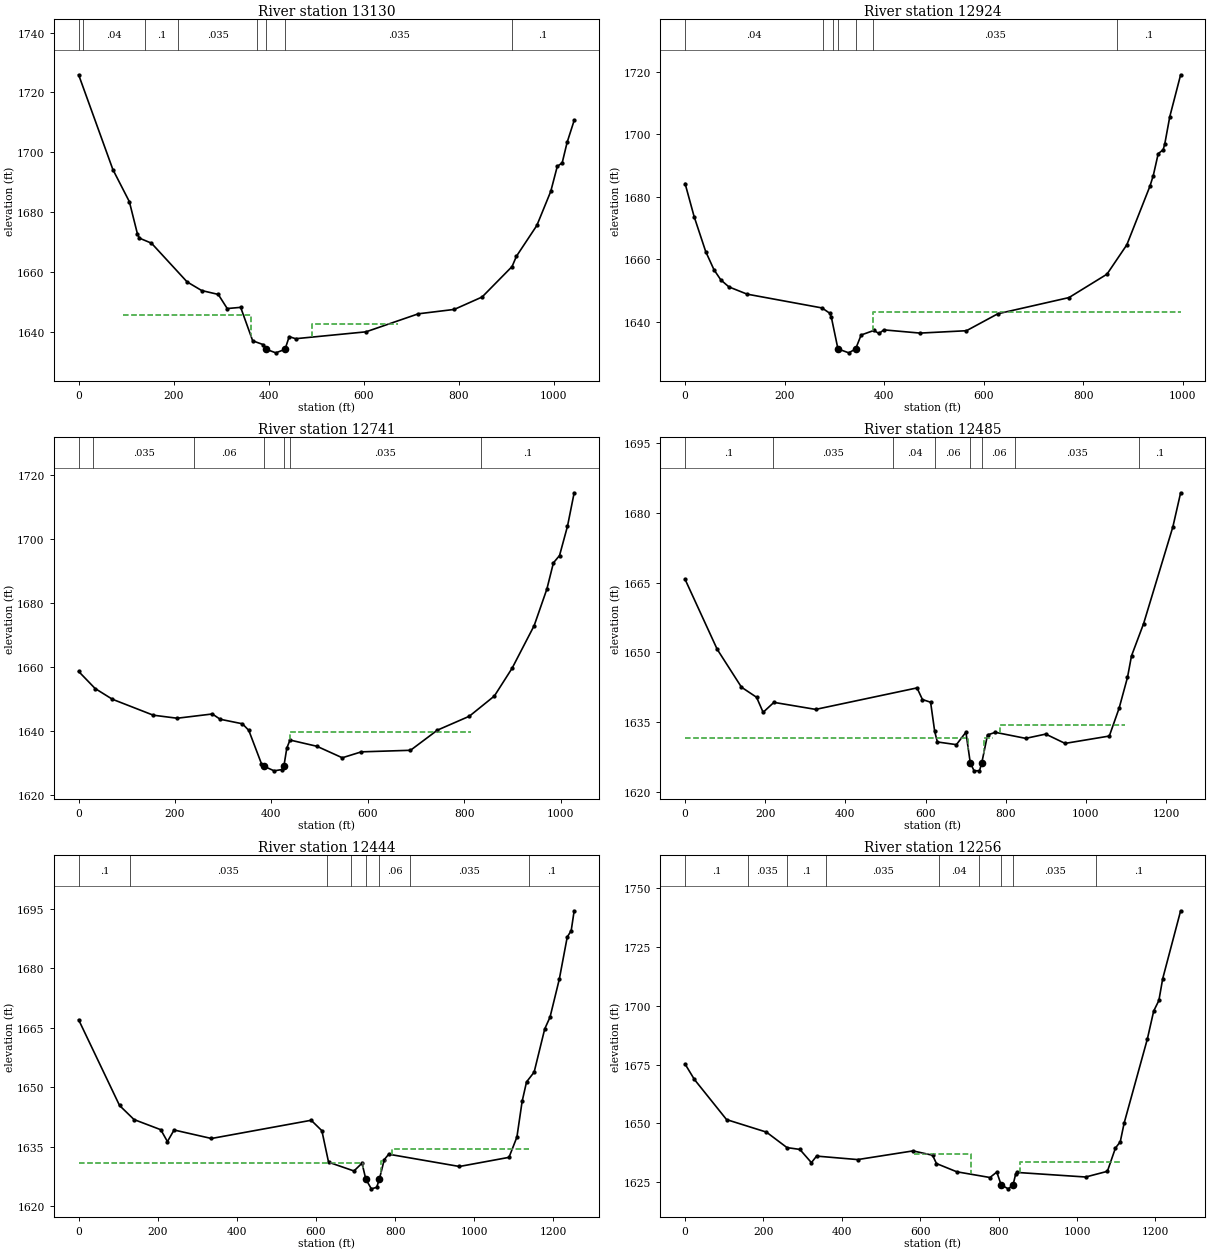
Type RM Length L Ch R = 1 ,13130   ,217.3,206.6,198.1
XS GIS Cut Line= 4
2027682.86926891286777.1060013032027514.58204324286983.640323716
2027361.59365627287248.8201944692027218.80449509287697.586129589
#Sta/Elev= 30
       0 1725.92    72.1 1694.21   106.8 1683.47   123.7 1672.75     128 1671.26
   153.4 1669.57   228.4 1656.62   259.2 1653.72     294 1652.43   312.9  1647.7
   341.2  1648.1   366.5 1636.91   388.2 1635.66  395.261634.052   415.2 1632.88
  434.631634.052   443.4 1638.31   456.9 1637.61   605.1 1639.91   715.3 1645.94
     791 1647.41   849.6 1651.56   912.7 1661.75   921.9 1665.19   964.9  1675.5
   994.2 1686.91  1007.9 1695.26  1018.3 1696.47  1028.6 1703.281043.497 1710.65
#Mann= 8 ,-1 , 0
       0      .1       0      10     .04       0     140      .1       0
     210    .035       0  376.42     .06       0  395.26    .045       0
  434.63    .035       0  912.56      .1       0
#XS Ineff= 2 ,-1
    92.4  363.631645.485  491.69  672.21 1642.59
Permanent Ineff=
       T       F
Bank Sta=395.26,434.63
XS Rating Curve= 0 ,0
Exp/Cntr(USF)=0,0
Exp/Cntr=0.3,0.1

Type RM Length L Ch R = 1 ,12924   ,184.3,183.3,183.7
XS GIS Cut Line= 4
2027302.94810793286710.8110336152027262.15120473286945.393226973
2027241.75275314287144.278130038 2027152.5095274287695.036323139
#Sta/Elev= 30
       0 1684.27    18.1 1673.71    41.4 1662.48    58.1 1656.63    71.9 1653.37
    88.1 1651.14   124.7 1648.82   275.2  1644.4   290.7 1642.71     294 1641.39
  307.211631.268     329 1630.01  342.771631.269   353.8 1635.73   379.5 1637.19
   389.6 1636.21   399.5 1637.37   472.3 1636.34   565.5  1637.1   628.5 1642.53
   771.5 1647.72   847.9 1655.22   887.8 1664.63   934.3 1683.44     941 1686.85
   950.9 1693.85   960.9 1695.12   964.2 1697.07   974.2 1705.75995.9733 1719.14
#Mann= 7 ,-1 , 0
       0     .04       0   278.1     .06       0   298.1     .05       0
  307.21    .045       0  342.77     .05       0   378.1    .035       0
  868.03      .1       0
#XS Ineff= 2 , 0
                          376.79         1643.14
Permanent Ineff=
       F       F
Bank Sta=307.21,342.77
XS Rating Curve= 0 ,0
Exp/Cntr(USF)=0,0
Exp/Cntr=0.3,0.1

Type RM Length L Ch R = 1 ,12741   ,263.9,256.1,249.1
XS GIS Cut Line= 4
 2027178.0075919286657.2650981742027081.11494682286896.946904432
2027055.61688232287251.3700009182027025.01920493287664.438645745
#Sta/Elev= 30
       0  1658.6    34.2 1653.26    69.9 1649.91   154.9 1644.91   204.4 1643.96
   277.3 1645.29   293.7 1643.64   339.8 1642.22     353 1640.16   379.3 1629.72
  385.061628.894   405.6  1627.5     422 1627.91  425.751628.893   431.9 1634.61
   438.5 1637.14   494.4 1635.18     547 1631.59   586.5 1633.44   688.5 1633.93
   744.4 1640.24   810.5 1644.58   862.5 1650.91   899.3 1659.61   945.1 1672.95
   971.4 1684.36     985 1692.57   997.7 1694.87  1014.2 1704.041028.065  1714.5
#Mann= 7 ,-1 , 0
       0     .06       0      30    .035       0     240     .06       0
  385.06    .045       0  425.75     .06       0  438.53    .035       0
  833.86      .1       0
#XS Ineff= 1 ,-1
  439.05  813.27  1639.5
Permanent Ineff=
       T
Bank Sta=385.06,425.75
XS Rating Curve= 0 ,0
Exp/Cntr(USF)=0,0
Exp/Cntr=0.5,0.3

Type RM Length L Ch R = 1 ,12485   ,39.9,40.2,40.9
XS GIS Cut Line= 4
2026648.83907117  286375.09240162026779.22027853286934.456492361
2026904.99225682287416.8477508432026939.04385168287576.878187287
#Sta/Elev= 30
       0 1665.67    80.1 1650.64   140.7 1642.49   178.3 1640.33   194.7 1637.09
   221.6 1639.23   325.8 1637.72   578.7 1642.34   592.2 1639.84   612.6 1639.26
   622.8 1632.98   629.5 1630.72     677 1630.14   700.7 1632.82   711.6 1626.22
   721.1 1624.51   734.6 1624.54  740.16 1626.18   754.6 1632.22     774 1632.79
   849.9 1631.49   899.8 1632.41   948.1 1630.41  1058.5 1631.99    1083 1637.98
  1103.9 1644.61  1113.9 1649.23  1144.1 1656.16  1217.1 1676.96  1236.5 1684.29
#Mann= 8 ,-1 , 0
       0      .1       0     220    .035       0     520     .04       0
  624.36     .06       0   711.6    .045       0  740.16     .06       0
  824.36    .035       0 1132.88      .1       0
#XS Ineff= 3 ,-1
       0  706.851631.632  745.01  769.051631.633  785.01 1097.75 1634.36
Permanent Ineff=
       F       F       F
Bank Sta=711.6,740.16
XS Rating Curve= 0 ,0
Exp/Cntr(USF)=0,0
Exp/Cntr=0.5,0.3

Type RM Length L Ch R = 1 ,12444   ,187.7,188.7,190.5
XS GIS Cut Line= 4
2026612.88956423286368.5819849432026734.64286851286912.167787348
2026858.82279643287418.4398012012026893.03506171287589.027274035
#Sta/Elev= 30
       0 1666.99   103.4  1645.4     140 1641.86   207.6  1639.3   224.4 1636.31
   241.2 1639.23   335.6 1637.09   587.7 1641.68   614.7 1639.05   631.6 1631.12
   695.8 1628.91   716.1 1630.87  725.79 1626.84   739.7 1624.41   753.2 1624.78
     760 1626.85   772.4 1631.77   783.6 1633.13   962.3 1630.04  1087.6 1632.34
  1107.6 1637.45  1120.8 1646.45  1131.9 1651.33  1151.1  1653.8  1177.9 1664.69
  1191.3 1667.66  1214.7  1677.2  1234.8 1687.84  1244.8 1689.44  1252.3 1694.44
#Mann= 8 ,-1 , 0
       0      .1       0     130    .035       0  627.05     .04       0
  687.05     .06       0  725.79    .045       0     760     .06       0
  837.05    .035       0 1138.33      .1       0
#XS Ineff= 3 ,-1
   -3.65  718.721631.021  763.79   775.9 1631.31   791.3 1137.63 1634.51
Permanent Ineff=
       F       F       F
Bank Sta=725.79,760
XS Rating Curve= 0 ,0
Exp/Cntr(USF)=0,0
Exp/Cntr=0.5,0.3

Type RM Length L Ch R = 1 ,12256   ,202.7,202.9,202.7
XS GIS Cut Line= 4
2026563.50423756286330.8898726322026558.40462466286919.895162477
2026639.99843104287386.5097427442026629.79920525287587.944452258
#Sta/Elev= 30
       0 1675.17    23.8 1668.63   105.8 1651.58   207.5 1646.26     260 1639.67
   292.8  1638.9   322.3 1633.27   335.5 1636.06   440.4 1634.58   581.6 1638.27
   631.4 1636.43   641.4 1632.89   693.2 1629.39   777.9 1626.96   795.3 1629.28
  806.441623.833   824.5 1622.14  836.791623.835   843.5 1628.42   847.9  1629.1
  1022.1 1627.17  1077.5 1629.59  1098.1 1639.51  1110.3 1642.11  1120.2 1650.05
  1179.4 1685.79  1195.7 1697.76  1208.9 1702.23  1218.7 1711.531264.415 1740.36
#Mann= 9 ,-1 , 0
       0      .1       0     160    .035       0     260      .1       0
     360    .035       0  649.03     .04       0  749.03    .035       0
  806.44    .045       0  836.79    .035       0 1049.03      .1       0
#XS Ineff= 2 ,-1
  584.96  730.251637.042  855.22 1114.041633.725
Permanent Ineff=
       T       T
Bank Sta=806.44,836.79
XS Rating Curve= 0 ,0
Exp/Cntr(USF)=0,0
Exp/Cntr=0.3,0.1