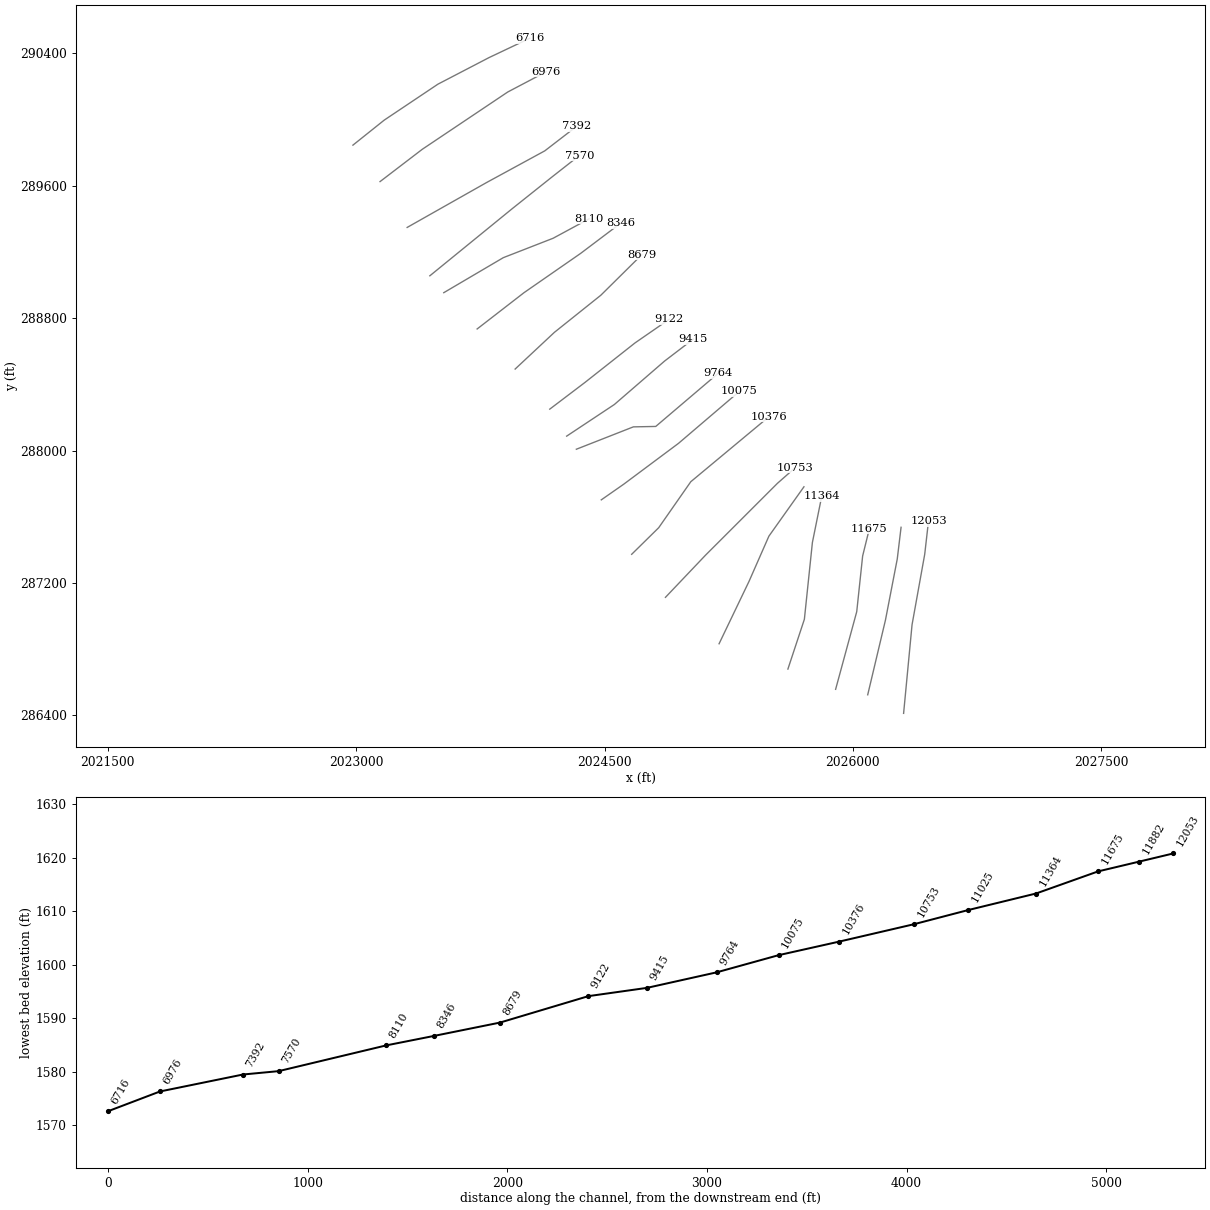
HEC-RAS study LICKCK1.prj: LICKCK1

--- LICKCK1.g01 (geometry) --- (continued)

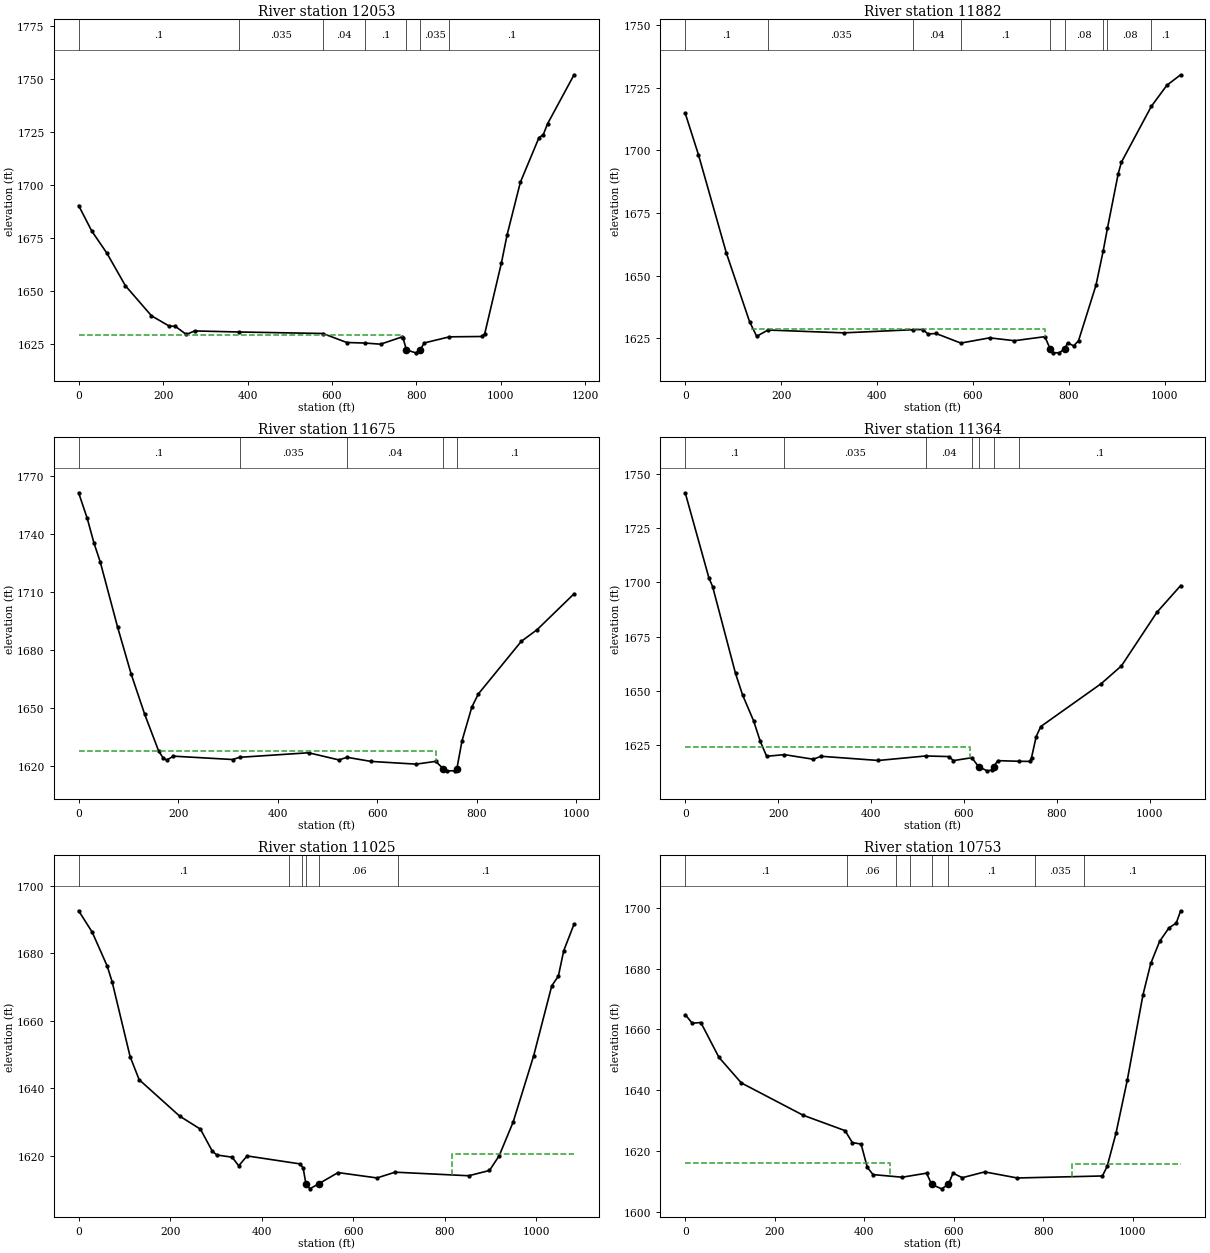
Type RM Length L Ch R = 1 ,12053   ,170.2,170.2,169.1
XS GIS Cut Line= 4
2026305.97378615286412.4836790182026356.96991514286947.943033422
2026433.46410863287373.7607104972026456.41236668287575.195420011
#Sta/Elev= 30
       0 1690.21    30.9 1678.26    67.1 1667.69   110.7 1652.44   172.5 1638.26
   214.7 1633.37   228.6 1633.34     255 1629.46   274.6 1631.12   380.2 1630.62
   578.4 1629.91   635.1 1625.67   678.1 1625.41   715.1 1624.88   765.1 1628.25
   768.5 1627.57  776.39 1622.18   798.4  1620.8  808.911622.182   818.4 1625.46
   878.1 1628.34   955.1  1628.5   961.8 1629.88  1001.3 1663.21  1014.7 1676.39
  1046.1 1701.16  1090.1 1722.15  1100.5 1723.65  1110.4 1728.671173.254  1751.8
#Mann= 7 ,-1 , 0
       0      .1       0   380.2    .035       0   578.4     .04       0
   678.1      .1       0  776.39    .045       0  808.91    .035       0
   878.1      .1       0
#XS Ineff= 2 , 0
           765.1  1629.2
Permanent Ineff=
       F       F
Bank Sta=776.39,808.91
XS Rating Curve= 0 ,0
Exp/Cntr(USF)=0,0
Exp/Cntr=0.3,0.1

Type RM Length L Ch R = 1 ,11882   ,204.5,207.3,208.3
XS GIS Cut Line= 4
2026089.24023794286524.6751627982026196.33210882286975.990904367
2026267.72668941287345.7128395522026290.67494746287536.948323268
#Sta/Elev= 30
       0 1714.83    27.6 1698.28    85.9 1659.02   134.1 1631.76     149 1625.87
   172.6 1628.38   330.4 1627.25   475.9 1628.51     496 1628.58     506 1626.78
   522.8    1627   574.7 1623.17   634.7 1625.26   686.4 1624.12   749.9 1625.73
  760.611621.003   766.6 1619.35     780 1619.28  791.731621.001   797.2 1623.29
   810.1 1622.04   820.1 1624.12   856.5 1646.25   871.6    1660   880.4 1668.99
   902.9 1690.77   909.5  1695.3   971.9 1717.57  1004.3 1725.981033.007 1730.16
#Mann= 9 ,-1 , 0
       0      .1       0   172.6    .035       0   475.9     .04       0
   574.7      .1       0  760.61    .045       0  791.73     .08       0
   871.6      .1       0   880.4     .08       0   971.9      .1       0
#XS Ineff= 1 ,-1
  136.23     7501628.932
Permanent Ineff=
       T
Bank Sta=760.61,791.73
XS Rating Curve= 0 ,0
Exp/Cntr(USF)=0,0
Exp/Cntr=0.3,0.1

Type RM Length L Ch R = 1 ,11675   ,310.7,310.9,310.6
XS GIS Cut Line= 4
2025895.45494778286557.8226466422026022.94527025287026.987033358
2026058.64256055287363.5614846982026099.43946374287529.298903919
#Sta/Elev= 30
       0 1761.46    17.3 1748.19    30.8 1735.46    43.3 1725.75    78.4 1691.79
   105.6 1667.52   132.8 1646.68   160.9  1627.6   170.2 1623.97     177 1623.04
   190.6 1625.04   309.6  1623.3   323.2 1624.44     462  1626.8   522.9  1623.1
   539.2 1624.45   587.4 1622.32   678.1 1620.91   717.4 1622.35  732.461618.539
   740.5 1617.44     757 1617.46  759.211618.538   760.3 1619.07   770.2 1632.98
   789.9 1650.42   803.1 1657.28   889.3 1684.51   920.9 1690.51995.3249 1709.14
#Mann= 5 ,-1 , 0
       0      .1       0   323.2    .035       0   539.2     .04       0
  732.46    .045       0  759.21      .1       0
#XS Ineff= 2 , 0
       0  718.16 1627.76               0
Permanent Ineff=
       T       F
Bank Sta=732.46,759.21
XS Rating Curve= 0 ,0
Exp/Cntr(USF)=0,0
Exp/Cntr=0.3,0.1

Type RM Length L Ch R = 1 ,11364   ,345.7,339.6,335.8
XS GIS Cut Line= 4
2025607.32681898 286680.213356222025706.76927051286981.090517267
2025755.21559305287445.1552910842025811.31133494287723.084194084
#Sta/Elev= 30
       0 1741.25      51 1702.11      59 1698.09   108.3 1658.16   123.6  1648.2
   147.3 1636.32   161.6 1626.91   175.4    1620   213.4 1620.77   275.6 1618.65
   292.7 1620.01     416 1618.08   518.3 1620.16   567.8 1619.87   577.7 1618.03
   617.3 1619.35  631.881615.224   650.3 1613.31   660.1 1613.67  664.011615.225
   673.3    1618   719.2  1617.7   742.6 1617.65   745.9 1619.43   755.8 1629.01
   765.7 1633.69   896.2 1653.48   939.5  1661.6  1015.9 1686.261067.005 1698.55
#Mann= 7 ,-1 , 0
       0      .1       0   213.4    .035       0   518.3     .04       0
   617.3     .06       0  631.88    .045       0  664.01     .06       0
   719.2      .1       0
#XS Ineff= 2 , 0
             614 1624.41
Permanent Ineff=
       F       F
Bank Sta=631.88,664.01
XS Rating Curve= 0 ,0
Exp/Cntr(USF)=0,0
Exp/Cntr=0.3,0.1

Type RM Length L Ch R = 1 ,11025   ,277.1,272.1,266.2
XS GIS Cut Line= 4
 2025191.7083677286833.2017431932025372.74462562287210.573097726
2025492.58552875287483.4023878272025704.21946406287781.729742424
#Sta/Elev= 30
       0 1692.65    29.6 1686.33    62.4 1676.27    73.2 1671.59   112.5 1649.41
   132.2 1642.58   220.7 1631.78   266.1 1627.91     292  1621.4   301.9 1620.26
   335.3  1619.6   349.8 1617.05     368 1619.98   484.7 1617.59   490.6 1616.29
  496.631611.688     505 1610.22  524.071611.684   566.8 1615.04   651.9 1613.45
   691.3 1615.16   852.1  1614.1   897.5 1615.66   918.6    1620   949.2    1630
   993.9 1649.58  1033.6 1670.41    1048 1673.26  1059.8 1680.841082.309 1688.69
#Mann= 6 ,-1 , 0
       0      .1       0  458.55    .035       0  488.55     .06       0
  496.63    .045       0  524.07     .06       0  698.55      .1       0
#XS Ineff= 2 , 0
                          814.99         1620.51
Permanent Ineff=
       F       F
Bank Sta=496.63,524.07
XS Rating Curve= 0 ,0
Exp/Cntr(USF)=0,0
Exp/Cntr=0.3,0.1

Type RM Length L Ch R = 1 ,10753   ,370.6,376,379.5
XS GIS Cut Line= 4
2024867.88294861287113.6804526432025110.11456132287368.661097598
2025543.58165774 287802.128194022025650.67352862287896.471032654
#Sta/Elev= 30
       0 1664.85    15.8 1662.01    34.9 1662.25    75.3 1650.81   125.4 1642.39
   263.5 1631.77   357.3  1626.7   373.5 1622.78   393.1 1622.29     407 1614.64
   419.9 1612.25   484.9 1611.39   539.5 1612.72   550.9 1609.03   573.1 1607.57
  588.171609.032   598.6 1612.72   619.4 1611.24   669.5 1613.14   742.4 1611.14
   932.6  1611.8   943.2 1614.97   962.8 1625.78   988.2 1643.34  1023.2 1671.32
  1040.6 1681.65  1060.4 1688.91  1081.3 1693.36  1097.5 1694.911107.434 1698.98
#Mann= 8 ,-1 , 0
       0      .1       0   361.7     .06       0   471.7     .04       0
   501.7      .1       0   550.9    .045       0  588.17      .1       0
   781.7    .035       0   891.7      .1       0
#XS Ineff= 2 , 0
          458.77  1616.1  865.37         1615.76
Permanent Ineff=
       F       F
Bank Sta=550.9,588.17
XS Rating Curve= 0 ,0
Exp/Cntr(USF)=0,0
Exp/Cntr=0.3,0.1

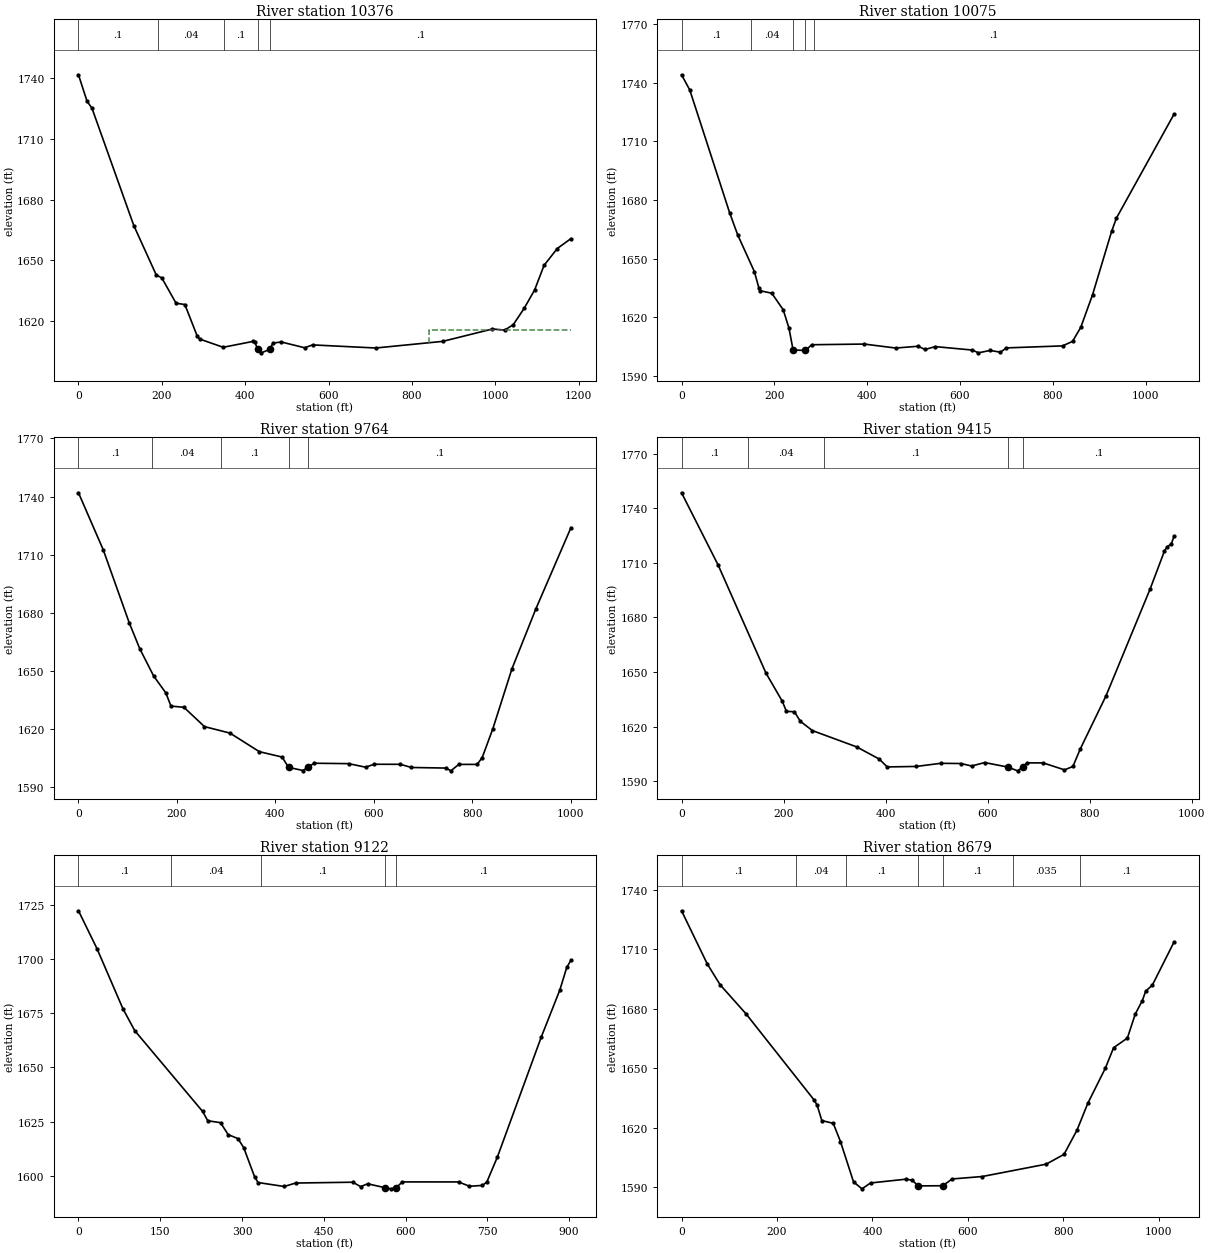
Type RM Length L Ch R = 1 ,10376   ,306.7,301.9,295.1
XS GIS Cut Line= 4
2024663.89843265287373.7607104972024827.08604542287534.398516818
2025020.87133558287812.3274198192025492.58552875288204.997613049
#Sta/Elev= 30
       0 1741.59    20.6 1728.48    32.2 1725.19   132.7 1667.17   186.4 1642.85
   200.2 1641.22   234.1 1628.81   255.3 1628.15   284.9 1612.57   290.6 1611.13
   347.2 1607.05   418.6 1609.94   422.7 1609.67  430.431606.012   438.6 1604.31
  458.831606.013   466.6 1609.13   486.6 1609.67   542.8 1606.81   561.6 1608.23
   713.1  1606.7   873.9 1609.97   993.3 1616.09  1022.7 1615.54  1043.2 1618.21
  1069.6 1626.36  1094.5 1635.37  1117.1 1647.51  1148.8 1655.811181.566 1660.71
#Mann= 5 ,-1 , 0
       0      .1       0     190     .04       0  348.99      .1       0
  430.43    .045       0  458.83      .1       0
#XS Ineff= 2 , 0
                          840.18         1615.46
Permanent Ineff=
       F       F
Bank Sta=430.43,458.83
XS Rating Curve= 0 ,0
Exp/Cntr(USF)=0,0
Exp/Cntr=0.3,0.1

Type RM Length L Ch R = 1 ,10075   ,317.5,310.6,298.3
XS GIS Cut Line= 4
2024480.31236828287702.685742488 2024615.4521101287797.028581121
2024946.92694855288044.3598067272025314.09907728288357.986000021
#Sta/Elev= 30
       0 1744.08    17.8 1736.26   103.8 1673.35     121 1662.16   156.9 1643.38
   166.8 1634.89     170 1633.53   194.4 1632.31   219.1 1623.84   231.4 1614.51
  240.421603.234   267.1 1603.02   280.5 1605.94   393.7 1606.28   461.6 1604.25
   509.7 1605.16   524.9  1603.5   546.6 1604.98   626.8 1603.21   639.8 1601.79
     665 1603.02   687.2 1602.12   700.2 1604.32     821 1605.34   842.6 1607.65
   860.4 1614.85   885.7 1631.48   926.8  1663.9   937.2 1670.741061.277 1723.89
#Mann= 5 ,-1 , 0
       0      .1       0     150     .04       0  240.42    .045       0
   267.1     .04       0  284.81      .1       0
Bank Sta=240.42,267.1
XS Rating Curve= 0 ,0
Exp/Cntr(USF)=0,0
Exp/Cntr=0.3,0.1

Type RM Length L Ch R = 1 ,9764    ,332.7,349,357.4
XS GIS Cut Line= 4
2024329.87378776288008.6625164342024674.09765844 288143.80225826
2024809.23740027288146.352064709 2025186.6087548288467.627677352
#Sta/Elev= 30
       0 1741.93    50.4 1712.48   103.3 1674.79   124.4 1661.61   152.6 1647.55
   177.6 1638.71   187.9 1631.97   214.2 1631.34     256 1621.38   307.7 1618.05
   367.6 1608.45   413.7 1605.69   426.8 1600.37   456.4 1598.74   466.2  1600.5
   479.2  1602.5   548.9 1602.29   583.4 1600.46   600.6 1601.97   654.1 1601.94
   676.5 1600.31   747.1 1600.01   756.5 1598.58   772.8  1601.9     810 1601.89
   820.3 1605.43   841.9 1620.26   880.7 1651.16   929.5 1682.191000.573 1723.92
#Mann= 5 ,-1 , 0
       0      .1       0     150     .04       0     290      .1       0
   426.8    .045       0   466.2      .1       0
Bank Sta=426.8,466.2
XS Rating Curve= 0 ,0
Exp/Cntr(USF)=0,0
Exp/Cntr=0.3,0.1

Type RM Length L Ch R = 1 ,9415    ,284.8,292.9,286
XS GIS Cut Line= 4
2024271.22823942288087.7065163692024559.35636821288278.942000085
2024862.78333571288541.5720643892025036.17017428288674.161999765
#Sta/Elev= 30
       0 1748.49    71.6 1708.85   165.5  1649.4   197.6 1633.86   205.5 1628.38
   221.2 1628.14     233 1622.86   256.7 1617.78   343.3 1608.84   387.3 1602.19
   403.3 1597.83   460.2  1598.1   507.9 1599.81   547.8  1599.7   568.7 1598.34
   594.3 1600.23  639.491597.761     659 1595.68   668.7 1597.81   677.1 1600.06
   709.1 1600.03   750.7 1596.21   767.2 1598.09   781.8 1607.79   832.1 1636.89
   918.7  1695.7   946.7  1716.5   951.4 1718.64   960.1 1720.37965.3901 1724.55
#Mann= 5 ,-1 , 0
       0      .1       0     130     .04       0     280      .1       0
  639.49    .045       0   668.7      .1       0
Bank Sta=639.49,668.7
XS Rating Curve= 0 ,0
Exp/Cntr(USF)=0,0
Exp/Cntr=0.3,0.1

Type RM Length L Ch R = 1 ,9122    ,441.5,442.9,433.5
XS GIS Cut Line= 4
2024169.23598143 288250.894129142024380.86991675288411.531935462
2024684.29688424288651.2137417192024890.83120666288794.002902894
#Sta/Elev= 30
       0 1722.12      34 1704.67    81.5 1677.06   103.2 1666.96   227.8 1629.75
   237.2 1625.48   260.6 1624.59   274.6  1619.1   292.5 1617.28   303.1 1613.12
   323.2 1599.61   329.5 1597.04   377.4 1595.22   398.4 1596.81   503.5 1597.19
   517.5 1595.16   530.7 1596.45   561.9 1594.69     573 1594.14   582.9 1594.71
   594.2 1597.33   697.3 1597.32   717.3 1595.32   741.2 1595.72   749.2 1597.29
   768.6 1608.82   848.9 1663.92   883.2 1685.72   895.9 1696.14903.4543  1699.3
#Mann= 5 ,-1 , 0
       0      .1       0     170     .04       0  335.69      .1       0
   561.9    .045       0   582.9      .1       0
Bank Sta=561.9,582.9
XS Rating Curve= 0 ,0
Exp/Cntr(USF)=0,0
Exp/Cntr=0.3,0.1

Type RM Length L Ch R = 1 ,8679    ,333.9,332.9,331.9
XS GIS Cut Line= 4
2023960.15185257288493.1257418472024197.28385238288714.958902958
2024477.76256183288939.3418705182024725.09378744289184.123289674
#Sta/Elev= 30
       0 1729.53    53.8 1702.75    80.8  1692.2   134.8 1677.61   278.5 1633.82
   284.3 1631.31   293.9 1623.67   317.9 1622.25     333 1613.07   360.4  1592.7
   378.1  1589.2     396 1592.16   469.6 1594.06   483.2 1593.59   495.8 1590.69
   547.1 1590.76   567.2 1594.19   630.2 1595.42   764.1 1601.66   801.4 1606.59
   828.7 1618.85   851.1 1632.27   888.1 1650.13   905.3  1660.4   934.2 1665.29
   950.6 1677.35   965.6 1684.23   972.5 1688.95   986.5 1692.011031.886 1713.73
#Mann= 7 ,-1 , 0
       0      .1       0     240     .04       0  344.72      .1       0
   495.8    .045       0   547.1      .1       0  693.91    .035       0
  833.91      .1       0
Bank Sta=495.8,547.1
XS Rating Curve= 0 ,0
Exp/Cntr(USF)=0,0
Exp/Cntr=0.3,0.1

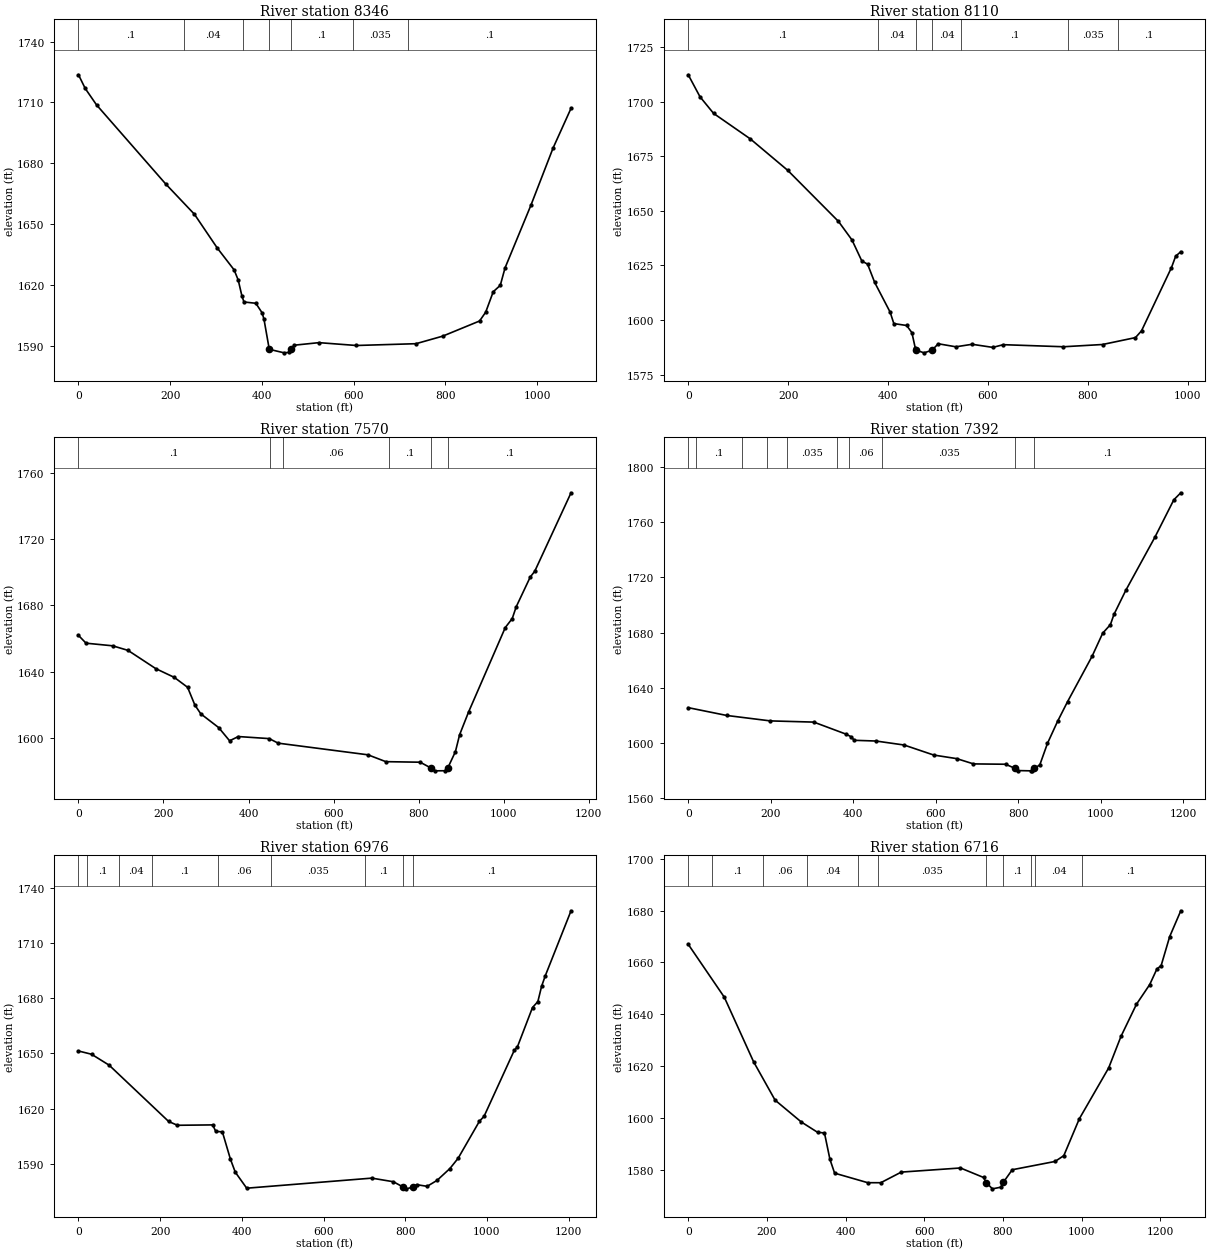
Type RM Length L Ch R = 1 ,8346    ,240.8,236.8,232.2
XS GIS Cut Line= 4
2023730.66927211288735.3573545542024013.69778801288954.640709215
2024355.37185225289191.7727090232024595.05365851289372.808966941
#Sta/Elev= 30
       0 1723.63    14.7 1716.89    39.4 1708.79   190.1 1669.89   252.9 1654.94
   302.7 1638.31   339.4 1627.56   348.4 1622.54   356.7 1614.47     361 1611.73
   386.8  1611.1   400.7 1606.33   404.7 1603.11  416.12 1588.43   448.6 1586.69
   458.9 1586.94  463.021588.434   470.4 1590.45   524.5 1591.71     606 1590.31
   736.1 1591.19   794.5 1594.92   874.8 1602.37   888.2 1606.74   904.6 1616.77
     920 1619.94   930.3 1628.49   986.6 1659.27  1035.1 1687.541074.306 1707.12
#Mann= 7 ,-1 , 0
       0      .1       0     230     .04       0  358.04      .1       0
  416.12    .045       0  463.02      .1       0  598.04    .035       0
  718.04      .1       0
Bank Sta=416.12,463.02
XS Rating Curve= 0 ,0
Exp/Cntr(USF)=0,0
Exp/Cntr=0.3,0.1

Type RM Length L Ch R = 1 ,8110    ,518.1,539.1,543.6
XS GIS Cut Line= 4
 2023529.2345626288954.6407092152023888.75727198289166.274644527
2024189.63443303289283.5657412072024406.36798124289400.856837886
#Sta/Elev= 30
       0 1712.43    23.6 1702.33    50.8 1694.72   124.3 1683.04   199.3 1668.61
   300.9  1645.2     328 1636.69   347.7 1627.05   359.2 1625.61   373.5  1617.2
   404.4  1603.6   411.8 1598.35   437.5 1597.48     448 1594.18   454.6 1587.27
  456.971586.128   472.3 1584.94  488.191586.126   500.8  1589.1   536.1 1587.71
   568.6 1588.86     610 1587.44   631.1 1588.68   751.5 1587.73   829.8 1588.76
   895.8 1591.93   907.9 1595.03   967.9 1624.03   976.3 1629.25986.5542 1631.31
#Mann= 7 ,-1 , 0
       0      .1       0     380     .04       0  456.97    .045       0
  488.19     .04       0  547.19      .1       0  760.12    .035       0
  860.12      .1       0
Bank Sta=456.97,488.19
XS Rating Curve= 0 ,0
Exp/Cntr(USF)=0,0
Exp/Cntr=0.3,0.1

Type RM Length L Ch R = 1 ,7570    ,182.8,178.5,174.3
XS GIS Cut Line= 4
2023445.09094976289056.6329671972023942.30320742289462.052192675
2024181.98501368289653.287676391 2024347.7224329289783.327805317
#Sta/Elev= 30
       0 1661.89    17.8 1657.19    80.4 1655.61   116.5 1652.85     182 1641.81
   225.5 1636.54   256.7 1630.56   273.8 1619.85   287.8 1614.53   329.8 1606.25
   355.5 1598.28   376.1 1600.83   448.7 1599.59   469.8 1596.84   681.1  1589.8
   723.1 1585.67   803.9 1585.34  828.791581.901   838.3 1580.13   861.7 1580.19
  868.921581.899   886.8  1591.7   896.7 1601.93   917.7  1615.6  1004.1 1666.62
  1020.5 1672.06  1029.8 1679.14  1062.8  1697.1  1073.5 1700.631158.837 1747.99
#Mann= 6 ,-1 , 0
       0      .1       0     450     .04       0     480     .06       0
  731.55      .1       0  828.79    .045       0  868.92      .1       0
Bank Sta=828.79,868.92
XS Rating Curve= 0 ,0
Exp/Cntr(USF)=0,0
Exp/Cntr=0.3,0.1

Type RM Length L Ch R = 1 ,7392    ,411.4,415.9,416.1
XS GIS Cut Line= 4
 2023308.1254206289348.9163361362023786.60761854289619.636527075
 2024139.1734486 289811.658988092024331.19590962289959.610720348
#Sta/Elev= 30
       0 1625.41    93.2 1619.74   198.8 1615.79   304.3 1614.91   382.1  1606.2
   394.8 1604.25   402.3 1601.69   455.2 1601.16     523 1598.27     595 1590.97
   650.7 1588.37   691.3 1584.54   769.2 1584.29  792.411581.217   799.7 1579.69
   829.5  1579.5   833.3 1579.58  838.541581.214     852 1583.84   870.6 1599.49
   894.9 1615.37   919.1 1629.69   978.7 1662.76  1004.4 1679.52  1023.1 1685.74
  1031.7 1693.15  1060.5 1710.73  1130.7 1749.14  1176.7 1776.411193.635 1781.54
#Mann= 10 ,-1 , 0
       0    .035       0      20      .1       0     130    .035       0
     190      .1       0     240    .035       0     360     .04       0
     390     .06       0     470    .035       0  792.41    .045       0
  838.54      .1       0
Bank Sta=792.41,838.54
XS Rating Curve= 0 ,0
Exp/Cntr(USF)=0,0
Exp/Cntr=0.3,0.1

Type RM Length L Ch R = 1 ,6976    ,265.9,260.2,257.4
XS GIS Cut Line= 4
2023144.43414236289625.9323454692023399.41478732289821.102715681
2023915.67189562290167.3727273482024148.61717619 290290.14118603
#Sta/Elev= 30
       0 1651.33    31.9 1649.57    75.1 1643.61   220.8 1612.98   242.3 1610.91
   328.6 1611.12   336.1 1607.59   352.3 1607.34   372.1 1592.44   383.9 1585.41
   411.9 1576.68   718.2 1582.16   771.1 1580.19   794.8 1577.31   802.7 1576.33
  820.251577.391   827.9 1578.61   853.7  1577.7   877.8  1580.9   909.4 1587.36
   929.6 1592.97   981.9 1613.17     993 1615.74  1067.2 1651.76  1074.6 1653.49
  1111.7 1674.99  1124.8  1678.2  1133.9 1686.49  1142.9 1692.211206.049 1727.62
#Mann= 9 ,-1 , 0
       0     .06       0      20      .1       0     100     .04       0
     180      .1       0   341.1     .06       0   471.1    .035       0
   701.1      .1       0   794.8    .045       0  820.25      .1       0
Bank Sta=794.8,820.25
XS Rating Curve= 0 ,0
Exp/Cntr(USF)=0,0
Exp/Cntr=0.3,0.1

Type RM Length L Ch R = 1 ,6716    ,490.8,505.7,504.5
XS GIS Cut Line= 5
2022980.74286412289846.2859892572023169.61741594289997.385630711
2023493.85206322290214.5913653022023802.34716453290375.134734348
2024047.88408189290491.607374636
#Sta/Elev= 30
       0    1667    91.7 1646.58     166  1621.7   220.7 1606.87   287.2 1598.45
   328.5 1594.47   346.2  1594.2   360.1 1584.02     372 1578.69   456.2 1575.01
   489.3    1575   541.4  1579.1   691.8 1580.69   750.4 1577.03   757.7 1574.97
   773.1 1572.64   794.2 1573.27  801.041575.224   823.4 1580.01   932.2 1583.21
   954.4 1585.45   993.8 1599.66  1068.4  1619.3  1099.7 1631.47  1139.1 1643.89
  1172.7 1651.46  1190.8 1657.43  1201.8 1658.82  1223.5 1669.991251.673 1679.94
#Mann= 11 ,-1 , 0
       0     .06       0      60      .1       0     190     .06       0
  301.88     .04       0  431.88      .1       0  481.88    .035       0
   757.7    .045       0  801.04      .1       0  872.14     .06       0
  882.14     .04       0  999.91      .1       0
Bank Sta=757.7,801.04
XS Rating Curve= 0 ,0
Exp/Cntr(USF)=0,0
Exp/Cntr=0.3,0.1