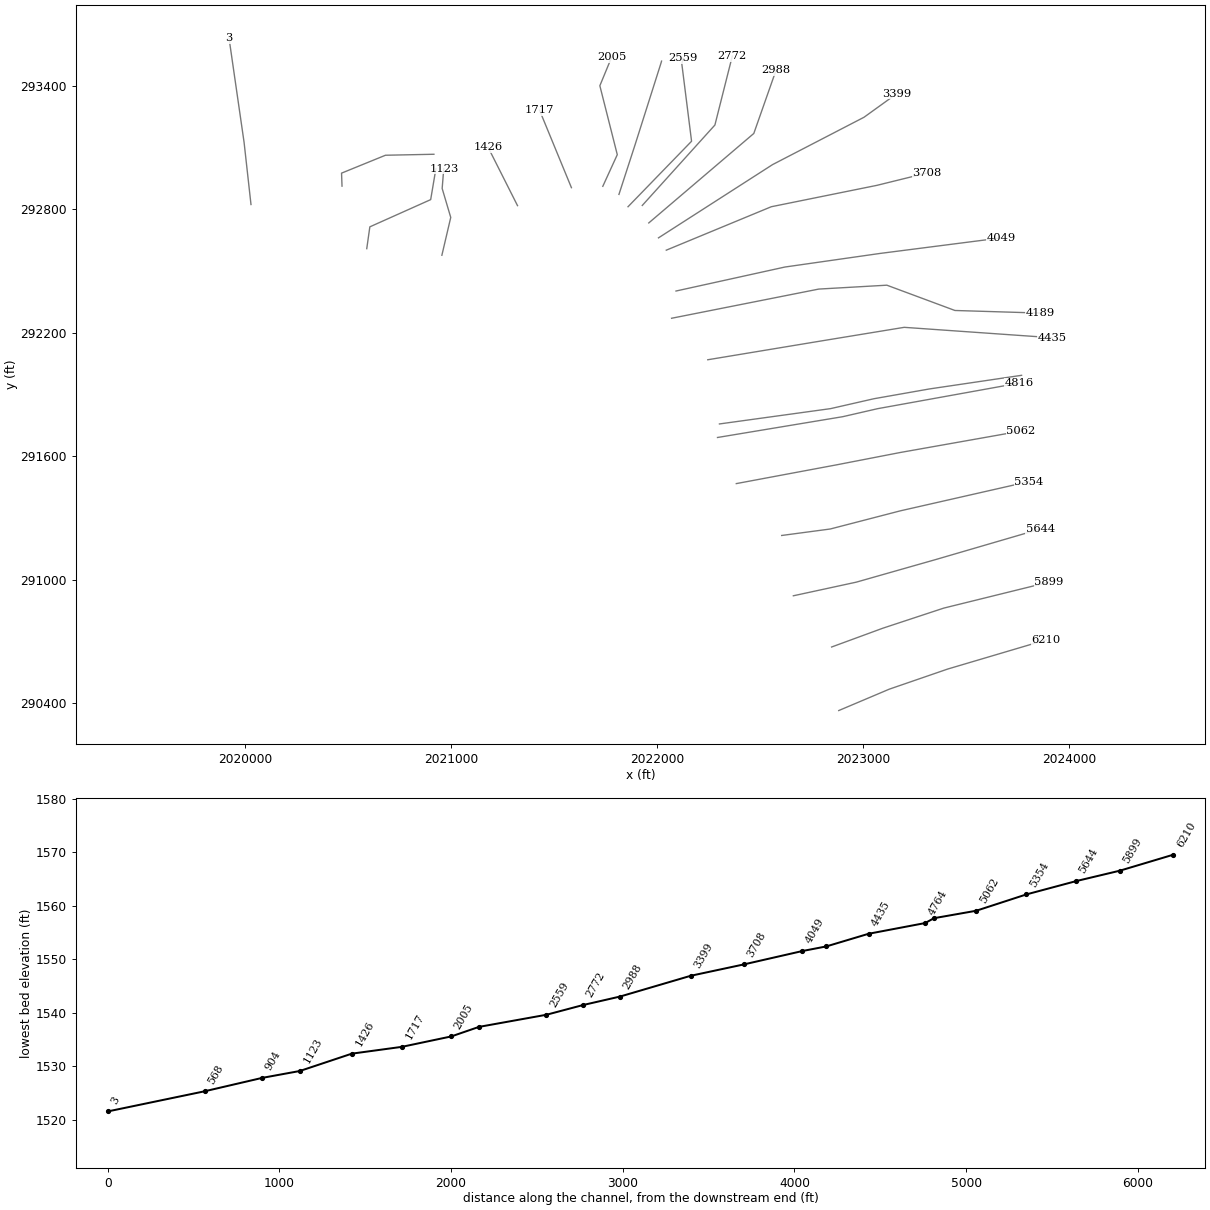
HEC-RAS study LICKCK1.prj: LICKCK1

--- LICKCK1.g01 (geometry) --- (continued)

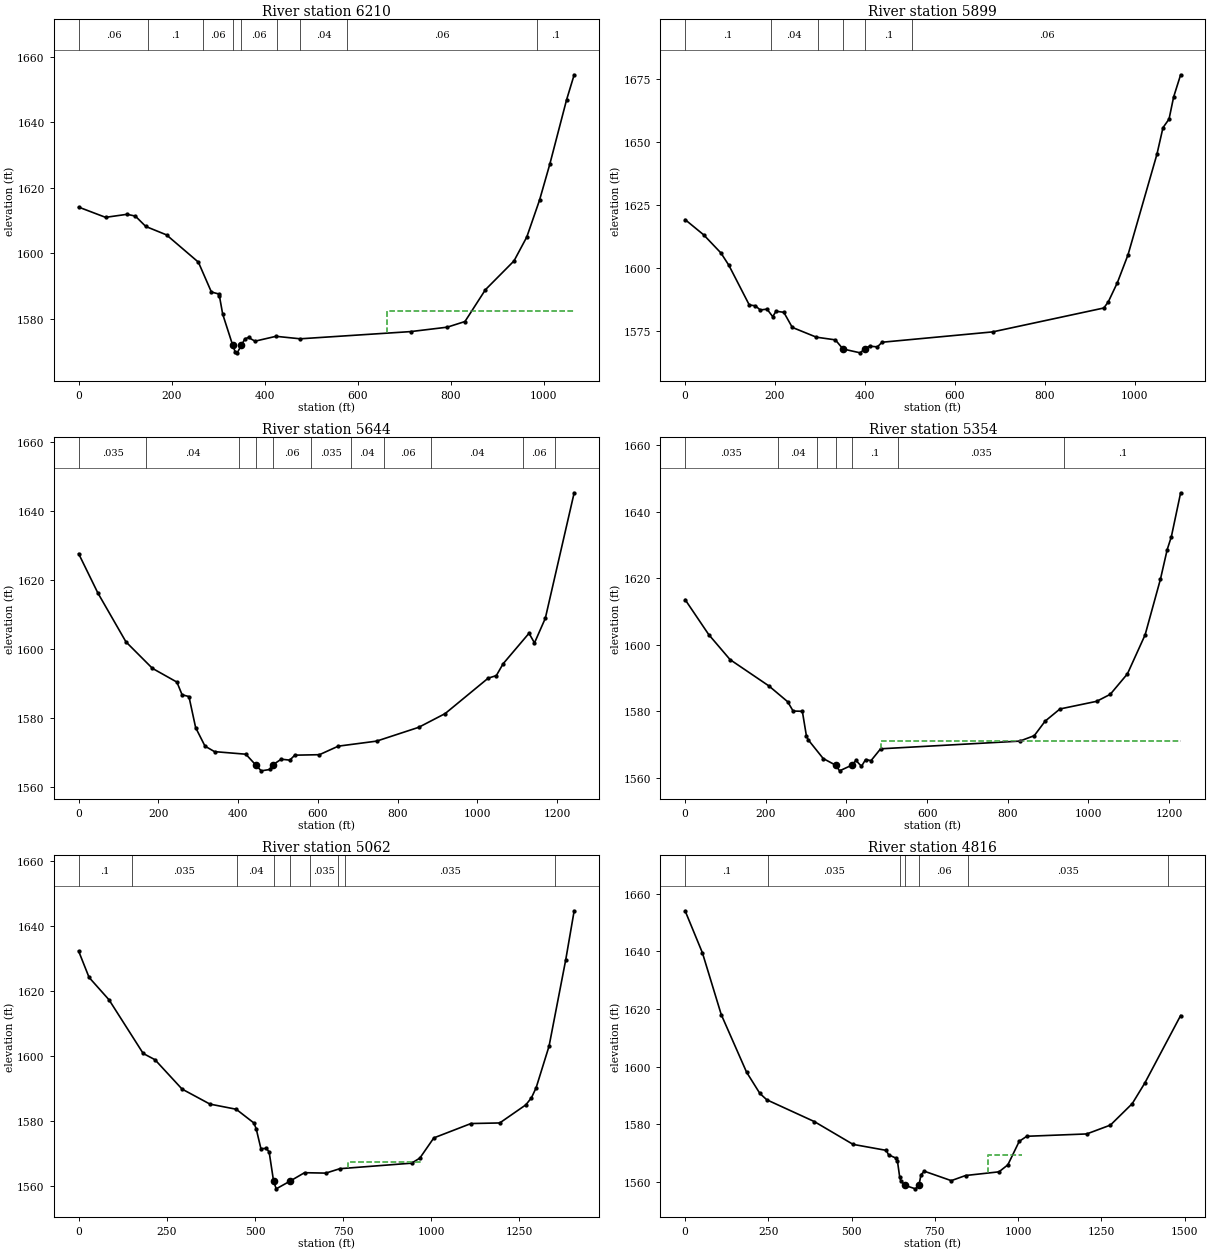
Type RM Length L Ch R = 1 ,6210    ,306.4,311.7,316.8
XS GIS Cut Line= 4
2022883.15767901290365.6910067572023128.69459638290469.572010257
 2023412.0064241290567.1571953632023890.48862204290708.813109227
#Sta/Elev= 30
       0 1614.09    57.9 1610.96   104.2 1611.89   121.9 1611.34   144.4 1608.17
   188.9  1605.6   257.4 1597.27   285.4 1588.14   300.7 1587.56   302.8 1586.82
   309.7 1581.37  331.331571.811   336.8 1569.76   340.9 1569.55  349.631571.811
   357.4 1573.83   365.2 1574.25   379.1 1573.11   424.2  1574.6   476.3 1573.84
   713.6 1576.04   792.3 1577.39   830.5 1579.12   874.4 1588.83   935.9 1597.64
   963.4 1604.95   990.8 1616.22  1012.7 1627.11  1048.9 1646.861065.266 1654.53
#Mann= 9 ,-1 , 0
       0     .06       0     150      .1       0  266.61     .06       0
  331.33    .045       0  349.63     .06       0  426.61      .1       0
  476.61     .04       0  576.25     .06       0  986.25      .1       0
#XS Ineff= 2 , 0
                          662.07         1582.37
Permanent Ineff=
       F       F
Bank Sta=331.33,349.63
XS Rating Curve= 0 ,0
Exp/Cntr(USF)=0,0
Exp/Cntr=0.3,0.1

Type RM Length L Ch R = 1 ,5899    ,256.1,254.8,253.5
XS GIS Cut Line= 4
2022848.53067785 290674.186108062023097.21550441290765.475474772
2023393.11896892290863.0606598782023903.08025883290988.977027757
#Sta/Elev= 30
       0 1619.24    41.3 1613.22    79.7 1606.04    97.2 1601.21   142.7 1585.49
   156.2 1585.16   167.1 1583.51   182.1 1583.84   194.9 1580.86   202.1 1583.02
   219.5 1582.58   238.3 1576.62   291.9 1572.75   334.1 1571.69  351.051568.079
   389.3 1566.56  398.88 1568.08   410.1 1569.21   427.5 1568.91   437.9 1570.75
   683.7 1574.84     931 1584.29   940.9 1586.72   961.2 1594.35   984.8 1605.34
    1049 1645.03  1062.5 1655.59    1076 1658.99  1086.2 1667.741101.767  1676.5
#Mann= 6 ,-1 , 0
       0      .1       0     190     .04       0  294.91      .1       0
  351.05    .045       0  398.88      .1       0  504.91     .06       0
Bank Sta=351.05,398.88
XS Rating Curve= 0 ,0
Exp/Cntr(USF)=0,0
Exp/Cntr=0.3,0.1

Type RM Length L Ch R = 1 ,5644    ,286.7,290.1,281.7
XS GIS Cut Line= 4
2022662.80403522290922.8709346212022968.15122733290988.977027757
2023355.34405856291099.1538496512023862.15743927291247.105581909
#Sta/Elev= 30
       0  1627.7    48.4 1616.24   118.7 1602.08     185 1594.39   246.5 1590.39
   259.5 1586.71   276.7 1586.19   293.5 1577.16     317 1571.78   340.9 1570.19
   419.4 1569.44  443.881566.362     458 1564.61   480.8 1565.02  487.261566.363
   508.1 1567.99   529.7 1567.72   542.2 1569.16     604  1569.3   651.3 1571.78
   747.3 1573.24   852.9 1577.25   919.3 1581.24  1027.2 1591.53  1047.7 1592.28
  1064.7 1595.71  1129.7 1604.58  1143.4 1601.77  1170.6 1608.941242.952 1645.39
#Mann= 11 ,-1 , 0
       0    .035       0     170     .04       0  402.42      .1       0
  443.88    .045       0  487.26     .06       0  582.42    .035       0
  682.42     .04       0  764.98     .06       0  884.98     .04       0
 1114.98     .06       0 1194.98      .1       0
Bank Sta=443.88,487.26
XS Rating Curve= 0 ,0
Exp/Cntr(USF)=0,0
Exp/Cntr=0.3,0.1

Type RM Length L Ch R = 1 ,5354    ,292.7,292,287.7
XS GIS Cut Line= 4
2022606.14166968291215.6264899392022842.23485945291247.105581909
2023182.20905272291335.2470394242023805.49507372291476.902953287
#Sta/Elev= 30
       0 1613.58    58.6 1603.06   111.5 1595.54   207.6 1587.65   254.2  1582.9
   267.8 1580.09   290.7 1580.01   300.6 1572.73   305.1 1571.47   342.4 1565.82
  373.671563.789     383 1562.12   413.5 1563.83   423.7 1565.26   437.3 1563.46
   447.4 1565.51     461 1565.19   484.7 1568.74   829.7 1571.05   865.7 1572.69
   892.6 1577.05   929.4 1580.71  1020.4 1583.01  1054.1 1585.11  1096.6 1591.25
  1140.5 1602.98  1178.6 1619.76  1195.3 1628.62  1205.5 1632.441228.577 1645.67
#Mann= 7 ,-1 , 0
       0    .035       0     230     .04       0  328.18      .1       0
  373.67    .045       0   413.5      .1       0  528.18    .035       0
   939.4      .1       0
#XS Ineff= 2 , 0
                          484.86         1571.02
Permanent Ineff=
       F       F
Bank Sta=373.67,413.5
XS Rating Curve= 0 ,0
Exp/Cntr(USF)=0,0
Exp/Cntr=0.3,0.1

Type RM Length L Ch R = 1 ,5062    ,241.7,245.9,240
XS GIS Cut Line= 4
2022385.78802589291467.4592256972022873.71395142291558.748592409
2023182.20905272291618.5588671512023767.72016336291722.439870651
#Sta/Elev= 30
       0 1632.25    29.6 1624.15    86.3 1617.24   183.1 1600.74   216.5 1598.82
   293.3 1589.78   372.5 1585.15   446.8 1583.57   496.9 1579.35   503.5 1577.57
   516.9 1571.46   532.6  1571.5   540.3 1570.41   552.91561.386   560.4 1559.07
  598.591561.389   640.6 1564.04     701 1563.91   740.8 1565.27   944.3 1566.97
   967.6 1568.53  1007.3 1574.75  1112.6 1579.17  1194.2 1579.35  1268.2 1584.92
  1284.2 1587.11  1297.5 1590.22  1334.1 1603.01  1381.4  1629.61405.287 1644.66
#Mann= 9 ,-1 , 0
       0      .1       0     150    .035       0     450     .04       0
   552.9    .045       0  598.59      .1       0  656.39    .035       0
  736.39     .06       0  756.39    .035       0 1350.63      .1       0
#XS Ineff= 1 ,-1
  765.19  976.961567.448
Permanent Ineff=
       T
Bank Sta=552.9,598.59
XS Rating Curve= 0 ,0
Exp/Cntr(USF)=0,0
Exp/Cntr=0.5,0.3

Type RM Length L Ch R = 1 ,4816    ,51.3,51.8,51.5
XS GIS Cut Line= 4
2022294.54460577291691.3509040562022902.67344399291792.323239458
2023072.49055353291831.335278136 2023758.6434691291955.255871584
#Sta/Elev= 30
       0 1654.07    52.1 1639.46   108.5 1618.09   184.6 1598.12   224.5 1590.75
   245.4 1588.54     388    1581   504.4 1573.09   604.2 1571.01   610.8 1569.49
   634.3 1568.27   637.7 1567.23   644.4 1561.74   647.8 1560.44  659.531558.916
   691.6 1557.68   702.21558.914   708.4  1562.6   718.5 1563.78   799.2 1560.52
   842.3  1562.3   942.6 1563.58   969.1    1566  1003.2 1574.13  1025.8  1575.9
  1205.9 1576.71  1277.1 1579.78  1342.6 1587.21  1380.1  1594.31487.948 1617.76
#Mann= 7 ,-1 , 0
       0      .1       0     250    .035       0  646.45     .06       0
  659.53    .045       0   702.2     .06       0   850.7    .035       0
  1450.7      .1       0
#XS Ineff= 3 ,-1
  594.94  637.18 1560.37  711.11  746.31 1560.58  909.46 1012.371569.278
Permanent Ineff=
       F       F       T
Bank Sta=659.53,702.2
XS Rating Curve= 0 ,0
Exp/Cntr(USF)=0,0
Exp/Cntr=0.5,0.3

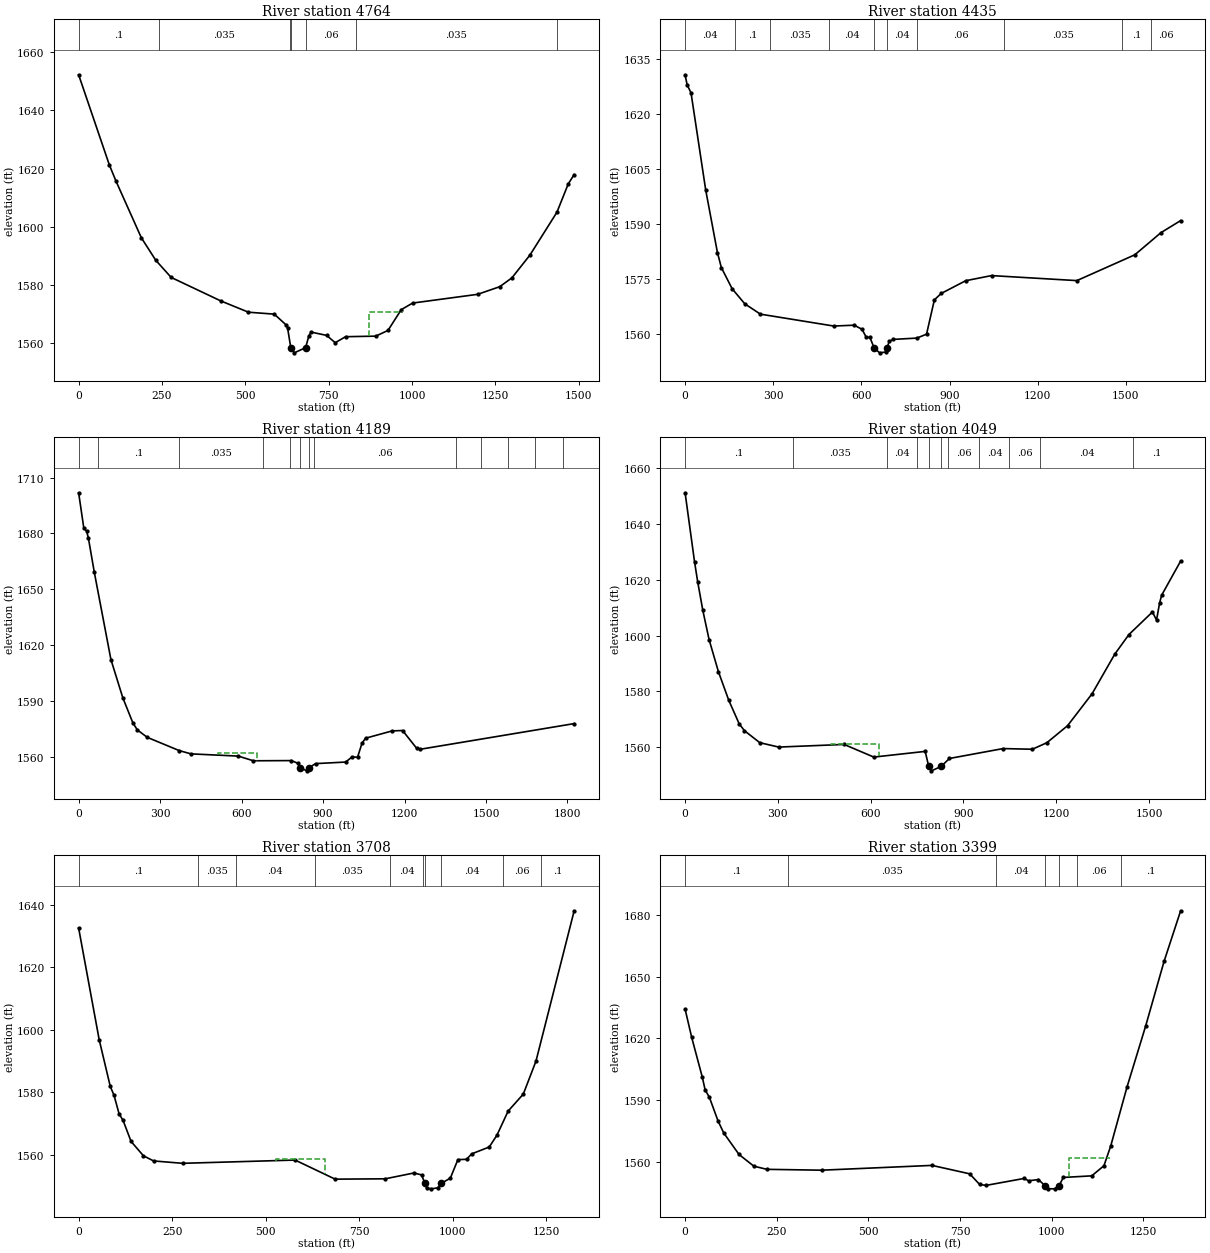
Type RM Length L Ch R = 1 ,4764    ,330.4,329,326.6
XS GIS Cut Line= 5
2022303.94238677291757.0668718182022843.67660186 291831.49918478
2023054.13194709291879.5266200322023323.86496659291927.053968454
2023770.86807256291993.160061591
#Sta/Elev= 30
       0 1652.24    92.1  1621.3     112 1615.75   188.1 1596.28   231.2 1588.58
   277.6 1582.66   426.6 1574.59   509.4 1570.72   586.9 1570.06   623.2 1566.26
   626.6 1565.42  636.441558.546   646.8 1556.77  680.931558.548   690.5 1562.57
   697.3 1563.89   743.9 1562.76   769.7 1560.25   800.8 1562.31   891.1  1562.5
   927.8 1564.45   967.9 1571.61  1001.9 1573.86  1196.9 1576.86  1263.2 1579.48
  1299.7 1582.52  1353.8 1590.34  1434.7 1605.04  1468.8  1614.81486.461 1617.98
#Mann= 7 ,-1 , 0
       0      .1       0     240    .035       0  634.84     .06       0
  636.44    .045       0  680.93     .06       0  830.71    .035       0
  1434.6      .1       0
#XS Ineff= 3 ,-1
  598.46   631.9 1558.74  688.23  726.95 1558.95   871.2  974.321570.905
Permanent Ineff=
       F       T       T
Bank Sta=636.44,680.93
XS Rating Curve= 0 ,0
Exp/Cntr(USF)=0,0
Exp/Cntr=0.5,0.3

Type RM Length L Ch R = 1 ,4435    ,248.6,245.8,243
XS GIS Cut Line= 4
2022247.28002122292068.7098823182022798.16413069 292159.99924903
2023201.09650791292226.1053421662023918.81980482292175.738795015
#Sta/Elev= 30
       0 1630.61     6.9 1627.87    20.2 1625.68    70.1 1599.19     110 1582.13
   123.3 1578.04   159.9 1572.27   203.1 1568.14   256.3 1565.32   505.7 1562.08
   575.6 1562.31   602.2 1561.18   616.6 1558.98   628.8    1559  643.041556.143
     662 1554.77     682 1554.99  687.461556.141   694.6 1557.94   708.9 1558.44
   788.4 1558.79   821.6 1559.86   848.2 1569.22   871.5 1570.97   954.7 1574.44
  1042.7 1575.84    1333 1574.47  1530.3 1581.51  1619.1 1587.541686.204 1590.84
#Mann= 10 ,-1 , 0
       0     .04       0     170      .1       0     290    .035       0
     490     .04       0  643.04    .045       0  687.46     .04       0
   788.4     .06       0 1086.72    .035       0 1486.72      .1       0
 1586.72     .06       0
Bank Sta=643.04,687.46
XS Rating Curve= 0 ,0
Exp/Cntr(USF)=0,0
Exp/Cntr=0.3,0.1

Type RM Length L Ch R = 1 ,4189    ,138.1,140.4,142.2
XS GIS Cut Line= 5
2022071.57642725292270.1683409572022786.15181497 292411.82425482
2023116.68228065292430.7117100022023447.21274633 292307.94325132
2023859.58885113292295.351614532
#Sta/Elev= 30
       0 1701.82    18.8 1683.12    29.5 1681.09    35.6 1677.78    57.4 1659.36
   118.9 1612.21   162.7 1591.65   199.8 1578.16   216.2  1574.4   252.8  1570.4
     370 1563.31   413.5 1561.53   587.8 1560.33   643.6 1557.81   783.8 1557.92
   806.8 1556.47  815.74 1554.19   839.7 1552.41   849.31554.192   872.5 1556.29
   983.1 1557.13  1007.2 1559.93    1027  1559.7  1043.4 1567.22  1056.5 1569.94
  1154.3 1573.86  1192.8 1574.08  1245.3 1564.42  1255.8 1563.951824.713 1577.79
#Mann= 13 ,-1 , 0
       0     .04       0      70      .1       0     370    .035       0
     680     .04       0  778.48    .035       0  815.74    .045       0
   849.3    .035       0  868.48     .06       0 1389.55     .04       0
 1482.14    .035       0 1582.14      .1       0 1682.14     .06       0
 1782.14      .1       0
#XS Ineff= 1 ,-1
512.8191  656.071561.746
Permanent Ineff=
       T
Bank Sta=815.74,849.3
XS Rating Curve= 0 ,0
Exp/Cntr(USF)=0,0
Exp/Cntr=0.3,0.1

Type RM Length L Ch R = 1 ,4049    ,338.6,340.9,342.4
XS GIS Cut Line= 4
2022093.03247057292402.3882571972022621.88121566292518.860897485
2023084.62386762292584.9669906212023673.28288745292660.516811348
#Sta/Elev= 30
       0  1651.2    30.5  1626.5    40.6 1619.36    57.4 1609.01    77.6 1598.57
   107.8 1587.06   141.4 1576.77     175 1568.37     192 1565.92   241.6 1561.63
   302.7 1560.06   514.3    1561   610.2 1556.47   776.4 1558.51  787.851553.099
   796.4 1551.54   827.91553.096   854.8 1555.97  1028.3 1559.52  1122.9 1559.28
  1169.8 1561.61  1236.7 1567.71  1316.1 1579.17  1389.6 1593.39  1435.2 1600.38
  1511.3 1608.48  1524.5 1605.56  1534.4 1611.71    1541 1614.481602.451 1626.72
#Mann= 11 ,-1 , 0
       0      .1       0     350    .035       0  651.52     .04       0
  751.52    .035       0  787.85    .045       0   827.9    .035       0
  851.52     .06       0  951.52     .04       0 1048.96     .06       0
 1148.96     .04       0 1448.96      .1       0
#XS Ineff= 1 ,-1
471.3735  627.541561.236
Permanent Ineff=
       T
Bank Sta=787.85,827.9
XS Rating Curve= 0 ,0
Exp/Cntr(USF)=0,0
Exp/Cntr=0.3,0.1

Type RM Length L Ch R = 1 ,3708    ,302.2,308.9,314.5
XS GIS Cut Line= 4
2022045.81383262292600.7065366062022555.77512253292811.616452803
2023068.88432163292915.497456303 2023311.2733298292975.307731045
#Sta/Elev= 30
       0 1632.52      55 1596.75    84.6 1581.82    94.6    1579   108.2 1573.04
   118.9 1570.93   140.2 1564.21   173.4  1559.6   200.5 1557.97     278 1557.21
   578.8 1558.25   685.9 1552.14   819.8 1552.25   896.8 1554.12   916.9  1553.5
  926.081550.757   930.3 1549.28   942.8 1549.04   960.4 1549.35  969.091550.758
   993.9 1552.46  1014.1 1558.39  1037.4 1558.49  1050.8 1560.22  1097.9 1562.43
  1118.5  1566.2  1148.5 1573.94    1189 1579.36  1222.9 1589.921325.033 1638.04
#Mann= 10 ,-1 , 0
       0      .1       0     320    .035       0     420     .04       0
  631.85    .035       0  831.85     .04       0  921.85    .035       0
  926.08    .045       0  969.09     .04       0 1135.37     .06       0
 1235.37      .1       0
#XS Ineff= 1 ,-1
  527.32  657.641558.559
Permanent Ineff=
       T
Bank Sta=926.08,969.09
XS Rating Curve= 0 ,0
Exp/Cntr(USF)=0,0
Exp/Cntr=0.3,0.1

Type RM Length L Ch R = 1 ,3399    ,396.2,411.5,430.6
XS GIS Cut Line= 4
2022008.03892225292660.5168113482022562.07094092293016.230550606
2023005.92613769293246.0279219852023163.32159754293359.352653076
#Sta/Elev= 30
       0 1634.25      18 1620.49    46.8  1601.3    54.6 1595.04    66.3 1591.39
    89.7    1580   105.3 1574.11   147.1 1563.63   187.5 1557.94   223.1  1556.4
   372.7 1555.98   673.7 1558.31   776.5 1554.22   803.7 1549.04   821.4  1548.6
   924.9 1551.97   937.5 1550.83   964.3 1551.44  981.62 1548.49   991.1 1546.98
  1008.1 1546.92 1020.671548.489    1032 1552.46  1109.6 1553.23  1142.9 1558.15
  1161.4 1567.75    1206  1596.5  1256.5 1625.91    1307 1657.481352.157 1682.03
#Mann= 7 ,-1 , 0
       0      .1       0     280    .035       0  848.39     .04       0
  981.62    .045       0 1020.67     .04       0 1068.39     .06       0
 1188.21      .1       0
#XS Ineff= 1 ,-1
 1046.66 1159.781561.784
Permanent Ineff=
       T
Bank Sta=981.62,1020.67
XS Rating Curve= 0 ,0
Exp/Cntr(USF)=0,0
Exp/Cntr=0.3,0.1

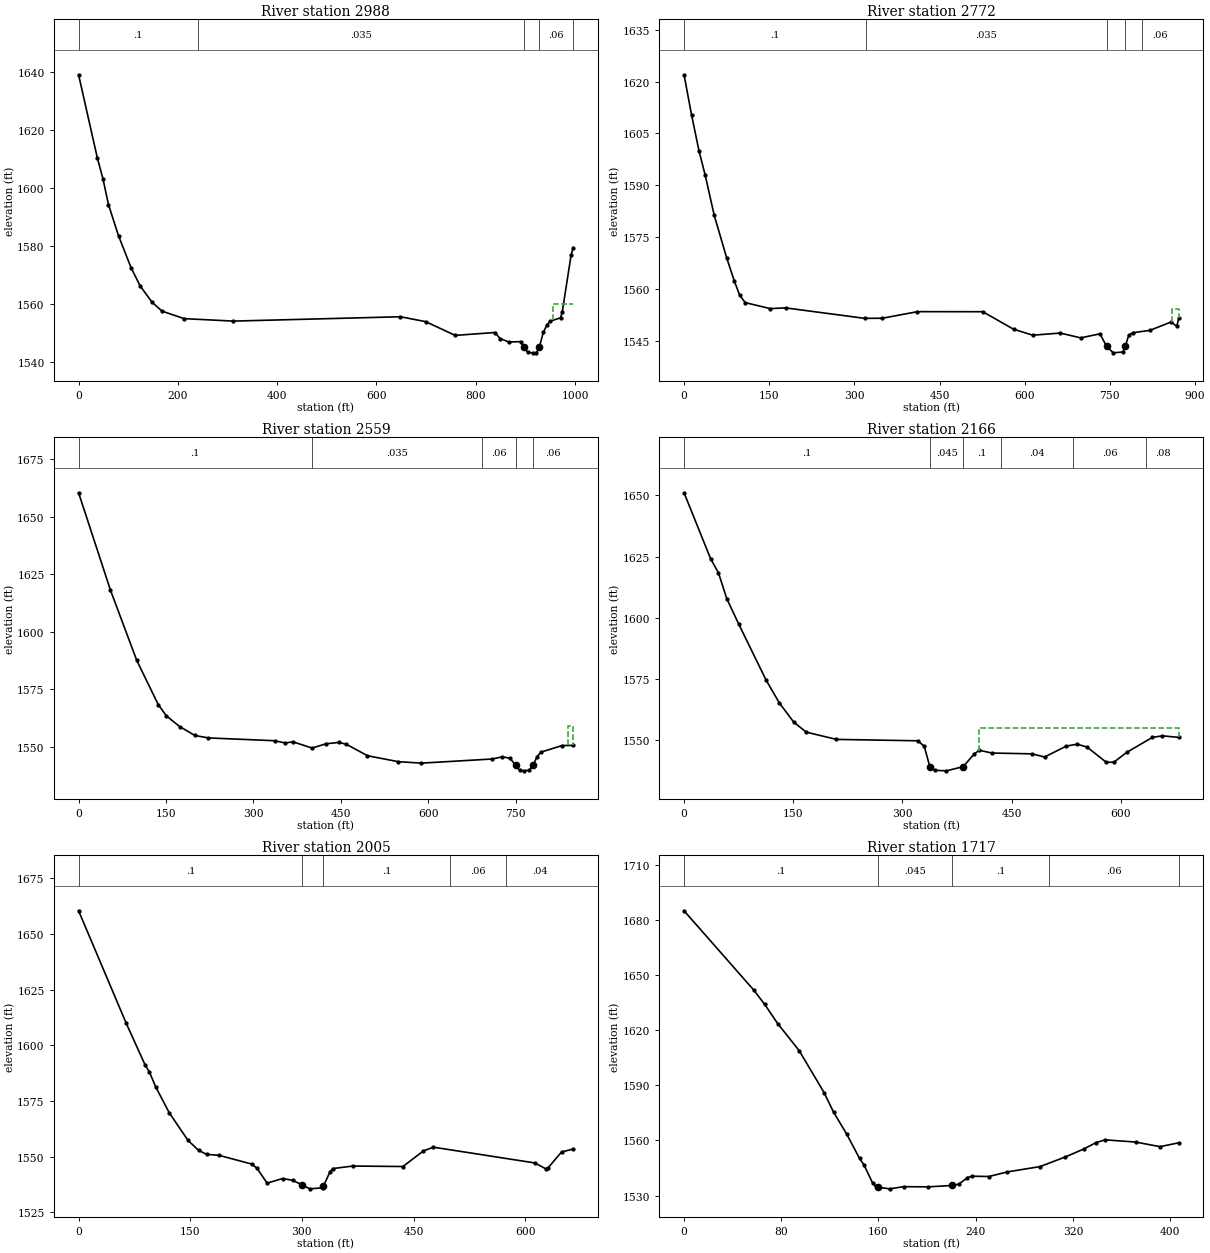
Type RM Length L Ch R = 1 ,2988    ,213.9,215.9,217.4
XS GIS Cut Line= 4
 2021960.8202843292732.9187228792022470.78157421293167.330192061
2022571.51466851293453.7899289852022580.02945054293474.722101481
#Sta/Elev= 30
       0 1638.97    37.9 1610.19    49.1  1603.1    60.2 1594.16    80.4 1583.44
   105.7 1572.42     124 1566.11   148.2 1560.45   168.2 1557.42   212.5 1554.84
     312 1553.99   648.2 1555.49   699.1  1553.8   758.5 1549.06   838.3 1550.05
     849 1547.98   866.4 1546.78   890.7 1546.91   897.41544.936   904.6 1543.17
   915.1 1543.04     922 1543.08   927.91544.941   935.9 1550.07   942.9 1552.55
   949.8 1553.96   970.7 1555.12   974.2 1557.23   991.9 1576.71   996.2 1579.35
#Mann= 5 ,-1 , 0
       0      .1       0     240    .035       0   897.4    .045       0
   927.9     .06       0  996.16      .1       0
#XS Ineff= 2 , 0
                          954.57        1559.968
Permanent Ineff=
       F       T
Bank Sta=897.4,927.9
XS Rating Curve= 0 ,0
Exp/Cntr(USF)=0,0
Exp/Cntr=0.3,0.1

Type RM Length L Ch R = 1 ,2772    ,205.7,212.5,220.9
XS GIS Cut Line= 3
2021929.34119233292817.9122711972022281.90702239293208.253011621
2022366.35006364293542.897656572
#Sta/Elev= 30
       0 1621.99    13.2 1610.38    26.5 1599.82    37.1 1593.02      53 1581.37
    75.1 1568.95    88.4 1562.32    97.8 1558.21   107.6    1556   151.7 1554.26
   178.8 1554.47   318.1 1551.44   349.2 1551.47   411.1 1553.38   526.1 1553.36
   580.2  1548.3     614 1546.56   662.6 1547.18   698.6 1545.78   732.5 1546.96
   744.21543.289   756.1 1541.45   773.1 1541.71   776.91543.299   783.2 1546.56
     790 1547.27   820.4 1547.96   857.7 1550.38   867.8 1549.12   871.1 1551.46
#Mann= 5 ,-1 , 0
       0      .1       0     320    .035       0   744.2    .045       0
   776.9    .035       0  805.99     .06       0
#XS Ineff= 2 , 0
                           858.8        1554.174
Permanent Ineff=
       F       T
Bank Sta=744.2,776.9
XS Rating Curve= 0 ,0
Exp/Cntr(USF)=0,0
Exp/Cntr=0.3,0.1

Type RM Length L Ch R = 1 ,2559    ,408,393.3,365.8
XS GIS Cut Line= 4
   2021860.08719292811.616452803 2022168.5822913293129.555281697
2022121.36365335293504.1564761362022126.56211221293532.063992135
#Sta/Elev= 30
       0  1660.3    54.5  1618.2    99.8 1587.58   136.7 1568.39   150.8 1563.47
   173.3 1558.88   199.6 1554.98   222.8 1553.92   336.4 1552.71     355 1551.72
   367.9 1552.24   400.9 1549.51   424.7 1551.39   447.1 1551.96   459.6 1551.16
   495.9  1546.2   548.5 1543.62   588.5 1542.98   710.1 1544.78   727.4 1545.73
   740.6 1545.08   750.2 1542.01     757 1539.86   763.8 1539.64   773.7 1539.93
   780.2    1542   786.9  1545.8   793.5 1547.75     830 1550.62     849 1550.66
#Mann= 5 ,-1 , 0
       0      .1       0     400    .035       0  693.01     .06       0
   750.2    .045       0   780.2     .06       0
#XS Ineff= 2 , 0
                          840.31        1559.086
Permanent Ineff=
       F       T
Bank Sta=750.2,780.2
XS Rating Curve= 0 ,0
Exp/Cntr(USF)=0,0
Exp/Cntr=0.3,0.1

Type RM Length L Ch R = 1 ,2166    ,147.9,161.1,175.1
XS GIS Cut Line= 4
2021816.01646124292871.4267275452021894.71419116293113.815735712
2022020.63055904 293510.452294532022022.84705516 293518.50556377
#Sta/Elev= 30
       0  1651.1    36.5 1624.12    47.2  1618.4    58.7 1607.77    74.8 1597.58
   112.5 1574.58   130.7 1565.22   150.7 1557.27   167.9 1553.19   209.3 1550.23
   321.1 1549.66   329.9 1547.39   337.51539.088   344.6 1537.59   360.3 1537.37
   383.41539.084   398.7 1544.35   405.6 1545.78   422.8 1544.65   477.9 1544.32
   495.1 1543.02   524.9 1547.49   539.9 1548.27   553.5 1547.09   579.7  1540.9
   590.2 1540.88   607.7 1544.88   643.1 1551.04   656.9 1551.69   679.3 1551.06
#Mann= 6 ,-1 , 0
       0      .1       0   337.5    .045       0   383.4      .1       0
  434.84     .04       0  534.84     .06       0  634.84     .08       0
#XS Ineff= 2 , 0
                          404.73        1554.917
Permanent Ineff=
       F       T
Bank Sta=337.5,383.4
XS Rating Curve= 0 ,0
Exp/Cntr(USF)=0,0
Exp/Cntr=0.3,0.1

Type RM Length L Ch R = 1 ,2005    ,288.6,288.3,290.6
XS GIS Cut Line= 4
2021737.59463322292910.6689409172021807.90713319 293064.31477426
2021723.27171654293398.9501909022021780.63330311 293537.82561098
#Sta/Elev= 30
       0 1660.34    63.9 1609.93    89.2 1591.28    95.1 1588.03   103.6 1581.34
   121.7 1569.75   146.9 1557.37   161.1 1552.87     172 1551.06   188.9 1550.61
   232.9 1546.67   239.7 1544.77   253.2 1538.16     274 1540.21   287.5 1539.44
   300.2 1537.35   310.7 1535.59   327.7 1536.05   328.91536.766   337.8 1543.32
   341.5 1544.68   368.3 1545.82   435.7  1545.6     463 1552.56   476.6 1554.28
   613.2 1547.19   627.4 1544.59   630.9 1545.12   648.7 1552.13   664.4 1553.44
#Mann= 5 ,-1 , 0
       0      .1       0   300.2    .045       0   328.9      .1       0
  498.97     .06       0  574.14     .04       0
Bank Sta=300.2,328.9
XS Rating Curve= 0 ,0
Exp/Cntr(USF)=0,0
Exp/Cntr=0.3,0.1

Type RM Length L Ch R = 1 ,1717    ,286.5,291,291.9
XS GIS Cut Line= 2
2021585.25088319 292904.158524262021430.30296654293280.460607573
#Sta/Elev= 30
       0 1684.91    57.4 1641.74    66.4 1633.95      77 1623.58    94.8 1608.76
   115.2 1586.02   123.1 1575.28   133.8 1563.46   144.4 1550.19     148 1546.71
   155.1  1536.9   157.9 1534.97   159.71534.491   169.3 1533.64   180.6 1534.82
   200.7 1534.72   220.81535.474     226 1536.15   233.1 1539.69   236.7 1540.53
   250.8 1540.34     266 1542.85     293 1545.75   313.8 1551.01   328.9 1555.31
   338.9 1558.77   346.4  1560.3   371.6 1559.09   391.7 1556.58     407 1558.69
#Mann= 5 ,-1 , 0
       0      .1       0   159.7    .045       0   220.8      .1       0
     300     .06       0  406.95     .08       0
Bank Sta=159.7,220.8
XS Rating Curve= 0 ,0
Exp/Cntr(USF)=0,0
Exp/Cntr=0.3,0.1

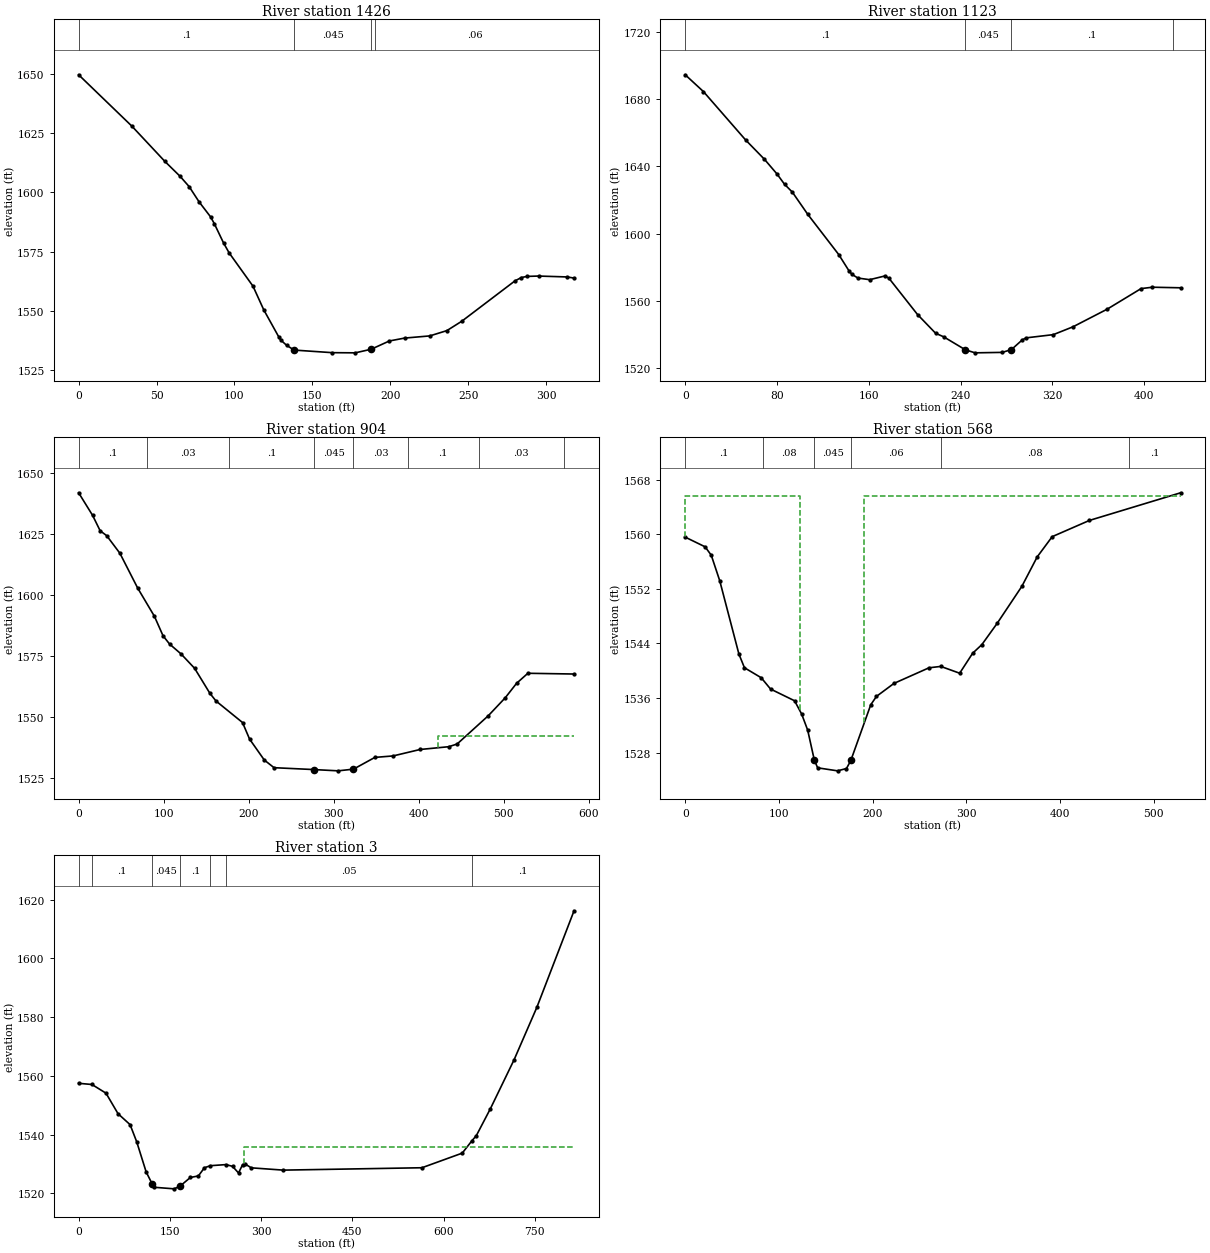
Type RM Length L Ch R = 1 ,1426    ,307.4,302.9,298.4
XS GIS Cut Line= 2
2021323.53213319292816.9189409172021180.30296651293100.773107573
#Sta/Elev= 30
       0 1649.51    34.2 1627.85    55.3 1613.05    65.1 1606.74    70.9 1602.42
    77.3 1595.97    84.7 1589.63    87.1 1586.75      93 1578.65    96.6 1574.46
   111.9 1560.44   118.8 1550.48   128.6 1538.88   129.7 1537.76   133.5 1535.52
   138.31533.531   162.8 1532.44   177.5 1532.37   187.71533.879   199.4 1537.37
   209.2 1538.59   225.3  1539.5   236.3 1541.73   245.9  1545.7     280 1562.69
   284.1  1564.1   287.7 1564.57   295.1 1564.72   313.5 1564.34   317.9 1563.86
#Mann= 4 ,-1 , 0
       0      .1       0   138.3    .045       0   187.7      .1       0
     190     .06       0
Bank Sta=138.3,187.7
XS Rating Curve= 0 ,0
Exp/Cntr(USF)=0,0
Exp/Cntr=0.3,0.1

Type RM Length L Ch R = 1 ,1123    ,242.3,218.7,165.4
XS GIS Cut Line= 4
2020956.29278731292576.0838891712020999.31338319292759.627274245
2020957.64671651 292900.252274262020965.45921651292996.606440917
#Sta/Elev= 30
       0 1694.31    15.9 1684.31    52.6 1655.62      69 1644.15    79.9 1635.47
    86.6 1629.25    93.4 1624.59   106.8 1611.42   133.8 1587.53   142.7 1577.92
   145.4 1575.72   150.6 1573.55   160.8 1572.59   174.2 1574.82   177.6 1573.44
   202.5  1551.9   218.3 1540.75   225.3 1538.65   244.31530.906   252.7 1529.13
   276.4  1529.4   284.41531.081   293.8  1536.8   297.2 1538.03   320.9 1539.94
   338.1 1544.61   367.8 1555.05   397.4 1567.29   407.3 1568.11   431.9 1567.77
#Mann= 4 ,-1 , 0
       0      .1       0   244.3    .045       0   284.4      .1       0
  425.19     .06       0
Bank Sta=244.3,284.4
XS Rating Curve= 0 ,0
Exp/Cntr(USF)=0,0
Exp/Cntr=0.5,0.3

Type RM Length L Ch R = 1 ,904     ,329,336,352.9
XS GIS Cut Line= 4
2020591.52004987292608.031416941 2020606.5300453292713.969793725
2020901.88942675292846.1042538452020927.19287288292996.117541617
#Sta/Elev= 30
       01642.073  16.457 1632.78  25.3141626.467  33.0251624.447  48.5331617.232
  69.4741602.915  89.1661591.321  99.2971583.319 106.9961579.921 120.4641575.873
 136.4391569.955 154.3691559.706 161.5571556.542  192.771547.689 201.0931540.874
 218.3871532.283 229.847 1529.14 276.571 1528.37 305.2471527.846 323.2951528.543
 348.4551533.369 369.8651533.969 401.6551536.619 435.2291537.753  445.211538.873
 481.8091550.473 501.7721557.855 515.081 1563.79  528.391567.924 582.6971567.617
#Mann= 8 ,-1 , 0
       0      .1       0      80     .03       0     177      .1       0
 276.571    .045       0 323.295     .03       0     387      .1       0
  470.57     .03       0  570.57      .1       0
#XS Ineff= 2 , 0
             176 1541.96     423         1541.96
Permanent Ineff=
       F       F
Bank Sta=276.571,323.295
XS Rating Curve= 0 ,0
Exp/Cntr(USF)=0,0
Exp/Cntr=0.5,0.3

Type RM Length L Ch R = 1 ,568     ,535.9,564.4,593.6
XS GIS Cut Line= 4
2020471.41137521292911.5299494022020469.15538478 292974.69768131
2020682.34647997293061.5533126822020917.65988649293066.303549604
#Sta/Elev= 30
       0 1559.58  21.2071558.164  27.7731556.938  36.8521553.184  57.3191542.439
  63.2081540.444  81.1061538.979  91.0881537.321 116.7191535.603  124.271533.657
 130.7041531.302 137.789 1526.91 141.3321525.778 162.5881525.337 172.0961525.678
 176.7581526.857 198.0141535.017 204.1321536.247 222.813 1538.15 260.1971540.436
 272.7831540.638  292.921539.641 306.7741542.568 316.6181543.833 333.0261546.967
 359.2781552.367 375.6851556.689 391.6721559.651 431.4711562.033 528.7741566.081
#Mann= 6 ,-1 , 0
       0      .1       0   83.21     .08       0 137.789    .045       0
 176.758     .06       0  273.21     .08       0  473.41      .1       0
#XS Ineff= 2 , 0
             123  1565.6     191          1565.6
Permanent Ineff=
       F       F
Bank Sta=137.789,176.758
XS Rating Curve= 0 ,0
Exp/Cntr(USF)=0,0
Exp/Cntr=0.5,0.3

Type RM Length L Ch R = 1 ,3       ,3,3,3
XS GIS Cut Line= 3
2020029.44664333292822.3735150522019995.88797134293124.401562916
2019922.84850879293629.755682218
#Sta/Elev= 30
       0 1557.49    21.9 1557.09      45 1554.13    64.8 1547.14    84.6 1543.42
    95.5 1537.58     111 1527.34   120.9 1523.25   124.2  1522.1   157.2 1521.57
   167.1 1522.55   183.7 1525.44   196.9 1525.96   206.8 1528.75   216.7 1529.45
   242.3 1529.82     253 1529.23   262.9 1526.97   269.5 1529.76   272.8 1530.13
   283.9 1528.72   336.5 1527.94   564.4 1528.75   630.7 1533.73   646.4 1537.88
   653.9  1539.7   677.1  1548.9     716 1565.54   753.3 1583.32814.4918 1616.22
#Mann= 7 ,-1 , 0
       0    .016       0    21.9      .1       0   120.9    .045       0
   167.1      .1       0   216.7    .016       0   242.3     .05       0
   646.4      .1       0
#XS Ineff= 2 , 0
       0                  271.55       0 1535.95
Permanent Ineff=
       F       F
Bank Sta=120.9,167.1
XS Rating Curve= 0 ,0
Exp/Cntr(USF)=0,0
Exp/Cntr=0.3,0.1
LCMann Table=0

Chan Stop Cuts=-1
Use User Specified Reach Order=0
Composite Channel Slope=5